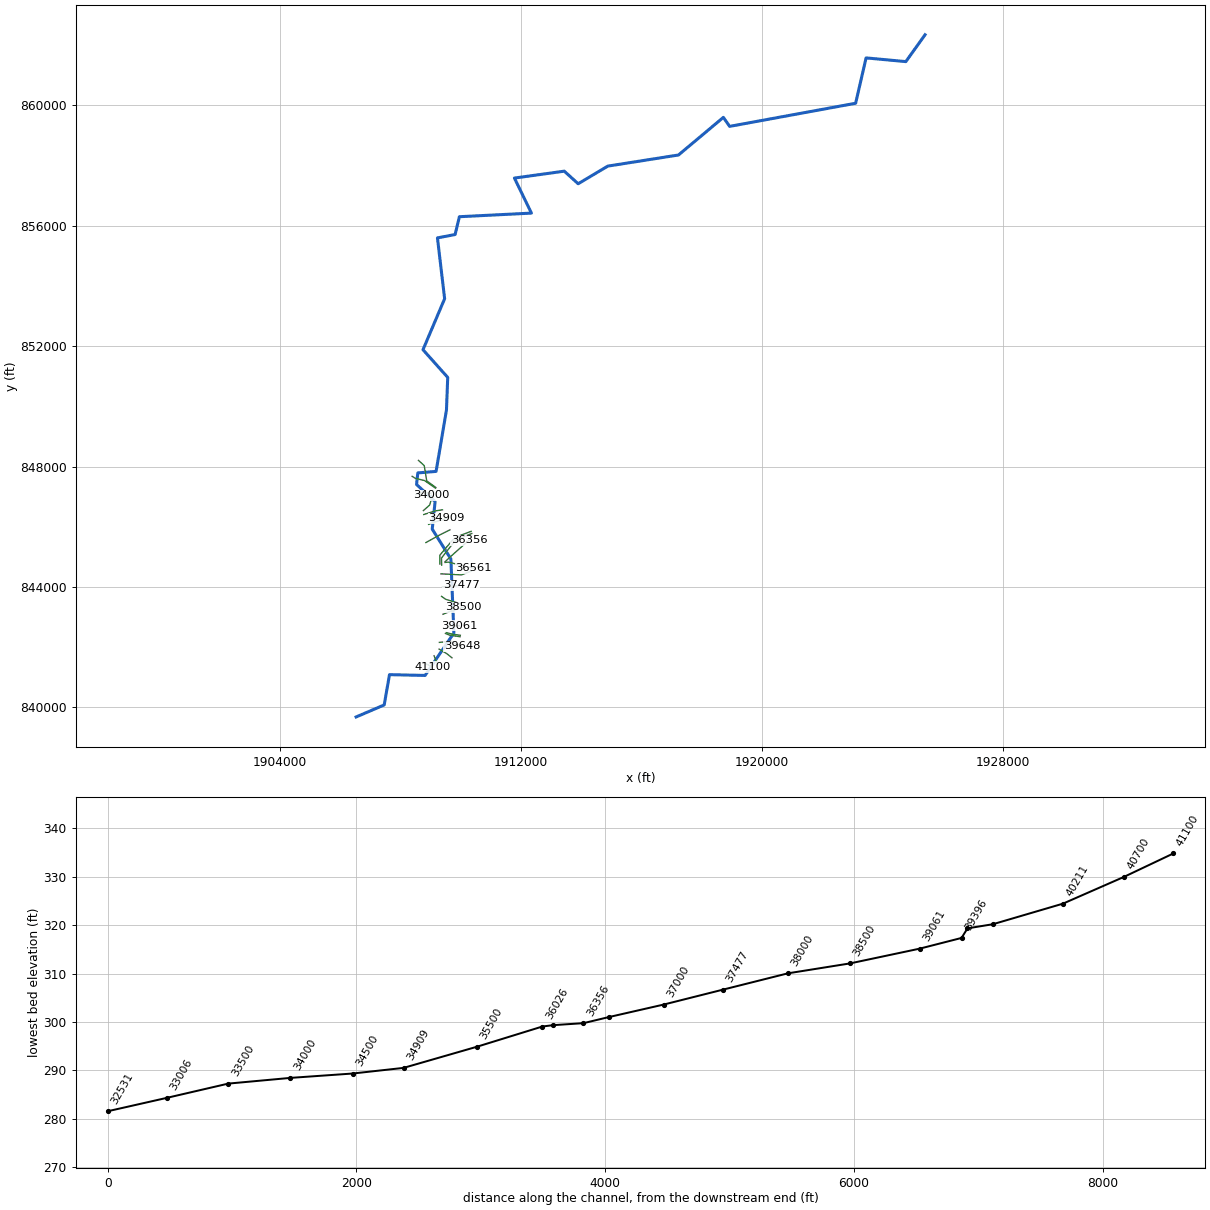
--- WATEREE CREEK.prj (project) ---

Proj Title=WATEREE CREEK Limited Detail Study
Current Plan=p04
Default Exp/Contr=0.3,0.1
English Units
Geom File=g01
Geom File=g02
Geom File=g03
Geom File=g04
Flow File=f01
Plan File=p01
Plan File=p02
Plan File=p03
Plan File=p04
Y Axis Title=Elevation
X Axis Title(PF)=Main Channel Distance
X Axis Title(XS)=Station
BEGIN DESCRIPTION:
WATEREE CREEK
END DESCRIPTION:
DSS Export Rating Curves= 0
DSS Export Rating Curve Sorted= 0
DSS Export Volume Flow Curves= 0
DXF OffsetX= 0
DXF OffsetY= 0
DXF ScaleX= 1
DXF ScaleY= 10

--- WATEREE CREEK.p04 (plan) ---

Plan Title=Proposed
Program Version=4.10
Short Identifier=Prop
Geom File=g04
Flow File=f01
Subcritical Flow
K Sum by GR= 0
Std Step Tol= 0.01
Critical Tol= 0.01
Num of Std Step Trials= 20
Max Error Tol= 0.3
Flow Tol Ratio= 0.001
Split Flow NTrial= 30
Split Flow Tol= 0.02
Split Flow Ratio= 0.02
Log Output Level= 0
Friction Slope Method= 1
Unsteady Friction Slope Method= 2
Unsteady Bridges Friction Slope Method= 1
Parabolic Critical Depth
Global Vel Dist= 0 , 0 , 0
Global Log Level= 0
CheckData=True
Encroach Param=-1 ,0,0, 0
Computation Interval=1HOUR
Output Interval=1HOUR
Run HTab= 0
Run UNet= 0
Run PostProcess= 0
Run WQNet= 0
UNET Theta= 1
UNET Theta Warmup= 1
UNET ZTol= 0.02
UNET ZSATol= 0.05
UNET MxIter= 20
UNET MaxInSteps= 0
UNET DtIC= 0
UNET DtMin= 0
UNET MaxCRTS= 20
UNET WFStab= 2
UNET SFStab= 1
UNET WFX= 1
UNET SFX= 1
UNET DSS MLevel= 4
UNET DZMax Abort= 100
UNET Convert EG Bridges= 0
UNET Use Existing IB Tables=-1
UNET Froude Reduction=False
UNET Froude Limit= 1
UNET Froude Power= 10
UNET Time Slicing=0,0, 5
UNET Junction Losses=0
Instantaneous Interval=1HOUR
Write IC File= 0
Write IC File at Sim End=0
Echo Input=False
Echo Parameters=False
Echo Output=False
Write Detailed= 0
WQ AD Non Conservative
WQ ULTIMATE=-1
WQ Max Comp Step=1HOUR
WQ Output Interval=15MIN
WQ Output Selected Increments= 0
WQ Output face flow=0
WQ Output face velocity=0
WQ Output face area=0
WQ Output face dispersion=0
WQ Output cell volume=0
WQ Output cell surface area=0
WQ Output cell continuity=0
WQ Output cumulative cell continuity=0
WQ Output face conc=0
WQ Output face dconc_dx=0
WQ Output face courant=0
WQ Output face peclet=0
WQ Output face adv mass=0
WQ Output face disp mass=0
WQ Output cell mass=0
WQ Output cell source sink temp=0
WQ Output cell source sink nsm=0
WQ Output MaxMinRange=-1
WQ Daily Max Min Mean=-1
WQ Daily Range=0
WQ Daily Time=0
WQ Create Restart=0
WQ Fixed Restart=0
WQ System Summary=0
WQ Use Fixed Temperature=0
Sorting and Armoring Iterations= 10
XS Update Threshold= 0.02
Hydraulics Update Threshold= 0.02
Energy Slope Method= 1
Volume Change Method= 0
XS Weighting Method= 0
Number of US Weighted Cross Sections= 1
Number of DS Weighted Cross Sections= 1
Upstream XS Weight=0.25
Main XS Weight=0.5
Downstream XS Weight=0.25
Number of DS XS's Weighted with US Boundary= 1
Upstream Boundary Weight= 1
Weight of XSs Associated with US Boundary= 0
Number of US XS's Weighted with DS Boundary= 1
Downstream Boundary Weight= 0.5
Weight of XSs Associated with DS Boundary= 0.5
Sediment Output Level= 4
Mass or Volume Output= 0
Output Increment Type= 1
Profile and TS Output Increment= 10
XS Output Flag= 0
XS Output Increment= 10
Disregard all LS=0
Disregard all Conn=0
Disregard all Breaches=0
Disregard all Pumps=0

--- WATEREE CREEK.p01 (plan) ---

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Plan Title=Multiple Run
Short Identifier=Multiple
Geom File=g01
Flow File=f01
Global Vel Dist=  1 , 1 , 1
Encroach Param= -1, 0, 0, 0
BEGIN DESCRIPTION:
Multiple Run
END DESCRIPTION:

--- WATEREE CREEK.p02 (plan) ---

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Plan Title=Effective
Short Identifier=EFF
Geom File=g02
Flow File=f01

--- WATEREE CREEK.p03 (plan) ---

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Plan Title=Corrected Effective
Short Identifier=CorrEff
Geom File=g03
Flow File=f01

--- WATEREE CREEK.f01 (steady flow) ---

Flow Title=Multiple
Number of Profiles=5
Profile Names=10-year,25-year,50-year,100-year,500-year
River Rch & RM= WATEREE CREEK,Reach-1,41100
     347     469     578     680     941
River Rch & RM= WATEREE CREEK,Reach-1,39648
     459     618     759     890    1226
River Rch & RM= WATEREE CREEK,Reach-1,38500
     477     641     787     923    1270
River Rch & RM= WATEREE CREEK,Reach-1,37000
     551     738     906    1061    1456
River Rch & RM= WATEREE CREEK,Reach-1,36356
     731     976    1193    1394    1903
River Rch & RM= WATEREE CREEK,Reach-1,35500
     926    1230    1501    1749    2378
River Rch & RM= WATEREE CREEK,Reach-1,33500
     948    1259    1536    1790    2433
River Rch & RM= WATEREE CREEK,Reach-1,33006
     958    1272    1551    1807    2456
River Rch & RM= WATEREE CREEK,Reach-1,32062
    1054    1397    1702    1981    2688
River Rch & RM= WATEREE CREEK,Reach-1,30500
    1076    1426    1738    2022    2742
River Rch & RM= WATEREE CREEK,Reach-1,29914
    1165    1542    1878    2183    2957
River Rch & RM= WATEREE CREEK,Reach-1,28500
    1177    1558    1896    2205    2985
River Rch & RM= WATEREE CREEK,Reach-1,26900
    1514    1994    2421    2808    3785
River Rch & RM= WATEREE CREEK,Reach-1,24347
    1557    2050    2489    2886    3888
River Rch & RM= WATEREE CREEK,Reach-1,22078
    1564    2059    2499    2897    3903
River Rch & RM= WATEREE CREEK,Reach-1,21731
    2516    3284    3968    4580    6117
River Rch & RM= WATEREE CREEK,Reach-1,19000
    2564    3345    4042    4663    6227
River Rch & RM= WATEREE CREEK,Reach-1,17000
    2569    3353    4050    4673    6240
River Rch & RM= WATEREE CREEK,Reach-1,15000
    2577    3362    4062    4686    6257
River Rch & RM= WATEREE CREEK,Reach-1,14500
    2673    3485    4209    4854    6477
River Rch & RM= WATEREE CREEK,Reach-1,12500
    2683    3498    4224    4872    6500
River Rch & RM= WATEREE CREEK,Reach-1,11101
    2688    3505    4232    4881    6512
River Rch & RM= WATEREE CREEK,Reach-1,10000
    2726    3553    4290    4947    6598
River Rch & RM= WATEREE CREEK,Reach-1,9000
    2842    3702    4468    5151    6865
River Rch & RM= WATEREE CREEK,Reach-1,7904
    2872    3740    4513    5202    6932
River Rch & RM= WATEREE CREEK,Reach-1,6500
    2892    3766    4545    5237    6979
River Rch & RM= WATEREE CREEK,Reach-1,4500
    2956    3847    4642    5348    7123
River Rch & RM= WATEREE CREEK,Reach-1,3000
    2976    3873    4672    5383    7169
Boundary for River Rch & Prof#=WATEREE CREEK,Reach-1,1
Up Type=0
Dn Type=3
Dn Slope=0.001
Boundary for River Rch & Prof#=WATEREE CREEK,Reach-1,2
Up Type=0
Dn Type=3
Dn Slope=0.001
Boundary for River Rch & Prof#=WATEREE CREEK,Reach-1,3
Up Type=0
Dn Type=3
Dn Slope=0.001
Boundary for River Rch & Prof#=WATEREE CREEK,Reach-1,4
Up Type=0
Dn Type=3
Dn Slope=0.001
Boundary for River Rch & Prof#=WATEREE CREEK,Reach-1,5
Up Type=0
Dn Type=3
Dn Slope=0.001

--- WATEREE CREEK.g04 (geometry) ---

Geom Title=Proposed
Program Version=4.10

River Reach=WATEREE CREEK   ,Reach-1
Reach XY= 30
      1906522.55       839685.45      1907454.88       840084.19
      1907630.97       841090.74      1908813.61       841064.36
      1909769.86       842474.66      1909670.17       844932.94
      1909051.09       845925.62      1909146.08       846842.25
      1908529.66       847407.97      1908572.11       847792.83
      1909178.56       847843.53      1909523.51       849880.21
      1909565.35        850965.4      1908743.95       851885.32
      1909462.69       853579.58      1909223.82       855600.92
      1909810.86       855712.54      1909952.93       856304.41
      1912346.62       856424.22      1911781.31       857588.47
      1913437.54       857817.53      1913898.44       857399.05
      1914883.34       857985.34      1917231.78       858354.94
      1918723.14       859604.67      1918931.47       859305.69
      1923116.29       860073.55      1923464.58       861580.89
      1924784.72       861457.18      1925423.86       862349.49

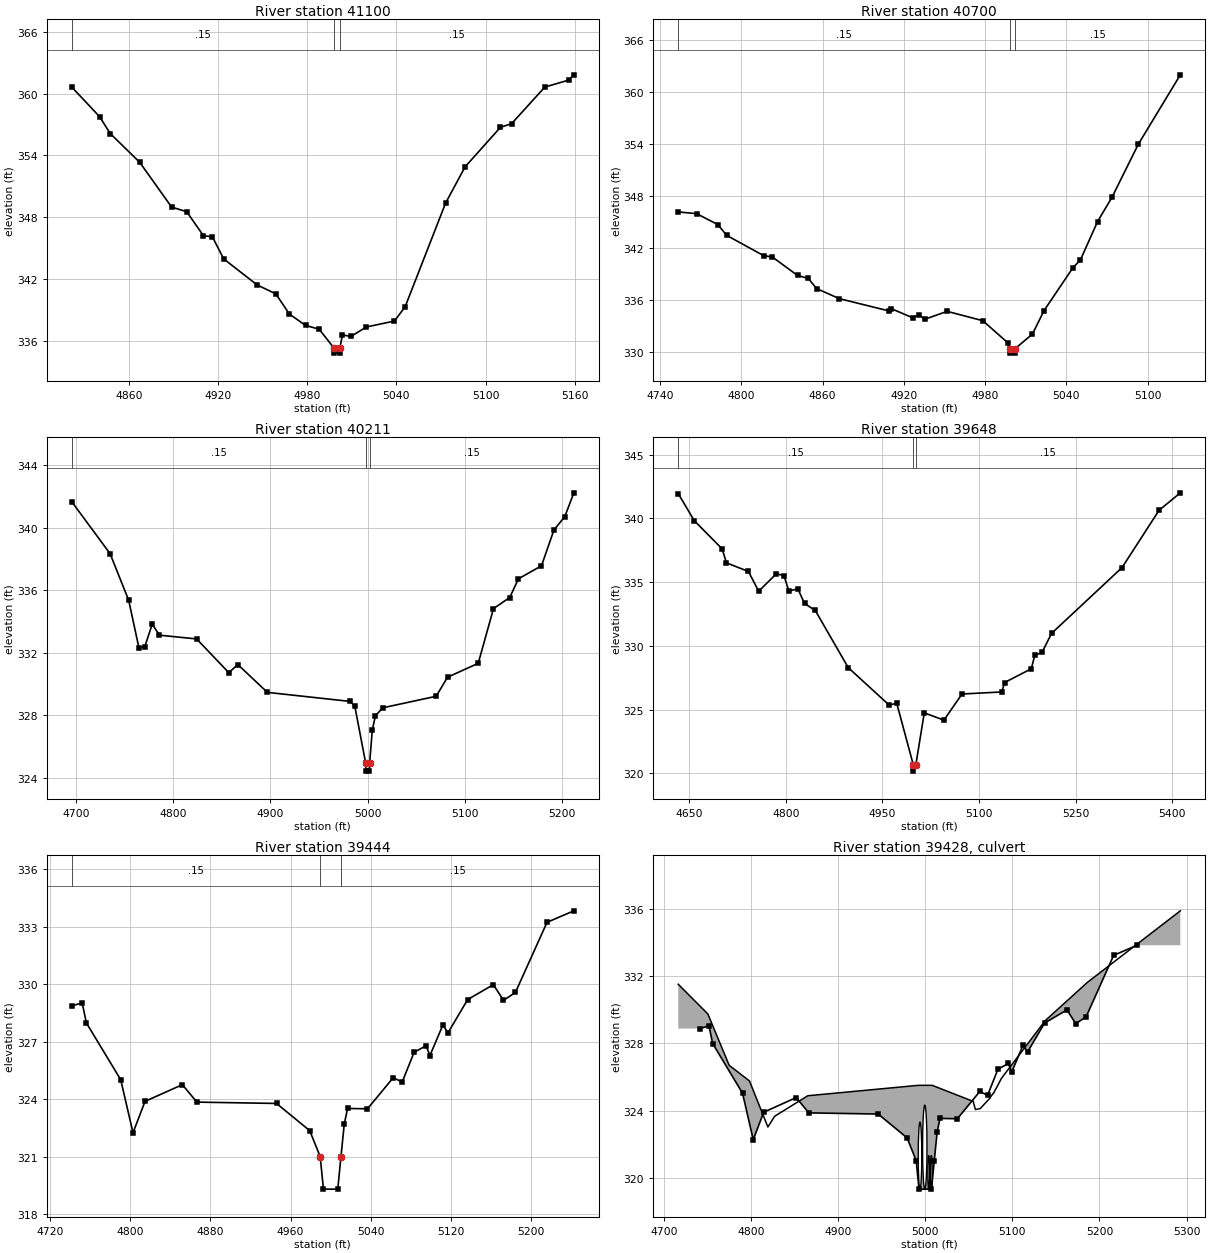
Type RM Length L Ch R = 1 ,41100   ,400,400,400
BEGIN DESCRIPTION:
WATEREE CREEK 82.0
END DESCRIPTION:
XS GIS Cut Line= 3
      1908746.81       841491.71      1908910.17       841420.03
      1909049.58       841342.73
#Sta/Elev= 30
  4821.6  360.64  4840.4  357.75  4847.5  356.12  4867.3  353.33  4888.8  348.97
  4898.9  348.53  4910.2  346.19  4916.2  346.09  4923.8  343.94  4946.3  341.41
  4958.9  340.54    4968  338.58  4978.9  337.47    4988  337.11    4998  335.28
  4998.3  334.78  5001.8  334.78    5002  335.28  5003.7  336.55  5009.4   336.4
  5019.8  337.32  5038.7   337.9  5045.9  339.29  5073.1  349.36  5086.2  352.88
    5110  356.73  5117.5  357.08  5139.9  360.64    5156  361.32  5159.4  361.83
#Mann= 3 ,-1 , 0
  4821.6     .15       0    4998     .05       0    5002     .15       0
Bank Sta=4998,5002
XS Rating Curve= 0 ,0
Exp/Cntr=0.3,0.1

Type RM Length L Ch R = 1 ,40700   ,489,489,489
BEGIN DESCRIPTION:
WATEREE CREEK 81.0
END DESCRIPTION:
XS GIS Cut Line= 3
      1909112.07        841717.2       1909203.9       841488.34
      1909218.88       841365.14
#Sta/Elev= 30
  4753.4  346.17    4767  345.97  4782.6  344.72  4789.2  343.47  4816.4  341.14
  4822.9  340.98  4841.5  338.85  4849.5  338.51  4855.5  337.35  4872.4  336.18
  4908.7  334.78  4910.7  335.03  4926.4  333.99  4931.1  334.35  4935.4  333.81
    4952  334.72  4978.3  333.64  4997.1  331.05    4998  330.41  4998.3  329.91
  5001.8  329.91    5002  330.41  5014.9   332.1  5023.5  334.81  5044.7  339.72
  5050.4  340.66    5063  345.06  5073.7  347.87    5093  353.94  5124.1  361.96
#Mann= 3 ,-1 , 0
  4753.4     .15       0    4998     .05       0    5002     .15       0
Bank Sta=4998,5002
XS Rating Curve= 0 ,0
Exp/Cntr=0.3,0.1

Type RM Length L Ch R = 1 ,40211   ,563,563,563
BEGIN DESCRIPTION:
WATEREE CREEK 80.0
END DESCRIPTION:
XS GIS Cut Line= 3
      1909278.89       841939.81      1909540.46       841783.91
      1909705.73       841650.82
#Sta/Elev= 30
  4695.5  341.65  4734.9  338.33  4754.1  335.34  4764.6   332.3  4770.7  332.38
  4778.3  333.82  4785.7  333.11    4824  332.87  4857.1  330.71  4866.4  331.23
  4896.8  329.45  4982.1  328.87  4986.8  328.56    4998  324.91  4998.3  324.41
  5001.8  324.41    5002  324.91  5004.8  327.05    5008  327.95  5015.4  328.46
  5070.5   329.2  5082.2  330.42  5113.8  331.31  5129.5  334.81  5146.2  335.52
  5155.2  336.72  5178.9  337.55  5191.7  339.84  5202.9   340.7  5212.2  342.22
#Mann= 3 ,-1 , 0
  4695.5     .15       0    4998     .05       0    5002     .15       0
Bank Sta=4998,5002
XS Rating Curve= 0 ,0
Exp/Cntr=0.3,0.1

Type RM Length L Ch R = 1 ,39648   ,204,204,204
BEGIN DESCRIPTION:
WATEREE CREEK 79.0
END DESCRIPTION:
XS GIS Cut Line= 3
       1909288.4       842162.44      1909653.24       842201.31
      1910032.13       842037.98
#Sta/Elev= 30
  4633.1  341.94  4657.9  339.82  4701.3   337.6  4707.9  336.51  4742.1  335.83
    4758  334.28  4785.4  335.65  4797.2  335.51  4804.7  334.32    4819  334.45
  4829.2  333.32  4845.9  332.77    4897  328.29    4961  325.33  4972.2  325.52
    4998  320.67  4998.3  320.17    5002  320.67  5015.1  324.74  5045.6  324.17
  5073.7  326.22  5135.4  326.38  5139.8  327.12  5181.2   328.2  5186.7  329.26
  5197.8  329.48  5212.8  330.98  5322.2  336.14  5379.6  340.63  5412.6     342
#Mann= 3 ,-1 , 0
  4633.1     .15       0    4998     .05       0    5002     .15       0
Bank Sta=4998,5002
XS Rating Curve= 0 ,0
Exp/Cntr=0.5,0.3

Type RM Length L Ch R = 1 ,39444   ,48,48,48
BEGIN DESCRIPTION:
WC_Private Dr-US
END DESCRIPTION:
XS GIS Cut Line= 4
      1909488.73       842459.12      1909618.24       842406.76
       1909735.3        842385.9      1909975.78       842350.27
#Sta/Elev= 30
  4741.4  328.88  4751.8  329.04    4756  327.99  4790.3  325.03  4802.6  322.26
  4814.6   323.9  4851.9  324.77  4866.4  323.86    4946  323.79  4979.2  322.37
  4989.6  321.02  4992.9  319.32  5007.2  319.32  5010.4  321.02  5013.7  322.72
    5017  323.53  5036.9  323.51  5062.7  325.14  5071.5   324.9  5083.5  326.46
  5095.4   326.8  5099.3  326.29  5112.2  327.88  5117.4  327.48    5137  329.21
  5162.7  329.99  5172.8  329.17  5184.7  329.58  5216.3  333.24  5243.1  333.84
#Mann= 3 ,-1 , 0
  4741.4     .15       0  4989.6     .05       0  5010.4     .15       0
#XS Ineff= 2 , 0
       0    4984     320    5016       0     320
Permanent Ineff=
       F       F
Bank Sta=4989.6,5010.4
XS Rating Curve= 0 ,0
Exp/Cntr=0.5,0.3

Type RM Length L Ch R = 2 ,39428   ,,,
BEGIN DESCRIPTION:
WC_Private Dr-TOR
Structure ID: lds 12
Approximate Survey Structure
END DESCRIPTION:
Bridge Culvert--1,0,-1,-1, 0
Deck Dist Width WeirC Skew NumUp NumDn MinLoCord MaxHiCord MaxSubmerge Is_Ogee
8,16,3,0, 23, 23, , , 0.95, 0, 1,1,,
  4716.5  4750.5    4775  4798.3  4819.4  4827.2  4865.2    4992    5008  5054.3
  5054.9  5057.6    5063  5074.5  5075.5  5079.3    5080  5082.3  5087.2  5087.7
  5137.7  5185.9  5292.8
  331.52  329.75  326.69  325.76  323.02  323.66  324.88   325.5   325.5  324.56
  324.57  324.06  324.11  324.75  324.85   325.1   325.2   325.4  325.89  325.93
  329.35  331.62  335.89
  297.42  297.42  297.42  297.42  297.42  297.42  297.42  297.42  297.42  297.42
  297.42  297.42  297.42  297.42  297.42  297.42  297.42  297.42  297.42  297.42
  297.42  297.42  297.42
  4716.5  4750.5    4775  4798.3  4819.4  4827.2  4865.2    4992    5008  5054.3
  5054.9  5057.6    5063  5074.5  5075.5  5079.3    5080  5082.3  5087.2  5087.7
  5137.7  5185.9  5292.8
  331.52  329.75  326.69  325.76  323.02  323.66  324.88   325.5   325.5  324.56
  324.57  324.06  324.11  324.75  324.85   325.1   325.2   325.4  325.89  325.93
  329.35  331.62  335.89
  297.34  297.34  297.34  297.34  297.34  297.34  297.34  297.34  297.34  297.34
  297.34  297.34  297.34  297.34  297.34  297.34  297.34  297.34  297.34  297.34
  297.34  297.34  297.34
BR Coef= 1 , 1 , 0 ,1.25, 0 ,,,0.8,0,2,0,
WSPro=,,,, 1 ,,,, 0 ,,,, 0 ,,,,-1 ,-1 ,-1 , 0 , 0 , 0 , 0 , 0
Culvert=1,4,,16,0.024,0.9,1,2,3,319.32,4994,317.34,4994,Culvert #1  , 0 ,8
Culvert Bottom n=0.024
Culvert=1,5,,16,0.024,0.9,1,2,3,319.32,4999.5,317.34,4999.5,Culvert #2  , 0 ,8
Culvert Bottom n=0.024
Culvert=1,2,,16,0.024,0.9,1,2,3,319.32,5004,317.34,5004,Culvert #3  , 0 ,8
Culvert Bottom n=0.024
Culvert=1,2,,16,0.024,0.9,1,2,3,319.32,5007,317.34,5007,Culvert #4  , 0 ,8
Culvert Bottom n=0.024
BC Design=,, 0 ,, 0 ,,,,,,
BC HTab HWMax=333.9
BC Use User HTab Curves=0
BC User HTab FreeFlow(D)= 0

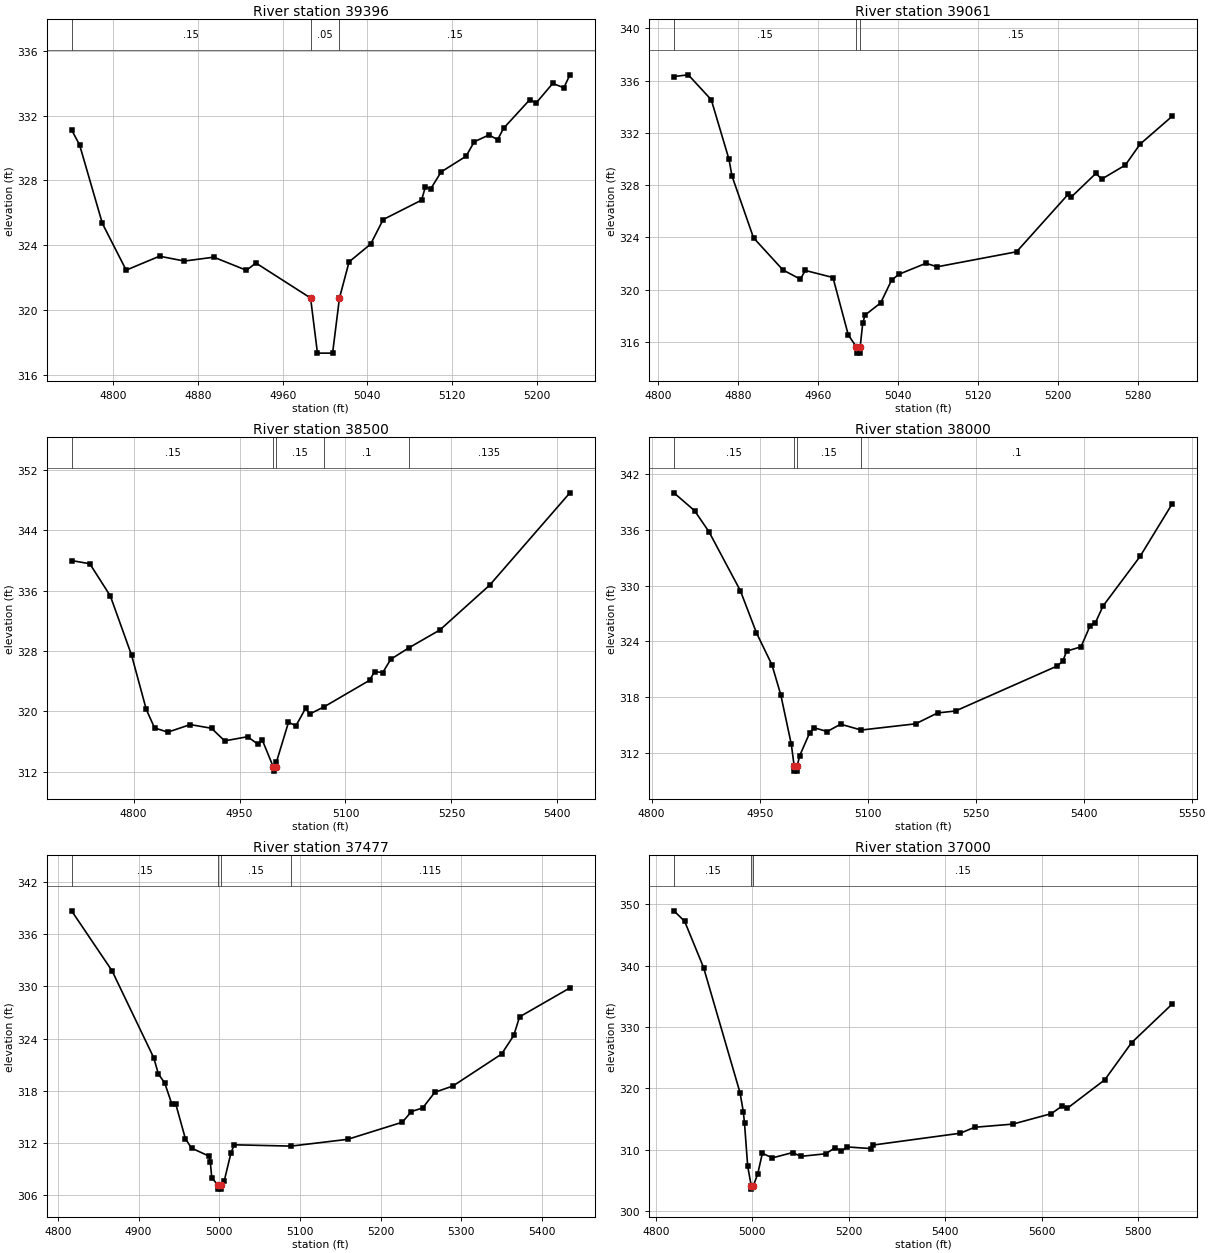
Type RM Length L Ch R = 1 ,39396   ,335,335,335
BEGIN DESCRIPTION:
WC_Private Dr-DS
END DESCRIPTION:
XS GIS Cut Line= 3
      1909521.98       842485.13      1909749.15       842430.88
      1909984.46       842399.09
#Sta/Elev= 30
  4760.5  331.12  4768.1  330.18  4789.6  325.34  4812.1  322.46  4843.6  323.32
  4867.1  323.02  4894.9  323.26  4925.8  322.45  4934.7   322.9  4986.4  320.74
  4992.9  317.34  5007.2  317.34  5013.7  320.74  5022.8  322.97  5043.2  324.07
    5055  325.58  5091.3  326.78  5094.9   327.6    5100  327.48  5109.8  328.52
  5133.4  329.49  5141.1  330.38    5155   330.8  5163.2  330.51  5168.8  331.21
  5193.5  332.97  5199.7  332.78  5215.3  333.98  5225.8  333.71  5231.5  334.51
#Mann= 3 ,-1 , 0
  4760.5     .15       0  4986.4     .05       0  5013.7     .15       0
#XS Ineff= 2 , 0
       0    4968     320    5032       0     320
Permanent Ineff=
       F       F
Bank Sta=4986.4,5013.7
XS Rating Curve= 0 ,0
Exp/Cntr=0.5,0.3

Type RM Length L Ch R = 1 ,39061   ,561,561,561
BEGIN DESCRIPTION:
WATEREE CREEK 78.0
END DESCRIPTION:
XS GIS Cut Line= 3
      1909478.92       842623.41      1909639.47       842714.31
      1909953.77       842714.09
#Sta/Elev= 30
  4815.5  336.32  4829.9  336.45  4852.9  334.54  4870.6  329.99  4873.6  328.71
  4895.2  323.97  4924.6  321.51  4942.1   320.8    4947  321.47  4974.7  320.93
  4990.1  316.52    4998  315.64  4998.3  315.14  5001.8  315.14    5002  315.64
  5004.5  317.43  5006.8  318.05  5022.5  318.99  5033.4  320.73  5040.8  321.18
  5067.8  322.02    5079  321.75  5158.5   322.9    5210  327.29  5213.1  327.08
    5238  328.91  5243.6  328.46  5267.4  329.54  5282.1  331.14  5314.3  333.28
#Mann= 3 ,-1 , 0
  4815.5     .15       0    4998     .05       0    5002     .15       0
Bank Sta=4998,5002
XS Rating Curve= 0 ,0
Exp/Cntr=0.3,0.1

Type RM Length L Ch R = 1 ,38500   ,500,500,500
BEGIN DESCRIPTION:
WATEREE CREEK 77.0
END DESCRIPTION:
XS GIS Cut Line= 3
      1909407.65       843097.86      1909675.34       843203.53
      1910074.99         843325.
#Sta/Elev= 30
  4712.2     340    4738  339.58  4767.1   335.3  4797.2  327.44  4817.9  320.28
  4829.7  317.81  4848.5  317.26  4880.3  318.26  4910.3  317.77  4928.9   316.1
  4961.4  316.65  4976.3  315.64    4982  316.26    4998  312.59  4998.3  312.09
    5002  312.59  5002.3  313.32  5019.3  318.56  5029.9  318.11  5043.4   320.4
  5049.4  319.66    5070  320.63  5134.1  324.13  5141.2  325.29  5152.7  325.15
  5164.1  326.92    5190  328.45  5233.6   330.8  5304.2  336.75  5417.7  348.98
#Mann= 5 ,-1 , 0
  4712.2     .15       0    4998     .05       0    5002     .15       0
    5070      .1       0    5190    .135       0
Bank Sta=4998,5002
XS Rating Curve= 0 ,0
Exp/Cntr=0.3,0.1

Type RM Length L Ch R = 1 ,38000   ,523,523,523
BEGIN DESCRIPTION:
WATEREE CREEK 76.0
END DESCRIPTION:
XS GIS Cut Line= 3
      1909359.89       843691.96      1909497.71       843593.98
      1909998.79       843444.16
#Sta/Elev= 30
  4830.9  339.98  4859.6  338.06  4879.6  335.79  4923.2  329.45  4945.6  324.91
  4967.1  321.47  4979.3  318.26    4994  312.91    4998  310.54  4998.3  310.04
  5001.8  310.04    5002  310.54  5005.5  311.68  5019.5  314.16  5025.8   314.7
  5043.8   314.3  5062.5  315.09    5091  314.46  5166.6  315.13  5197.2   316.3
    5222  316.51  5362.7  321.33    5371  321.86  5376.3  322.95  5396.3  323.41
    5409  325.69  5416.4  326.02  5426.9   327.8  5478.3  333.13    5523   338.8
#Mann= 4 ,-1 , 0
  4830.9     .15       0    4998     .05       0    5002     .15       0
    5091      .1       0
Bank Sta=4998,5002
XS Rating Curve= 0 ,0
Exp/Cntr=0.3,0.1

Type RM Length L Ch R = 1 ,37477   ,477,477,477
BEGIN DESCRIPTION:
WATEREE CREEK 75.0
END DESCRIPTION:
XS GIS Cut Line= 3
      1909396.31       844014.24      1909579.37       844010.46
      1910011.36       844058.97
#Sta/Elev= 30
  4816.9  338.69    4867   331.8  4918.7   321.8  4924.6   319.9  4932.3   318.9
  4941.1  316.48    4946  316.48    4958  312.47  4965.6  311.39  4987.2  310.47
  4988.9  309.79  4990.7  307.98    4998  307.17  4998.3  306.67  5001.8  306.67
    5002  307.17  5006.2  307.63  5014.6  310.88  5018.7  311.77    5089  311.62
  5159.2   312.4    5227  314.37  5238.3   315.6  5252.2  316.01  5267.3  317.82
  5289.6  318.53    5350  322.21  5365.1  324.35  5372.3  326.49  5434.7  329.82
#Mann= 4 ,-1 , 0
  4816.9     .15       0    4998     .05       0    5002     .15       0
    5089    .115       0
Bank Sta=4998,5002
XS Rating Curve= 0 ,0
Exp/Cntr=0.3,0.1

Type RM Length L Ch R = 1 ,37000   ,439,439,439
BEGIN DESCRIPTION:
WATEREE CREEK 74.0
END DESCRIPTION:
XS GIS Cut Line= 4
      1909338.97       844438.26      1909501.28       844432.72
      1910022.65       844405.42      1910348.05        844530.8
#Sta/Elev= 30
  4837.6  348.95  4859.8  347.25  4899.1  339.71  4974.7   319.3  4981.5  316.21
    4984   314.3  4990.6  307.32    4998  304.09  4998.3  303.59    5002  304.09
  5011.4  306.07    5021  309.44  5041.5  308.68  5083.9  309.55  5100.5  308.93
  5152.2  309.35  5172.1  310.34  5184.8   309.8  5197.5  310.46  5246.5   310.2
  5250.2  310.77  5431.2   312.7    5461  313.67  5540.4  314.19  5620.1  315.89
  5642.4  317.13  5653.5  316.78  5731.1  321.42  5786.4  327.44  5870.8  333.76
#Mann= 3 ,-1 , 0
  4837.6     .15       0    4998     .05       0    5002     .15       0
Bank Sta=4998,5002
XS Rating Curve= 0 ,0
Exp/Cntr=0.3,0.1

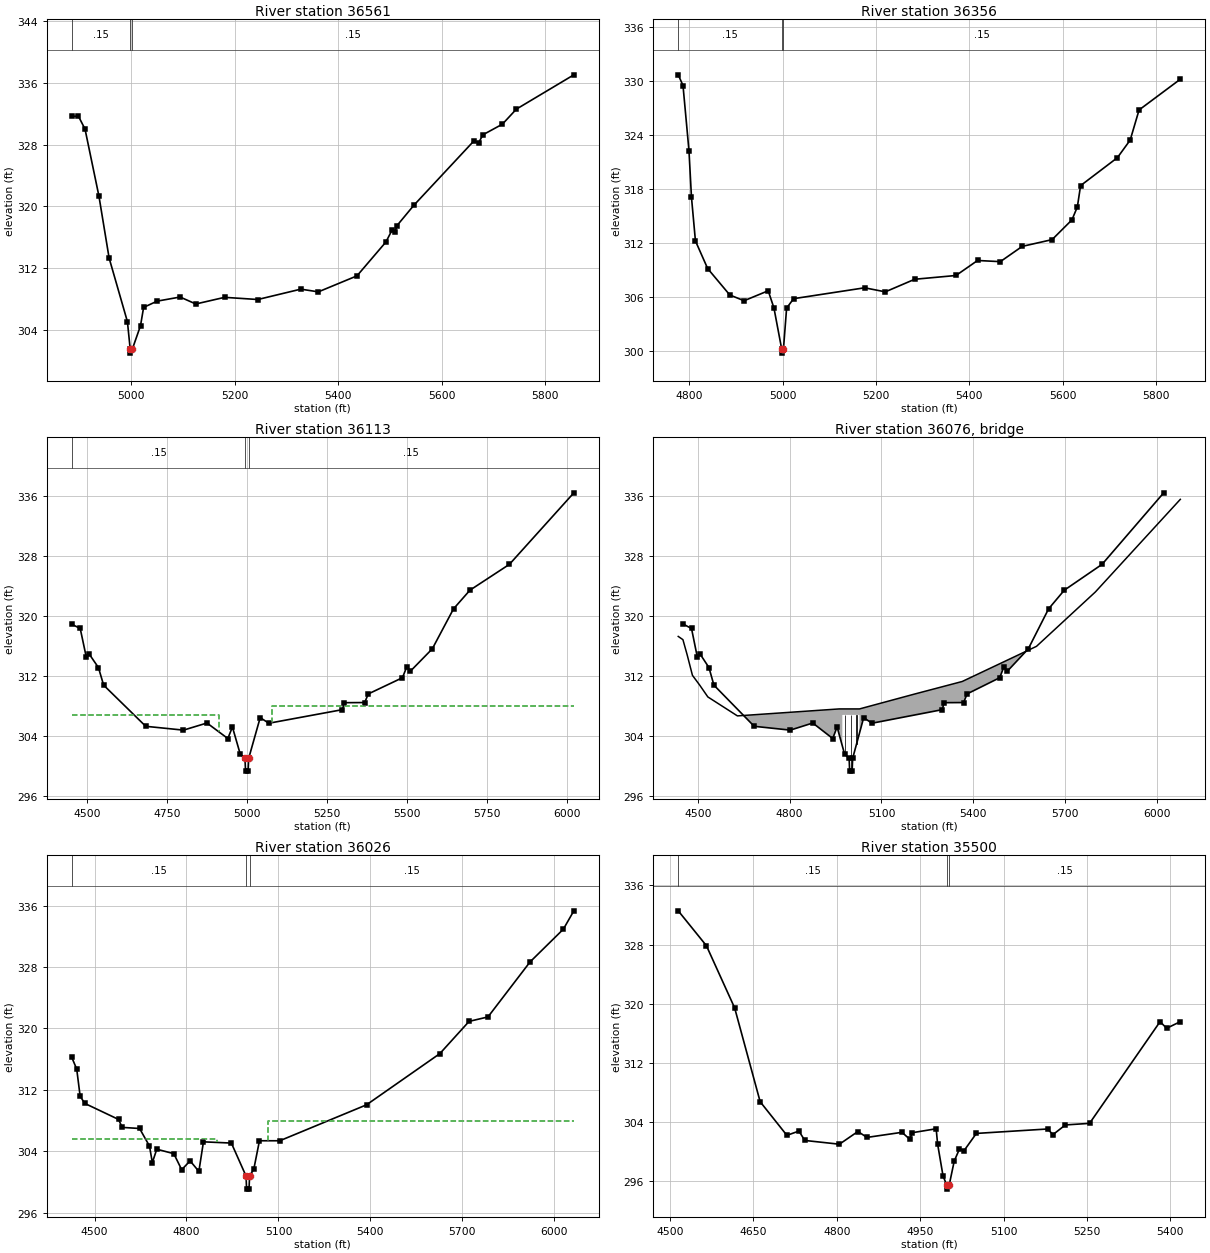
Type RM Length L Ch R = 1 ,36561   ,205,205,205
BEGIN DESCRIPTION:
WATEREE CREEK 73.0
END DESCRIPTION:
XS GIS Cut Line= 3
      1909478.98       844819.23      1909587.37       844828.26
        1910425.         844625.
#Sta/Elev= 30
    4885  331.67  4897.9  331.68  4910.6  330.02  4937.5  321.35  4957.2  313.33
  4992.6  305.09    4998  301.52  4998.3  301.02    5002  301.52  5017.9  304.57
  5023.9  306.94  5050.1  307.75  5094.5  308.28  5124.8  307.38  5180.5  308.24
  5244.7  307.96  5327.8   309.3  5361.7  308.95  5436.4  311.02  5492.3   315.4
  5504.5  316.98    5510  316.65  5513.2  317.48  5546.3  320.15  5662.1  328.46
  5671.9  328.28  5679.9  329.28  5717.5  330.65  5744.6   332.6  5855.7  337.04
#Mann= 3 ,-1 , 0
    4885     .15       0    4998     .05       0    5002     .15       0
Bank Sta=4998,5002
XS Rating Curve= 0 ,0
Exp/Cntr=0.3,0.1

Type RM Length L Ch R = 1 ,36356   ,243,243,243
BEGIN DESCRIPTION:
WATEREE CREEK 72.0
END DESCRIPTION:
XS GIS Cut Line= 3
      1909475.93        844840.3      1909635.56        844990.9
      1910274.02       845560.09
#Sta/Elev= 30
  4776.7  330.73  4786.9  329.54  4799.7  322.28    4805  317.13  4813.5  312.25
  4839.7  309.17  4887.1  306.23  4917.7  305.59  4969.3   306.7  4981.6  304.78
    4998  300.26  4998.3  299.76    5002  300.26  5008.7  304.77  5023.7  305.82
  5175.7  307.03    5220  306.58  5282.9  307.98  5371.3   308.4  5417.5  310.07
  5466.2  309.94  5513.1  311.64    5577  312.39  5619.5  314.59  5631.1  316.03
    5638   318.4  5716.8  321.51  5744.2  323.47  5763.2  326.82  5851.5  330.24
#Mann= 3 ,-1 , 0
  4776.7     .15       0    4998     .05       0    5002     .15       0
Bank Sta=4998,5002
XS Rating Curve= 0 ,0
Exp/Cntr=0.5,0.3

Type RM Length L Ch R = 1 ,36113   ,87,87,87
BEGIN DESCRIPTION:
WC_Old Hilton RD - US
END DESCRIPTION:
XS GIS Cut Line= 6
       1909364.5       844731.91      1909358.48        844966.8
       1909774.1       845493.86      1909840.36       845560.12
      1909918.66       845602.28      1910364.43       845779.99
#Sta/Elev= 30
    4453  318.95  4479.4  318.38  4498.3  314.57  4507.1  314.99  4536.3  313.17
  4552.6  310.82  4684.1  305.33  4802.1  304.82  4875.5  305.77  4940.7   303.7
    4955  305.24  4979.5  301.61  4994.3  301.05    4996  299.35    5004  299.35
  5005.8  301.05  5041.8  306.49  5068.8  305.74  5298.5  307.55  5304.5  308.48
  5368.3   308.5  5379.6  309.65  5486.2  311.81  5499.3   313.2  5511.3  312.69
  5579.6  315.67  5645.9     321  5697.2  323.49  5820.6  326.94  6021.9  336.48
#Mann= 3 ,-1 , 0
    4453     .15       0  4994.3     .05       0  5005.8     .15       0
#XS Ineff= 2 , 0
       0    4913  306.87    5080       0     308
Permanent Ineff=
       F       F
Bank Sta=4994.3,5005.8
XS Rating Curve= 0 ,0
Exp/Cntr=0.5,0.3

Type RM Length L Ch R = 3 ,36076   ,,,
BEGIN DESCRIPTION:
WC_Old Hilton RD (DS) - TOR
Structure ID: lds 15
Approximate Survey Structure
END DESCRIPTION:
Bridge Culvert--1,0,-1,-1, 0
Deck Dist Width WeirC Skew NumUp NumDn MinLoCord MaxHiCord MaxSubmerge Is_Ogee
24,26,3,0, 18, 18, , , 0.95, 0, 1,1,,
    4436  4451.3  4465.2  4482.4    4506  4532.7  4629.3  4961.8    4972    4972
    5028    5028  5028.3  5208.6  5363.7  5606.4  5798.6  6076.2
  317.32  316.89  314.86  312.13  310.83  309.25  306.72  307.65  307.65  307.65
  307.65  307.65  307.65  309.64  311.31     316  323.25  335.61
  279.32  279.32  279.32  279.32  279.32  279.32  279.32  279.32  279.32  306.85
  306.85  279.32  279.32  279.32  279.32  279.32  279.32  279.32
    4436  4451.3  4465.2  4482.4    4506  4532.7  4629.3  4961.8    4972    4972
    5028    5028  5028.3  5208.6  5363.7  5606.4  5798.6  6076.2
  317.32  316.89  314.86  312.13  310.83  309.25  306.72  307.65  307.65  307.65
  307.65  307.65  307.65  309.64  311.31     316  323.25  335.61
  279.32  279.32  279.32  279.32  279.32  279.32  279.32  279.32  279.32  306.85
  306.85  279.32  279.32  279.32  279.32  279.32  279.32  279.32
Pier Skew, UpSta & Num, DnSta & Num=  ,4981.3, 2 ,4981.3, 2 , 0 , 0 , 0 ,0,0
       1       1
   301.7  306.85
       1       1
     301  306.85
Pier Skew, UpSta & Num, DnSta & Num=  ,5000, 2 ,5000, 2 , 0 , 0 , 0 ,0,0
       1       1
  299.35  306.85
       1       1
     298  306.85
Pier Skew, UpSta & Num, DnSta & Num=  ,5018.7, 2 ,5018.7, 2 , 0 , 0 , 0 ,0,0
       1       1
     304  306.85
       1       1
     301  306.85
Abutment Skew #Up #Dn= , 2 , 2
    4972    4979
  306.85  301.68
    4972    4979
  306.85  301.92
Abutment Skew #Up #Dn= , 2 , 2
  5021.1    5028
  304.23  306.85
    5021    5028
  302.12  306.85
BR Coef= 1 , 1 , 0 ,1.25, 0 ,,,0.8,0,2,0,
WSPro=,,,, 1 ,,,, 0 ,,,, 0 ,,,,-1 ,-1 ,-1 , 0 , 0 , 0 , 0 , 0
BC Design=,, 0 ,, 0 ,,,,,,
BC HTab HWMax=336.6
BC Use User HTab Curves=0
BC User HTab FreeFlow(D)= 0

Type RM Length L Ch R = 1 ,36026   ,526,526,526
BEGIN DESCRIPTION:
WC_Old Hilton RD (DS) - DS
END DESCRIPTION:
XS GIS Cut Line= 6
      1909304.26       844764.99      1909304.26       845060.17
       1909698.8         845530.      1909807.23       845629.39
       1909903.6       845686.61      1910343.28       845852.24
#Sta/Elev= 30
  4425.8  316.23  4441.9  314.71  4453.1  311.18    4468  310.24  4578.3  308.15
  4590.3  307.11    4647  306.97  4679.3  304.68  4688.6  302.53  4703.1  304.27
  4758.6  303.69  4784.3   301.6  4811.8  302.75  4840.4  301.38  4855.3  305.23
  4946.4  305.07  4994.3  300.77    4996  299.07    5004  299.07  5005.8  300.77
  5019.6  301.68    5038  305.37  5104.2  305.37  5387.2  310.05  5626.4  316.72
  5721.8  320.92  5783.4   321.5  5920.8  328.67  6029.3  332.93  6063.5  335.32
#Mann= 3 ,-1 , 0
  4425.8     .15       0  4994.3     .05       0  5005.8     .15       0
#XS Ineff= 2 , 0
       0    4900  305.64    5065       0     308
Permanent Ineff=
       F       F
Bank Sta=4994.3,5005.8
XS Rating Curve= 0 ,0
Exp/Cntr=0.5,0.3

Type RM Length L Ch R = 1 ,35500   ,591,591,591
BEGIN DESCRIPTION:
WATEREE CREEK 71.0
END DESCRIPTION:
XS GIS Cut Line= 3
      1908841.62       845479.36      1909266.01       845714.97
      1909639.65       845902.36
#Sta/Elev= 30
  4514.6  332.57  4565.3  327.85  4616.1  319.43    4662  306.73  4710.1  302.18
  4731.8  302.76  4742.3  301.49  4804.6  300.98  4837.9   302.7  4854.2   301.9
  4917.2  302.59  4930.9  301.67    4936  302.54  4978.7  303.07  4981.3     301
  4991.1  296.67    4998   295.4  4998.3   294.9    5002   295.4  5011.2   298.7
  5020.5  300.31    5029  300.12    5051  302.44  5179.1  303.04  5188.9  302.28
  5211.2  303.59  5254.7   303.8  5381.6  317.57  5393.4  316.67    5418  317.57
#Mann= 3 ,-1 , 0
  4514.6     .15       0    4998     .05       0    5002     .15       0
Bank Sta=4998,5002
XS Rating Curve= 0 ,0
Exp/Cntr=0.3,0.1

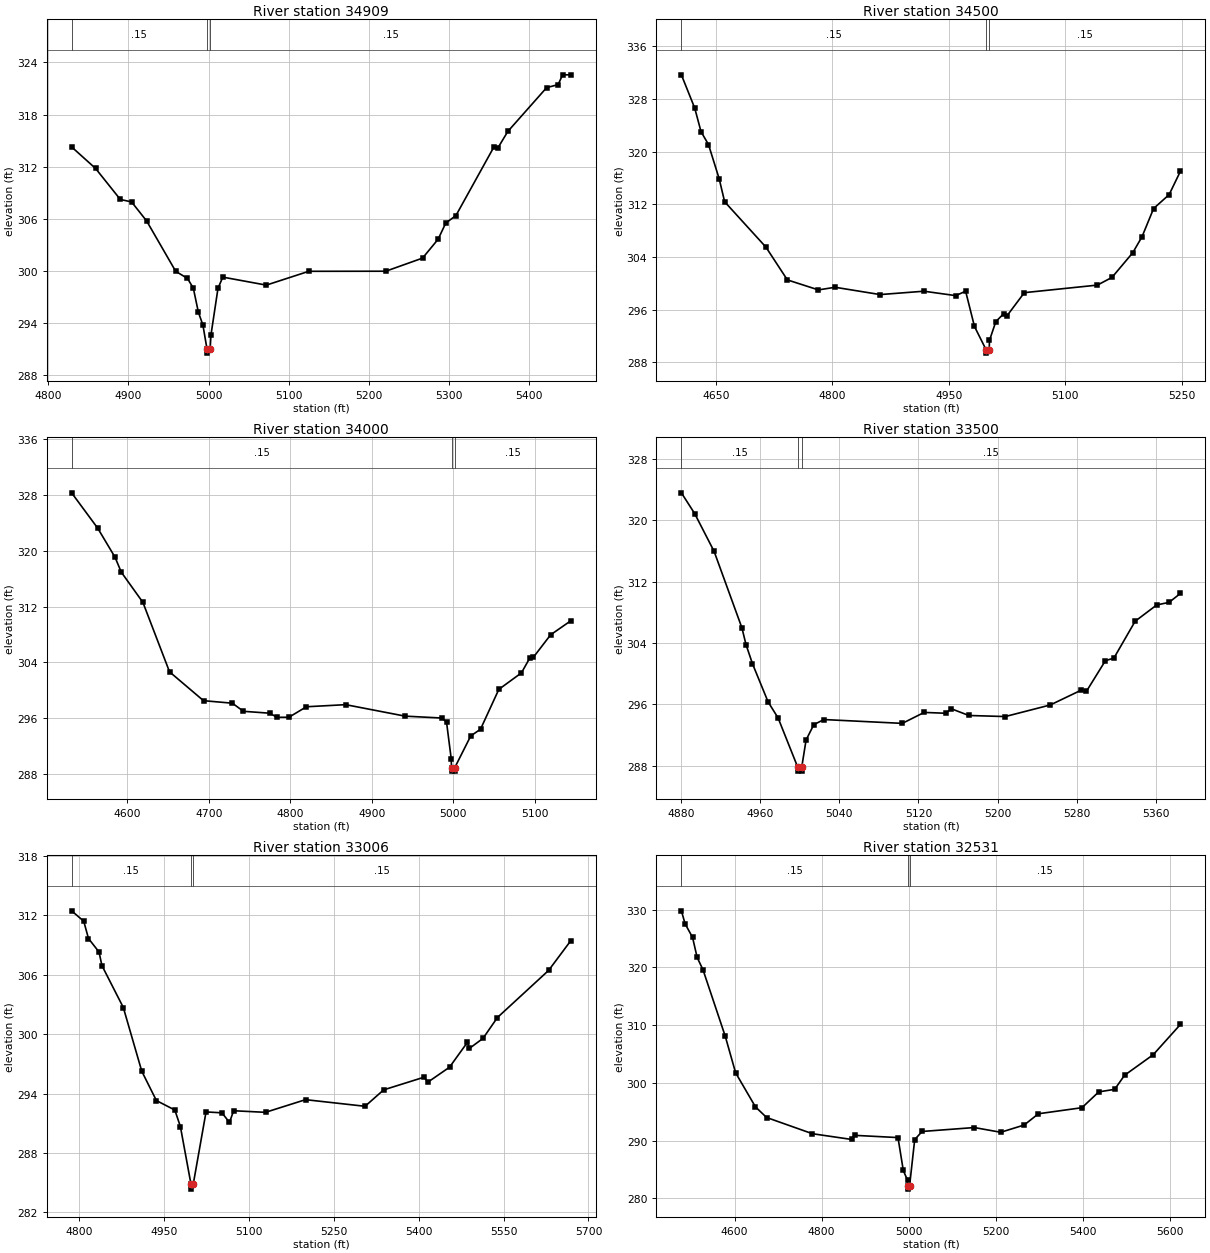
Type RM Length L Ch R = 1 ,34909   ,409,409,409
BEGIN DESCRIPTION:
WATEREE CREEK 70.0
END DESCRIPTION:
XS GIS Cut Line= 3
       1908930.3       846083.04      1909088.84       846146.86
      1909521.16       846278.76
#Sta/Elev= 30
  4829.1  314.27    4859  311.79  4889.9  308.22  4903.9  307.94  4922.7  305.75
    4959  299.95  4973.7  299.13    4981  298.01  4987.3  295.24    4993  293.75
    4998  291.03  4998.3  290.53    5002  291.03    5003  292.61  5011.8     298
  5017.8  299.28  5072.1  298.36  5125.1  299.95  5221.2  299.96  5267.1  301.47
  5286.5  303.64  5296.1  305.51  5308.7  306.36    5356  314.24  5360.9  314.12
  5373.5  316.05    5422   321.1  5436.3  321.44  5441.9  322.57    5452  322.57
#Mann= 3 ,-1 , 0
  4829.1     .15       0    4998     .05       0    5002     .15       0
Bank Sta=4998,5002
XS Rating Curve= 0 ,0
Exp/Cntr=0.3,0.1

Type RM Length L Ch R = 1 ,34500   ,500,500,500
BEGIN DESCRIPTION:
WATEREE CREEK 69.0
END DESCRIPTION:
XS GIS Cut Line= 3
      1908769.64       846410.46      1909145.72       846529.58
      1909391.12       846567.46
#Sta/Elev= 30
  4605.5  331.67  4622.7  326.61  4630.8  323.03  4640.4  321.08  4654.2  315.86
  4661.2  312.38  4714.4  305.48    4742   300.5    4782  298.98  4803.5  299.38
  4861.5  298.27  4917.9  298.78  4958.8  298.11  4971.6  298.78    4983  293.42
    4998  289.87  4998.3  289.37    5002  289.87  5002.3   291.3  5010.5  294.16
  5020.4  295.34  5024.6     295  5047.2  298.56  5141.3  299.71  5160.1  300.88
  5186.8  304.62  5198.8  307.06  5213.7  311.35  5233.7  313.46  5248.3  317.03
#Mann= 3 ,-1 , 0
  4605.5     .15       0    4998     .05       0    5002     .15       0
Bank Sta=4998,5002
XS Rating Curve= 0 ,0
Exp/Cntr=0.3,0.1

Type RM Length L Ch R = 1 ,34000   ,500,500,500
BEGIN DESCRIPTION:
WATEREE CREEK 68.0
END DESCRIPTION:
XS GIS Cut Line= 4
      1908756.57       846541.32       1908963.7       846724.46
      1909020.97       846907.53      1909029.12        847051.6
#Sta/Elev= 30
  4531.7  328.25  4563.7   323.2    4585  319.04  4592.6  316.92  4619.2  312.59
  4651.9  302.66  4693.6  298.54    4729  298.18  4742.6  297.02  4774.9  296.75
  4783.8  296.16  4798.4  296.17  4819.9  297.67  4868.1  297.97    4941  296.33
  4986.2  296.06  4991.9  295.47  4997.6  290.27    4998  288.97  4998.3  288.47
  5001.8  288.47    5002  288.97  5021.6   293.5  5033.6  294.46  5056.1  300.16
  5083.8  302.51  5093.9   304.6  5098.4  304.73  5119.6  307.95  5144.3  309.95
#Mann= 3 ,-1 , 0
  4531.7     .15       0    4998     .05       0    5002     .15       0
Bank Sta=4998,5002
XS Rating Curve= 0 ,0
Exp/Cntr=0.3,0.1

Type RM Length L Ch R = 1 ,33500   ,494,494,494
BEGIN DESCRIPTION:
WATEREE CREEK 67.0
END DESCRIPTION:
XS GIS Cut Line= 4
      1908507.99       847079.91      1908619.08       847124.49
      1908856.85       847132.23      1909002.91       847114.79
#Sta/Elev= 30
  4880.3   323.6  4893.8  320.88  4913.4  315.96  4941.5  305.99  4945.7  303.78
  4952.2   301.3    4968  296.32  4978.1  294.23    4998  287.79  4998.3  287.29
  5001.8  287.29    5002  287.79  5006.4  291.35  5014.2  293.35  5024.4  294.02
  5103.7  293.52  5125.8  294.95  5147.5  294.84  5153.4  295.42    5171  294.55
  5207.8  294.41  5253.3  295.92  5284.4  297.84  5289.9   297.7  5309.1   301.7
  5317.7  302.04  5339.2  306.85    5361  308.97  5373.5  309.31    5385  310.48
#Mann= 3 ,-1 , 0
  4880.3     .15       0    4998     .05       0    5002     .15       0
Bank Sta=4998,5002
XS Rating Curve= 0 ,0
Exp/Cntr=0.3,0.1

Type RM Length L Ch R = 1 ,33006   ,475,475,475
BEGIN DESCRIPTION:
WATEREE CREEK 66.0
END DESCRIPTION:
XS GIS Cut Line= 4
      1908383.65       847679.57      1908490.51       847611.96
      1908793.61         847540.       1909157.8       847287.04
#Sta/Elev= 30
  4787.2  312.47  4808.6  311.42    4817  309.67  4835.6  308.31  4840.7  306.94
  4878.5   302.7  4911.1  296.26  4936.9   293.3  4969.5  292.34  4979.3  290.67
    4998  284.85  4998.3  284.35    5002  284.85  5024.6  292.15  5052.7  292.06
    5066  291.09  5073.3  292.27  5129.6  292.11  5200.3  293.39  5305.4  292.72
  5338.3  294.38  5409.7  295.66  5416.4  295.16  5454.6  296.67  5486.3  299.19
  5489.5  298.56  5513.7  299.58  5539.2  301.69  5629.6  306.45  5668.6  309.44
#Mann= 3 ,-1 , 0
  4787.2     .15       0    4998     .05       0    5002     .15       0
Bank Sta=4998,5002
XS Rating Curve= 0 ,0
Exp/Cntr=0.3,0.1

Type RM Length L Ch R = 1 ,32531   ,469,469,469
BEGIN DESCRIPTION:
WATEREE CREEK 65.0
END DESCRIPTION:
XS GIS Cut Line= 4
      1908592.97       848209.47      1908784.89         848035.
      1908867.75        847529.1      1909170.87       847308.85
#Sta/Elev= 30
  4477.8  329.81  4486.3  327.57  4503.5   325.2    4514  321.74  4527.6  319.57
  4578.6  308.08  4602.4  301.75    4648  295.84  4673.6     294  4778.9  291.19
  4868.7   290.2  4875.8  290.91  4975.5  290.52  4987.7  284.82  4997.4  283.13
    4998  282.09  4998.3  281.59    5002  282.09  5013.9  290.18  5030.9  291.58
  5150.9  292.26  5211.6  291.44  5265.4   292.7  5298.2  294.65  5398.2   295.7
  5436.8  298.44  5473.3  298.88  5496.1  301.32  5561.9  304.88  5624.5  310.13
#Mann= 3 ,-1 , 0
  4477.8     .15       0    4998     .05       0    5002     .15       0
Bank Sta=4998,5002
XS Rating Curve= 0 ,0
Exp/Cntr=0.3,0.1