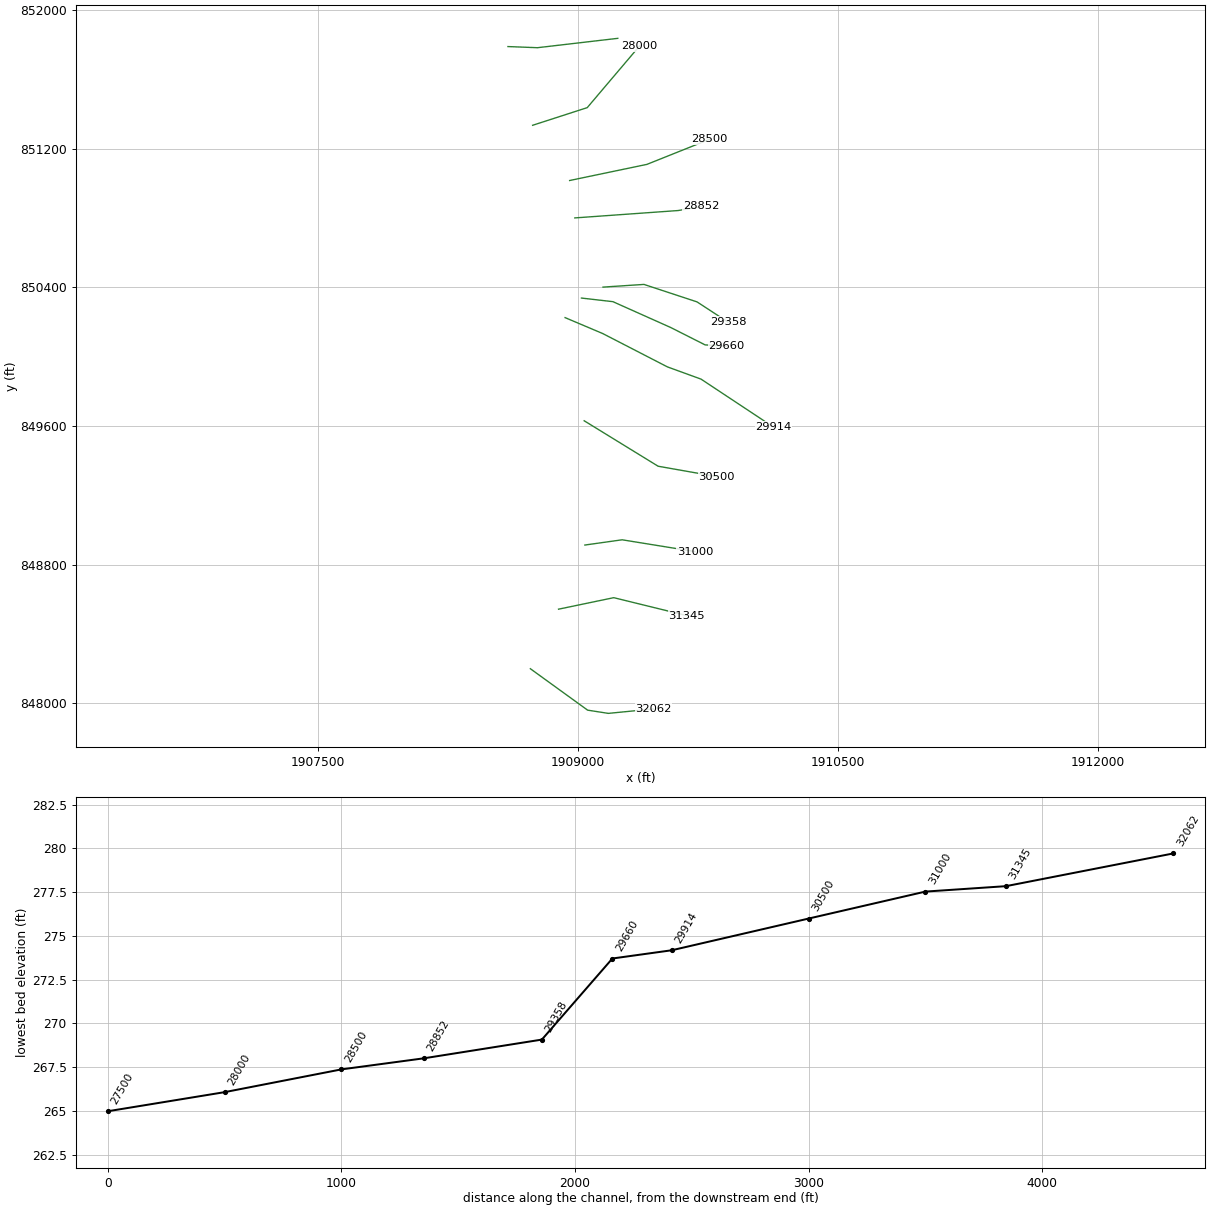
HEC-RAS study WATEREE CREEK.prj: WATEREE CREEK Limited Detail Study

--- WATEREE CREEK.g04 (geometry) --- (continued)

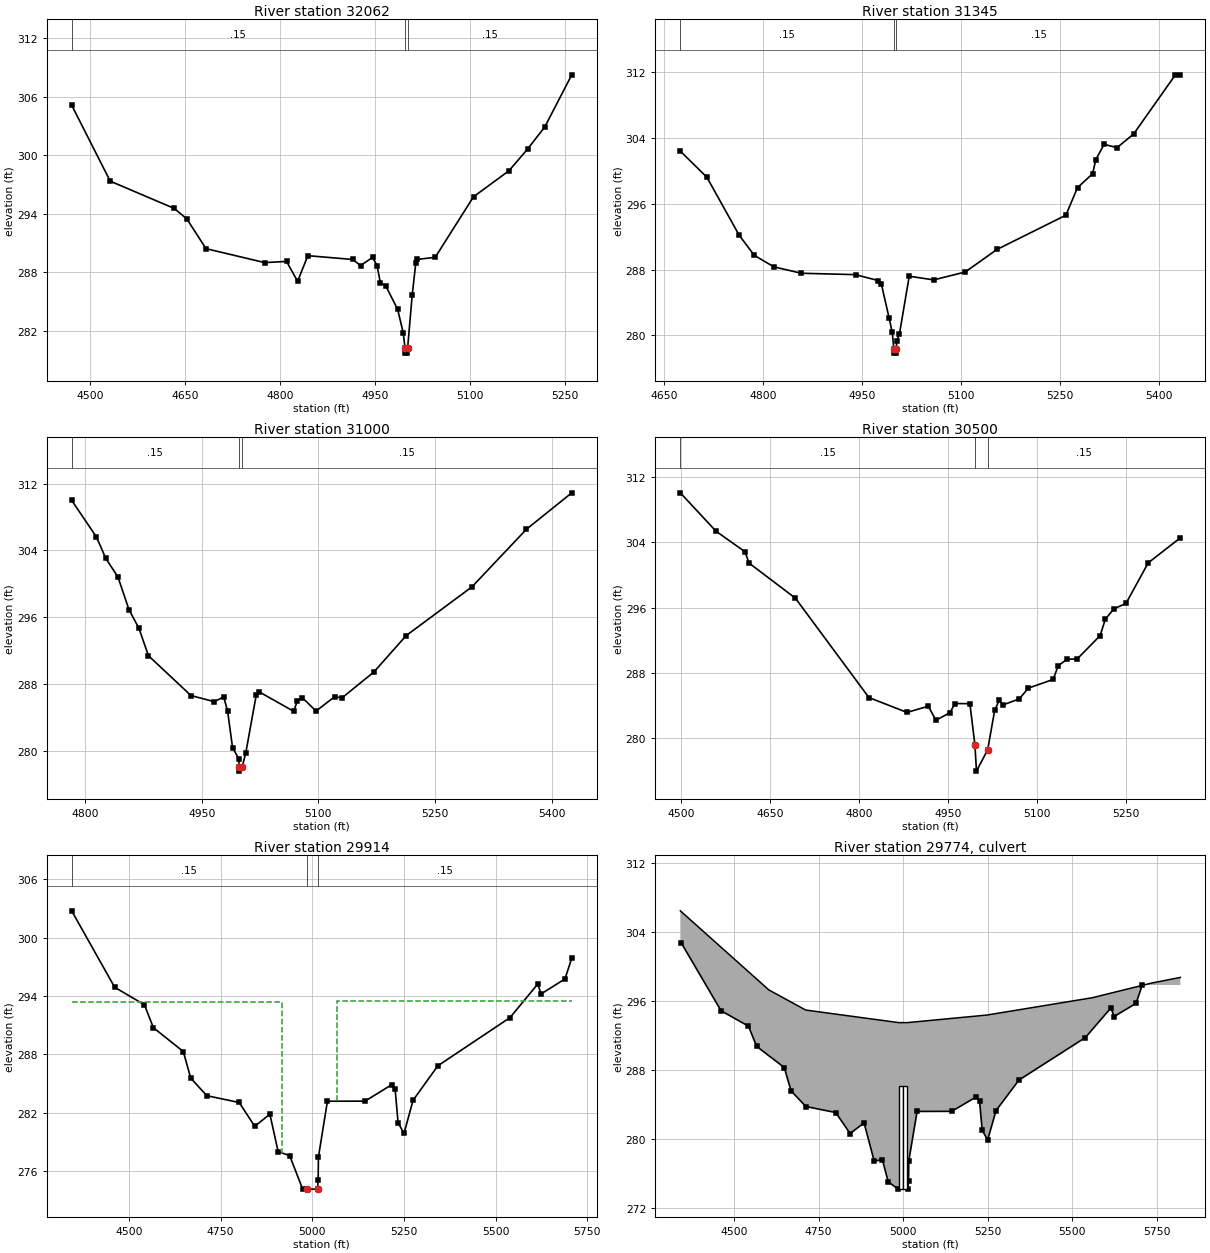
Type RM Length L Ch R = 1 ,32062   ,717,717,717
BEGIN DESCRIPTION:
WATEREE CREEK 64.0
END DESCRIPTION:
XS GIS Cut Line= 4
      1908724.94       848198.82       1909055.2        847959.9
      1909174.83       847941.21      1909434.88        847966.8
#Sta/Elev= 30
  4471.3  305.13  4532.2  297.34  4633.1  294.55  4653.1  293.48  4683.5  290.42
  4776.3  288.99  4810.8  289.11  4828.2  287.07  4844.4   289.7  4915.4  289.31
  4927.6  288.69  4946.7  289.52  4953.7  288.68  4959.1  286.87  4967.2  286.64
  4986.3  284.19    4995  281.81    4998  280.21  4998.3  279.71  5001.8  279.71
    5002  280.21  5009.3   285.7    5015  288.99  5017.4  289.32  5045.6  289.53
  5106.1  295.74  5162.2  298.41    5192  300.67  5218.7   302.9  5261.3  308.24
#Mann= 3 ,-1 , 0
  4471.3     .15       0    4998     .05       0    5002     .15       0
Bank Sta=4998,5002
XS Rating Curve= 0 ,0
Exp/Cntr=0.3,0.1

Type RM Length L Ch R = 1 ,31345   ,345,345,345
BEGIN DESCRIPTION:
WATEREE CREEK 63.0
END DESCRIPTION:
XS GIS Cut Line= 3
      1908887.63       848542.51      1909206.07       848608.95
      1909625.52         848506.
#Sta/Elev= 30
  4674.7  302.39  4714.9  299.22  4763.6   292.2  4786.6  289.73  4816.3  288.33
  4857.8  287.55    4940  287.38  4974.4  286.66  4979.1  286.24  4990.9  282.09
  4995.6  280.35    4998  278.34  4998.3  277.84  5001.8  277.84    5002  278.34
  5002.2   279.3  5006.4  280.15  5021.3  287.19  5058.3  286.74    5106   287.7
  5154.1  290.44  5258.5  294.61  5276.1  297.96    5299  299.65  5303.7  301.35
  5316.4  303.22    5336  302.82  5361.1  304.48  5424.3  311.67  5431.9  311.66
#Mann= 3 ,-1 , 0
  4674.7     .15       0    4998     .05       0    5002     .15       0
Bank Sta=4998,5002
XS Rating Curve= 0 ,0
Exp/Cntr=0.3,0.1

Type RM Length L Ch R = 1 ,31000   ,500,500,500
BEGIN DESCRIPTION:
WATEREE CREEK 62.0
END DESCRIPTION:
XS GIS Cut Line= 3
      1909039.44       848912.69      1909254.52       848942.98
      1909674.96       848875.01
#Sta/Elev= 30
  4782.8  309.99  4814.5  305.62  4826.7  303.03  4842.3   300.8  4856.5  296.89
  4869.4  294.63  4881.5  291.37  4936.2  286.59    4966  285.86  4978.3  286.42
  4983.3  284.74  4989.7  280.35  4997.9  278.97    4998  278.03  4998.3  277.53
    5002  278.03  5006.7  279.71  5020.1  286.63  5023.4  287.06  5068.3   284.7
    5073  285.95  5079.5  286.33  5097.1  284.73  5120.9  286.45  5130.4  286.31
  5171.3   289.4    5213  293.78  5297.6  299.62  5367.6  306.52  5425.9  310.89
#Mann= 3 ,-1 , 0
  4782.8     .15       0    4998     .05       0    5002     .15       0
Bank Sta=4998,5002
XS Rating Curve= 0 ,0
Exp/Cntr=0.3,0.1

Type RM Length L Ch R = 1 ,30500   ,586,586,586
BEGIN DESCRIPTION:
WATEREE CREEK 61.0
END DESCRIPTION:
XS GIS Cut Line= 3
      1909035.56       849629.85      1909462.29       849367.55
      1909799.19       849308.11
#Sta/Elev= 30
  4499.1  310.03  4559.3  305.33  4608.1  302.82  4614.9  301.44  4693.1  297.14
    4817  284.99  4881.2  283.17  4917.1  283.93  4929.9  282.21  4953.6  283.14
    4962  284.26  4987.2  284.24  4995.7   279.2  4998.3  275.99  5017.2   278.6
  5029.1  283.46  5036.9  284.68  5042.4  284.07  5070.6  284.83  5085.6  286.14
  5127.5   287.2  5136.2  288.89  5151.4  289.68    5168   289.7  5206.7  292.56
  5215.6  294.58  5230.1  295.85  5250.3   296.5  5287.9  301.47  5342.1  304.53
#Mann= 3 ,-1 , 0
  4499.1     .15       0  4995.7     .05       0  5017.2     .15       0
Bank Sta=4995.7,5017.2
XS Rating Curve= 0 ,0
Exp/Cntr=0.5,0.3

Type RM Length L Ch R = 1 ,29914   ,254,254,254
BEGIN DESCRIPTION:
WC_I-26 - US
END DESCRIPTION:
XS GIS Cut Line= 5
      1908925.36        850225.2      1909142.71       850133.21
      1909515.74        849940.9      1909710.07       849870.21
      1910127.52       849593.91
#Sta/Elev= 30
  4344.3  302.74  4461.6  294.89  4542.7   293.1  4566.9  290.75  4648.6   288.3
  4668.6  285.59  4712.5  283.77  4800.9  283.07  4843.3  280.63  4884.6  281.87
    4907  278.04  4938.6  277.61  4973.9  274.18  4985.6  274.18  5014.4  274.18
  5016.2  275.16  5016.9  277.47  5041.4   283.2  5143.9  283.21  5216.4  284.89
    5226  284.43    5234     281  5250.1  279.89  5274.9   283.3  5342.5  286.84
  5539.1  291.78  5614.8  295.23  5623.8  294.21  5688.9  295.75  5707.4  297.88
#Mann= 3 ,-1 , 0
  4344.3     .15       0  4985.6     .05       0  5014.4     .15       0
#XS Ineff= 2 , 0
       0    4917  293.41  5066.4       0  293.44
Permanent Ineff=
       F       F
Bank Sta=4985.6,5014.4
XS Rating Curve= 0 ,0
Exp/Cntr=0.5,0.3

Type RM Length L Ch R = 2 ,29774   ,,,
BEGIN DESCRIPTION:
WC_I-26 - TOR
Structure ID: lds 17
Approximate Survey Structure
END DESCRIPTION:
Bridge Culvert--1,0,-1,-1, 0
Deck Dist Width WeirC Skew NumUp NumDn MinLoCord MaxHiCord MaxSubmerge Is_Ogee
80,120,3,0, 9, 9, , , 0.95, 0, 1,1,,
  4341.2  4602.9    4712  4987.5  5012.5  5247.6  5559.4  5734.5  5820.1
  306.49  297.31  294.97  293.51  293.51  294.39   296.4   298.1  298.76
  250.91  250.91  250.91  250.91  250.91  250.91  250.91  250.91  250.91
  4341.2  4602.9    4712  4987.5  5012.5  5247.6  5559.4  5734.5  5820.1
  306.49  297.31  294.97  293.51  293.51  294.39   296.4   298.1  298.76
  250.31  250.31  250.31  250.31  250.31  250.31  250.31  250.31  250.31
BR Coef= 1 , 1 , 0 ,1.25, 0 ,,,0.8,0,2,0,
WSPro=,,,, 1 ,,,, 0 ,,,, 0 ,,,,-1 ,-1 ,-1 , 0 , 0 , 0 , 0 , 0
Culvert=2,12,12,130,0.012,0.4,1,8,1,274.18,4993.5,273.71,4993.5,Culvert #1  , 0 ,80
Culvert Bottom n=0.012
Culvert=2,12,12,130,0.012,0.4,1,8,1,274.18,5006.5,273.71,5006.5,Culvert #2  , 0 ,80
Culvert Bottom n=0.012
BR U #Sta/Elev= 30
  4344.3  302.74  4461.6  294.89  4542.7   293.1  4566.9  290.75  4648.6   288.3
  4668.6  285.59  4712.5  283.77  4800.9  283.07  4843.3  280.63  4884.6  281.87
  4914.6  277.42  4938.6  277.61    4956  275.02  4985.6  274.18  5014.4  274.18
  5016.2  275.16  5016.9  277.47  5041.4   283.2  5143.9  283.21  5216.4  284.89
    5226  284.43    5234     281  5250.1  279.89  5274.9   283.3  5342.5  286.84
  5539.1  291.78  5614.8  295.23  5623.8  294.21  5688.9  295.75  5707.4  297.88
BR U #Mann= 3
  4344.3     .15  4985.6     .05  5014.4     .15
BR D #Sta/Elev= 30
    4452  302.62  4571.6   296.1    4636  287.55  4694.8  285.22    4703  283.97
    4717  284.55  4723.6  283.22  4761.2   283.8  4774.2  282.77  4792.3  283.53
  4841.4  282.53  4894.4  279.35  4918.1  279.37  4926.6   280.4    4948  280.87
  4958.4  279.97  4966.9  280.34  4983.6  275.33  4983.8  274.56  4985.6  273.71
  5014.4  273.71  5022.4  276.53  5035.5  277.21  5043.4  279.49  5070.7  282.62
  5188.5  287.71  5210.5  292.03  5227.1   293.2  5311.2  304.74  5346.7  308.04
BR D #Mann= 3
    4452     .15  4985.6     .05  5014.4     .15
BC Design=,, 0 ,, 0 ,,,,,,
BC HTab HWMax=302.74
BC Use User HTab Curves=0
BC User HTab FreeFlow(D)= 0

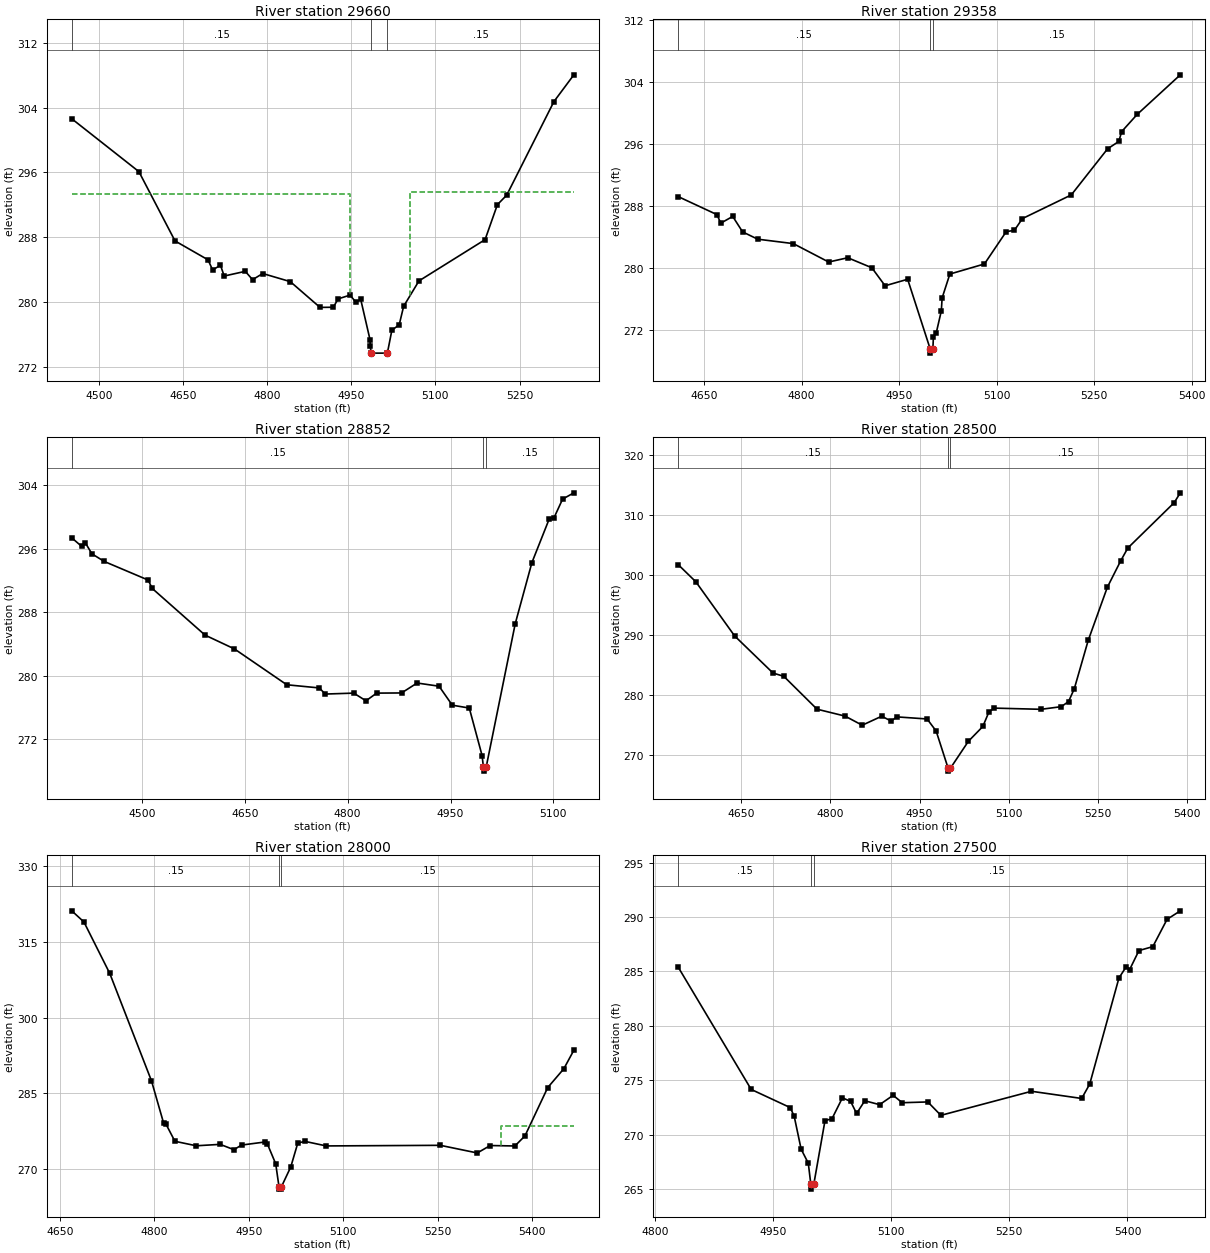
Type RM Length L Ch R = 1 ,29660   ,302,302,302
BEGIN DESCRIPTION:
WC_I-26 - DS
END DESCRIPTION:
XS GIS Cut Line= 5
      1909019.78       850338.11      1909201.35       850317.25
       1909534.8       850168.22      1909733.33       850067.92
      1909857.36       850060.17
#Sta/Elev= 30
    4452  302.62  4571.6   296.1    4636  287.55  4694.8  285.22    4703  283.97
    4717  284.55  4723.6  283.22  4761.2   283.8  4774.2  282.77  4792.3  283.53
  4841.4  282.53  4894.4  279.35  4918.1  279.37  4926.6   280.4    4948  280.87
  4958.4  279.97  4966.9  280.34  4983.6  275.33  4983.8  274.56  4985.6  273.71
  5014.4  273.71  5022.4  276.53  5035.5  277.21  5043.4  279.49  5070.7  282.62
  5188.5  287.71  5210.5  292.03  5227.1   293.2  5311.2  304.74  5346.7  308.04
#Mann= 3 ,-1 , 0
    4452     .15       0  4985.6     .05       0  5014.4     .15       0
#XS Ineff= 2 , 0
       0    4947  293.37    5054       0  293.57
Permanent Ineff=
       F       F
Bank Sta=4985.6,5014.4
XS Rating Curve= 0 ,0
Exp/Cntr=0.5,0.3

Type RM Length L Ch R = 1 ,29358   ,506,506,506
BEGIN DESCRIPTION:
WATEREE CREEK 59.0
END DESCRIPTION:
XS GIS Cut Line= 4
      1909144.09       850401.31      1909380.56       850416.82
      1909686.81       850316.02      1909865.15       850199.72
#Sta/Elev= 30
  4610.3  289.23  4669.9  286.91  4675.7  285.81  4694.1  286.68  4709.3  284.69
  4732.5  283.75  4787.3  283.18  4841.7  280.81  4871.1  281.36  4908.1  280.07
  4928.5  277.75  4963.2  278.59    4998  269.58  4998.3  269.08    5002  269.58
  5002.8  271.22  5007.1  271.66    5015  274.52  5016.2  276.18  5028.1  279.26
  5081.3  280.56  5114.9  284.73  5127.3  284.88  5139.7   286.4  5214.9  289.45
  5270.7  295.38  5287.9  296.33  5292.5  297.61  5316.2  299.81  5382.6  304.91
#Mann= 3 ,-1 , 0
  4610.3     .15       0    4998     .05       0    5002     .15       0
Bank Sta=4998,5002
XS Rating Curve= 0 ,0
Exp/Cntr=0.3,0.1

Type RM Length L Ch R = 1 ,28852   ,352,352,352
BEGIN DESCRIPTION:
WATEREE CREEK 58.0
END DESCRIPTION:
XS GIS Cut Line= 3
      1908981.29        850800.6      1909578.26       850843.24
      1909710.03        850866.5
#Sta/Elev= 30
  4397.6  297.37  4412.2  296.29  4417.5  296.73    4427  295.36    4445   294.4
    4509  292.06  4514.9  291.01    4592  285.13  4634.9  283.39  4711.2  278.88
  4758.8  278.48  4767.1  277.71  4808.9  277.83  4826.7  276.86  4842.3  277.83
  4878.6  277.85  4901.3   279.1  4933.3   278.7  4952.6  276.31  4977.4  275.95
  4996.1  269.96    4998  268.51  4998.3  268.01    5002  268.51  5044.4  286.56
  5068.7  294.25  5094.2   299.8  5100.8  299.87  5113.5  302.25  5129.9  303.04
#Mann= 3 ,-1 , 0
  4397.6     .15       0    4998     .05       0    5002     .15       0
#XS Ineff= 2 , 0
       0  4901.3   279.1               0
Permanent Ineff=
       F       F
Bank Sta=4998,5002
XS Rating Curve= 0 ,0
Exp/Cntr=0.3,0.1

Type RM Length L Ch R = 1 ,28500   ,500,500,500
BEGIN DESCRIPTION:
WATEREE CREEK 57.0
END DESCRIPTION:
XS GIS Cut Line= 3
      1908951.55       851016.46      1909397.73       851109.63
      1909758.49        851253.8
#Sta/Elev= 30
  4544.2  301.78  4573.8  298.93    4639  289.91  4703.6  283.72  4721.7  283.18
  4777.6   277.7  4824.7  276.55  4853.6  275.03  4886.4  276.53  4902.4  275.71
  4911.5  276.42  4962.7  276.07  4977.9  274.06    4998  267.88  4998.3  267.38
    5002  267.88  5032.1  272.35  5056.4  274.82  5066.8  277.27  5075.3  277.88
  5154.3  277.68  5188.4  278.12  5200.6  278.98  5210.3  281.13  5233.6  289.16
  5265.8  298.02  5288.1  302.39  5300.2  304.55  5378.1   312.1  5388.5  313.75
#Mann= 3 ,-1 , 0
  4544.2     .15       0    4998     .05       0    5002     .15       0
Bank Sta=4998,5002
XS Rating Curve= 0 ,0
Exp/Cntr=0.3,0.1

Type RM Length L Ch R = 1 ,28000   ,500,500,500
BEGIN DESCRIPTION:
WATEREE CREEK 56.0
END DESCRIPTION:
XS GIS Cut Line= 3
       1908737.9       851335.18      1909053.13       851437.09
      1909354.99        851792.9
#Sta/Elev= 30
  4668.7   321.1    4688   318.9  4729.1  308.72  4795.4  287.48  4814.8  279.07
    4818  279.03  4832.6  275.54  4866.5  274.65  4904.5  274.93  4926.4  273.88
  4938.5  274.79  4975.8   275.4  4979.7  274.97  4992.8  271.09    4998  266.58
  4998.3  266.08  5001.8  266.08    5002  266.58  5016.7  270.46  5027.9  275.19
  5039.3  275.52  5073.1  274.62  5254.4  274.74  5313.1  273.23  5333.7   274.7
  5372.9  274.61  5388.9   276.6  5425.1  286.16  5450.7  289.88  5466.6  293.54
#Mann= 3 ,-1 , 0
  4668.7     .15       0    4998     .05       0    5002     .15       0
#XS Ineff= 2 , 0
       0                  5350.7       0   278.5
Permanent Ineff=
       F       F
Bank Sta=4998,5002
XS Rating Curve= 0 ,0
Exp/Cntr=0.3,0.1

Type RM Length L Ch R = 1 ,27500   ,600,600,600
BEGIN DESCRIPTION:
WATEREE CREEK 55.0
END DESCRIPTION:
XS GIS Cut Line= 3
      1908595.49       851789.54      1908765.56       851782.91
      1909229.52       851837.01
#Sta/Elev= 30
  4829.8  285.38  4922.4  274.15    4972  272.48    4977  271.68  4985.8  268.66
  4994.9  267.37    4998  265.49  4998.3  264.99    5002  265.49  5016.1  271.29
  5024.9  271.45  5038.2  273.38  5048.6  273.05  5056.2  271.94  5066.6  273.11
  5085.4  272.75  5102.6  273.61  5114.1  272.93  5146.6     273  5163.2  271.77
  5278.2  273.98  5341.9  273.32  5352.1  274.64  5389.2  284.39  5398.6  285.44
  5402.7  285.15  5414.6  286.91  5432.2  287.27  5450.3  289.78  5467.1  290.56
#Mann= 3 ,-1 , 0
  4829.8     .15       0    4998     .05       0    5002     .15       0
Bank Sta=4998,5002
XS Rating Curve= 0 ,0
Exp/Cntr=0.5,0.3