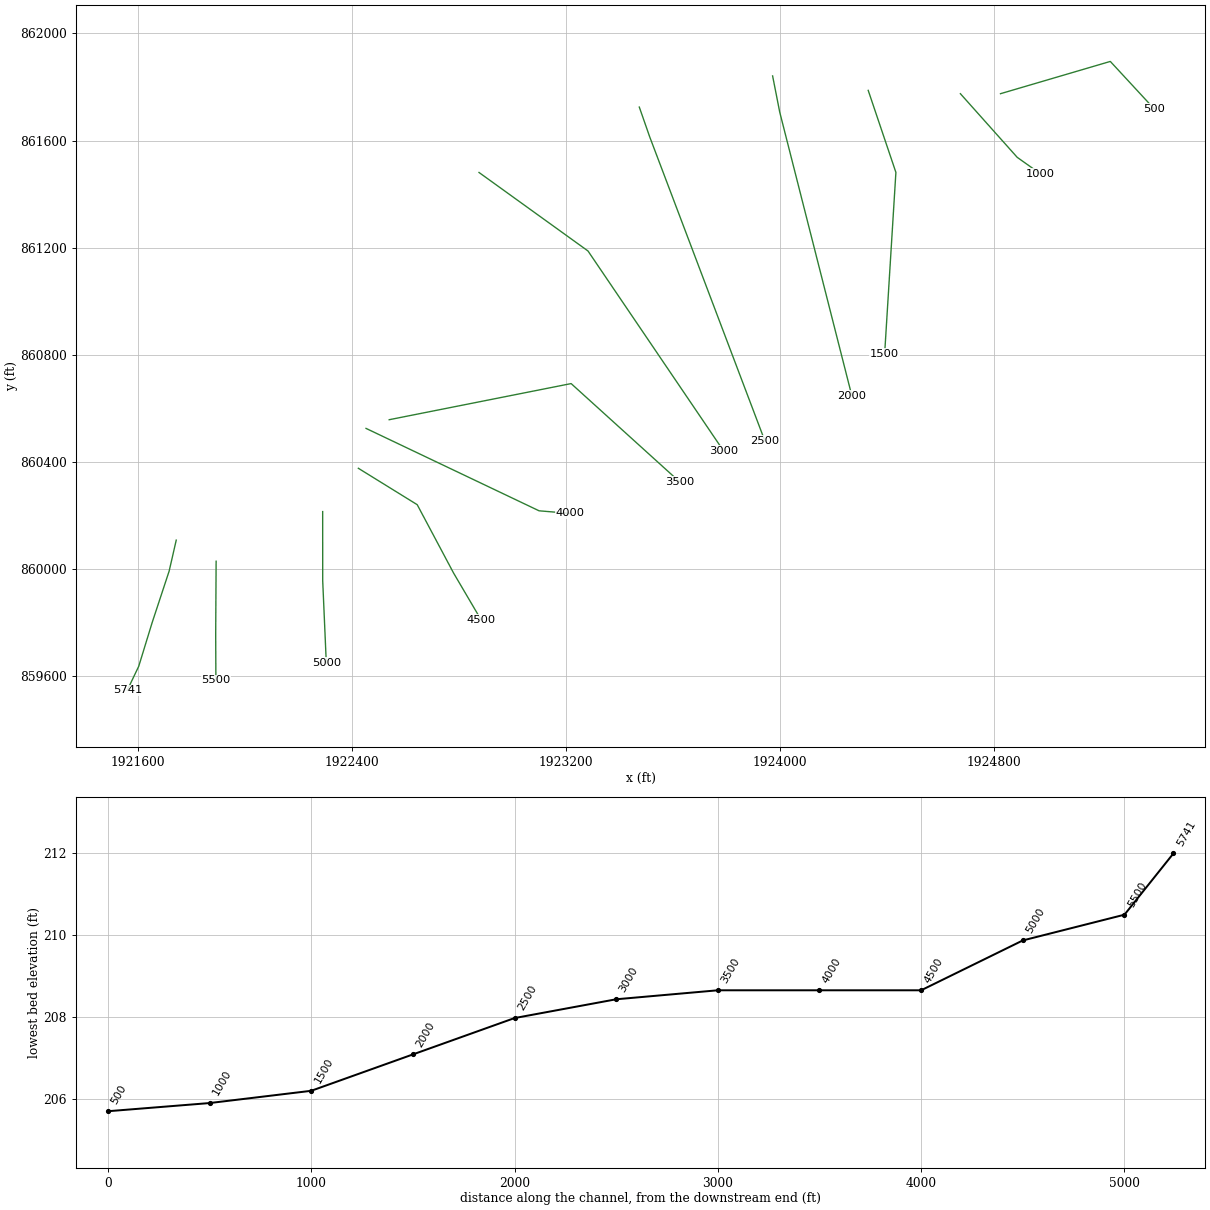
HEC-RAS study WATEREE CREEK.prj: WATEREE CREEK Limited Detail Study

--- WATEREE CREEK.g04 (geometry) --- (continued)

Type RM Length L Ch R = 3 ,5800    ,,,
BEGIN DESCRIPTION:
WC_Wash Lever Rd - TOR
Structure ID: lds 23
Approximate Survey Structure
END DESCRIPTION:
Bridge Culvert--1,0,-1,-1, 0
Deck Dist Width WeirC Skew NumUp NumDn MinLoCord MaxHiCord MaxSubmerge Is_Ogee
38,36,3,0, 15, 15, , , 0.95, 0, 1,1,,
  4730.1  4755.5  4822.2  4888.7    4909    4909    5091    5091  5323.3    5324
  5326.5  5329.8  5333.1  5334.2  5337.5
  245.93  244.95  242.28  237.45  237.45  237.45  237.45  237.45  237.45  237.48
  237.54  237.68  237.79  237.83  237.95
  192.25  192.25  192.25  192.25  192.25  235.75  235.75  192.25  192.25  192.25
  192.25  192.25  192.25  192.25  192.25
  4730.1  4755.5  4822.2  4888.7    4909    4909    5091    5091  5323.3    5324
  5326.5  5329.8  5333.1  5334.2  5337.5
  245.93  244.95  242.28  237.45  237.45  237.45  237.45  237.45  237.45  237.48
  237.54  237.68  237.79  237.83  237.95
  192.25  192.25  192.25  192.25  192.25  235.75  235.75  192.25  192.25  192.25
  192.25  192.25  192.25  192.25  192.25
Pier Skew, UpSta & Num, DnSta & Num=  ,4927.2, 2 ,4927.2, 2 , 0 , 0 , 0 ,0,0
       1       1
  228.53  235.75
       1       1
  221.51  235.75
Pier Skew, UpSta & Num, DnSta & Num=  ,4963.6, 2 ,4963.6, 2 , 0 , 0 , 0 ,0,0
       1       1
  224.25  235.75
       1       1
  214.94  235.75
Pier Skew, UpSta & Num, DnSta & Num=  ,5000, 2 ,5000, 2 , 0 , 0 , 0 ,0,0
       1       1
  212.25  235.75
       1       1
     212  235.75
Pier Skew, UpSta & Num, DnSta & Num=  ,5036.4, 2 ,5036.4, 2 , 0 , 0 , 0 ,0,0
       1       1
  218.72  235.75
       1       1
  218.74  235.75
Pier Skew, UpSta & Num, DnSta & Num=  ,5072.8, 2 ,5072.8, 2 , 0 , 0 , 0 ,0,0
       1       1
  221.28  235.75
       1       1
  220.71  235.75
Abutment Skew #Up #Dn= , 2 , 2
    4909    4950
  235.75  226.23
    4909    4950
  235.75  217.67
Abutment Skew #Up #Dn= , 2 , 2
    5050    5091
  219.69  235.75
    5050    5091
  218.64  235.75
BR Coef= 1 , 1 , 0 ,1.25, 0 ,,,0.8,0,2,0,
WSPro=,,,, 1 ,,,, 0 ,,,, 0 ,,,,-1 ,-1 ,-1 , 0 , 0 , 0 , 0 , 0
BC Design=,, 0 ,, 0 ,,,,,,
BC HTab HWMax=254.86
BC Use User HTab Curves=0
BC User HTab FreeFlow(D)= 0

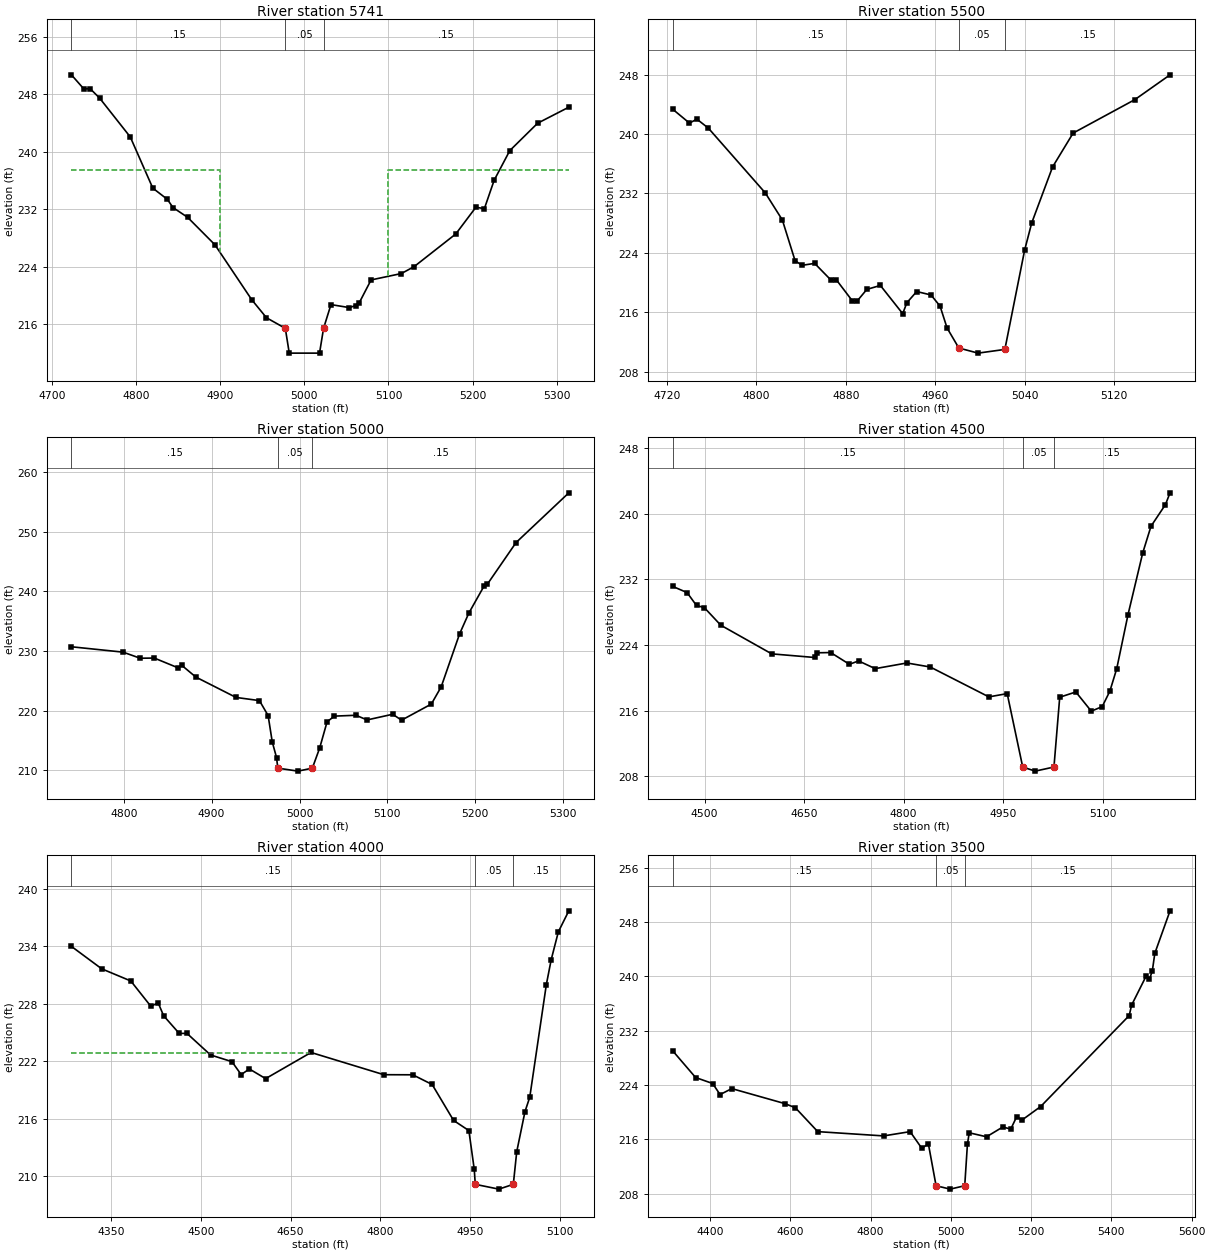
Type RM Length L Ch R = 1 ,5741    ,241,241,241
BEGIN DESCRIPTION:
WC_Wash Lever Rd - DS
END DESCRIPTION:
XS GIS Cut Line= 5
      1921744.38       860106.43      1921717.85       859990.72
      1921654.48       859798.75      1921604.16       859634.74
      1921561.31       859545.31
#Sta/Elev= 30
  4722.9  250.71  4737.6  248.76  4745.2  248.78  4756.4  247.48  4792.9  242.07
  4819.7  234.95    4837  233.39  4843.7  232.25  4861.1  230.89  4893.6  227.07
  4937.3  219.44  4954.9  216.92  4977.3  215.45    4982     212    5018     212
  5022.8  215.45  5031.6  218.75  5053.6  218.33  5060.9  218.62  5065.4  219.04
  5079.3  222.18  5115.3  223.07  5130.5  224.03  5180.1  228.58  5203.9  232.28
  5214.1  232.11  5225.7  236.05  5244.3  240.17  5277.4  243.98  5314.5  246.21
#Mann= 3 ,-1 , 0
  4722.9     .15       0  4977.3     .05       0  5022.8     .15       0
#XS Ineff= 2 , 0
       0    4900  237.45    5100       0  237.45
Permanent Ineff=
       F       F
Bank Sta=4977.3,5022.8
XS Rating Curve= 0 ,0
Exp/Cntr=0.5,0.3

Type RM Length L Ch R = 1 ,5500    ,500,500,500
BEGIN DESCRIPTION:
WATEREE CREEK 11.0
END DESCRIPTION:
XS GIS Cut Line= 3
      1921893.44       860027.65      1921891.81       859752.65
      1921892.58       859582.55
#Sta/Elev= 30
    4725  243.34  4740.1  241.46  4746.7     242    4757  240.78  4807.9  232.07
  4823.2  228.42  4834.6  222.93  4840.9  222.32  4852.1  222.58  4866.9   220.3
  4871.4  220.39  4885.7  217.56  4890.1  217.51  4898.8  219.08  4910.9  219.61
  4930.9  215.81  4934.6  217.28  4943.4  218.79  4956.2  218.33  4964.3  216.83
  4970.6  213.88  4981.1  211.19  4998.3   210.5  5022.3     211    5040  224.37
  5046.3  228.01    5065  235.56  5083.4  240.12  5138.6  244.62  5170.1  247.96
#Mann= 3 ,-1 , 0
    4725     .15       0  4981.1     .05       0  5022.3     .15       0
Bank Sta=4981.1,5022.3
XS Rating Curve= 0 ,0
Exp/Cntr=0.3,0.1

Type RM Length L Ch R = 1 ,5000    ,500,500,500
BEGIN DESCRIPTION:
WATEREE CREEK 10.0
END DESCRIPTION:
XS GIS Cut Line= 3
      1922291.64        860213.2       1922291.8        859953.7
      1922305.21        859647.6
#Sta/Elev= 30
  4740.5  230.71  4799.3  229.81  4818.7  228.79  4834.8  228.82  4861.7  227.19
  4865.9  227.62    4882  225.64  4927.8  222.22  4954.4  221.69  4964.3  219.18
    4969  214.76  4973.9  212.13  4975.3  210.37  4998.3  209.87  5014.6  210.37
  5022.9  213.72  5031.4  218.15  5039.8  219.09  5064.2  219.23  5076.9  218.45
    5106   219.4  5116.1  218.41    5150  221.11  5161.2     224  5182.1  232.86
  5192.7  236.37  5209.7  240.82  5213.6  241.17  5246.4  248.18  5306.4  256.51
#Mann= 3 ,-1 , 0
  4740.5     .15       0  4975.3     .05       0  5014.6     .15       0
Bank Sta=4975.3,5014.6
XS Rating Curve= 0 ,0
Exp/Cntr=0.3,0.1

Type RM Length L Ch R = 1 ,4500    ,500,500,500
BEGIN DESCRIPTION:
WATEREE CREEK 9.0
END DESCRIPTION:
XS GIS Cut Line= 4
        1922425.         860375.        1922645.       860238.92
      1922781.02       859983.24       1922883.2       859809.45
#Sta/Elev= 30
  4451.7  231.15  4473.5  230.39  4487.7  228.82  4499.5  228.56  4524.3  226.42
  4601.1  222.93  4665.6  222.49  4669.8  223.06    4690  223.09  4718.2  221.66
  4732.1  222.07  4757.1  221.13  4804.9  221.82  4840.1  221.33  4928.5  217.69
  4956.1  218.09  4979.5  209.15  4998.3  208.65  5026.6  209.15  5035.3  217.65
  5059.6  218.29  5082.9  215.95  5099.4  216.51  5110.9  218.39  5121.2  221.11
  5138.3  227.72  5160.4  235.21  5172.9  238.47  5194.7  241.11  5201.6  242.54
#Mann= 3 ,-1 , 0
  4451.7     .15       0  4979.5     .05       0  5026.6     .15       0
Bank Sta=4979.5,5026.6
XS Rating Curve= 0 ,0
Exp/Cntr=0.3,0.1

Type RM Length L Ch R = 1 ,4000    ,500,500,500
BEGIN DESCRIPTION:
WATEREE CREEK 8.0
END DESCRIPTION:
XS GIS Cut Line= 3
      1922453.69       860524.07       1923100.4       860216.08
       1923215.3       860206.44
#Sta/Elev= 30
  4283.7  233.98  4334.3  231.64    4383  230.37  4416.5  227.73  4428.7  228.09
  4437.9  226.74  4463.9   224.9  4476.9   224.9  4516.3  222.65  4552.1  221.95
  4567.5   220.6  4581.2  221.19  4608.4  220.18  4684.3  222.91  4806.1  220.59
  4854.4  220.58  4886.8  219.57  4922.6  215.82  4948.2  214.76  4957.2  210.71
  4958.9  209.15  4998.3  208.65  5022.5  209.15  5028.2  212.55    5042  216.74
    5050  218.24  5077.7  229.99  5085.9  232.61  5097.8   235.5  5115.3  237.69
#Mann= 3 ,-1 , 0
  4283.7     .15       0  4958.9     .05       0  5022.5     .15       0
#XS Ineff= 2 , 0
       0  4683.2   222.9               0
Permanent Ineff=
       F       F
Bank Sta=4958.9,5022.5
XS Rating Curve= 0 ,0
Exp/Cntr=0.3,0.1

Type RM Length L Ch R = 1 ,3500    ,500,500,500
BEGIN DESCRIPTION:
WATEREE CREEK 7.0
END DESCRIPTION:
XS GIS Cut Line= 3
       1922540.3       860556.53      1923220.22       860691.56
      1923625.01       860324.99
#Sta/Elev= 30
  4306.8  229.04  4364.1  225.09  4406.6  224.21    4425  222.58  4454.2  223.46
  4586.4  221.25  4612.6  220.64  4668.4  217.12  4832.5  216.49  4898.5  217.12
  4927.7  214.66    4944  215.33  4963.2  209.15  4998.3  208.65  5034.6  209.15
  5041.3  215.26  5045.8  216.95  5088.9  216.36  5129.3   217.8  5149.3   217.5
  5164.2  219.34  5177.1  218.82  5223.8  220.82  5444.4  234.22  5450.3  235.75
  5487.1   240.1  5494.8  239.56    5502  240.81  5508.2  243.39  5546.1  249.65
#Mann= 3 ,-1 , 0
  4306.8     .15       0  4963.2     .05       0  5034.6     .15       0
Bank Sta=4963.2,5034.6
XS Rating Curve= 0 ,0
Exp/Cntr=0.3,0.1

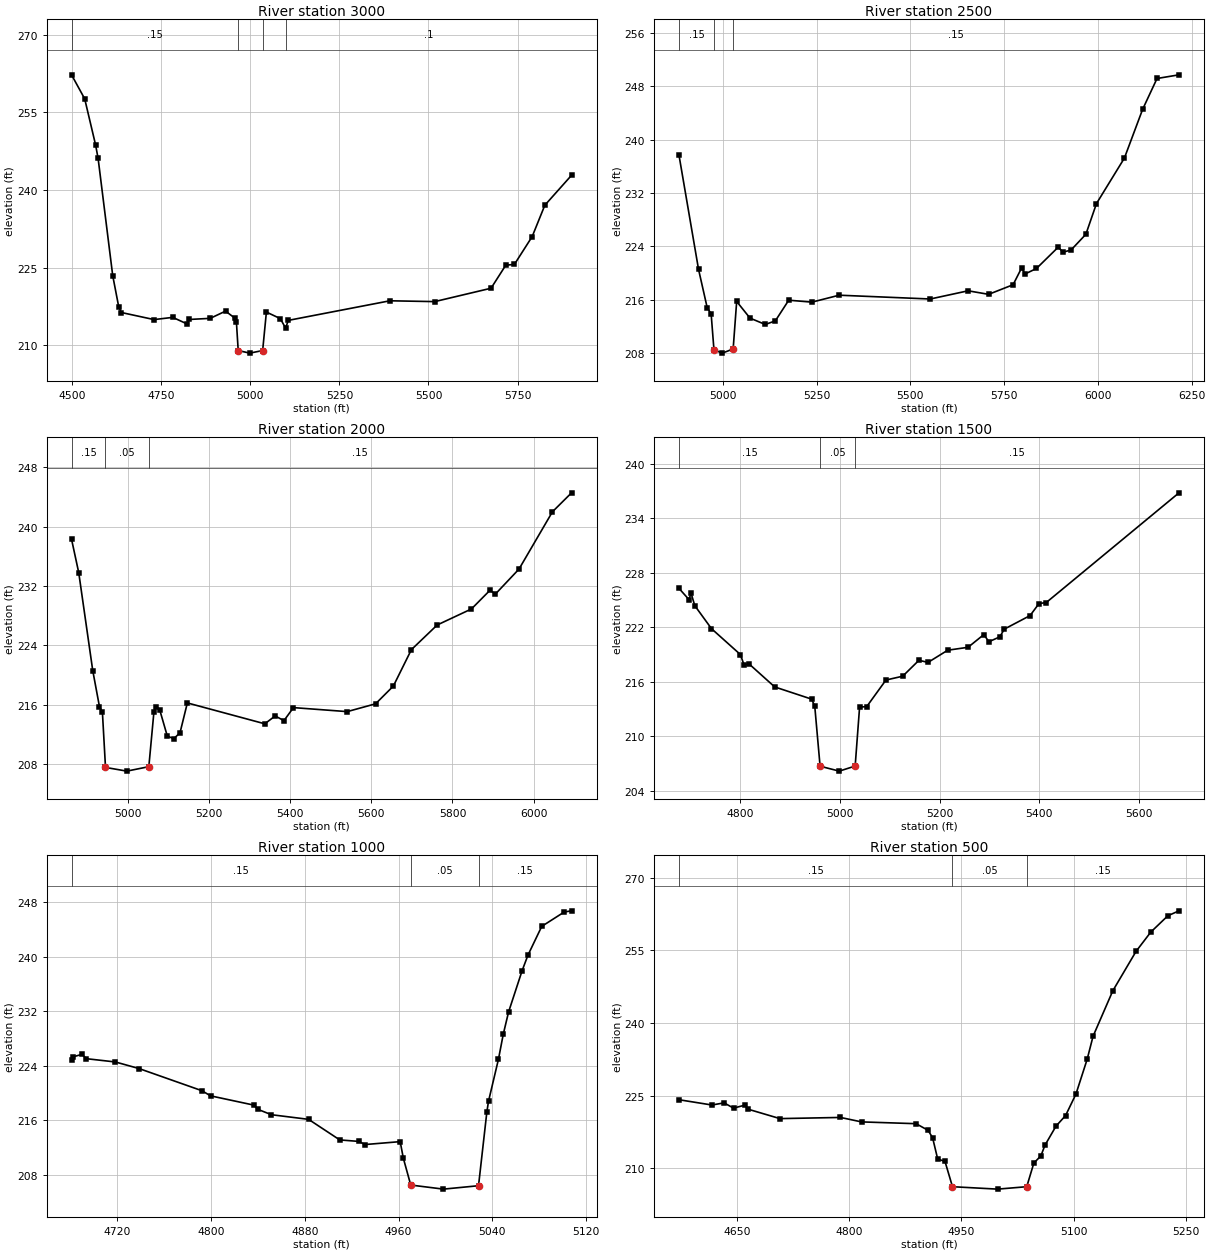
Type RM Length L Ch R = 1 ,3000    ,500,500,500
BEGIN DESCRIPTION:
WATEREE CREEK 6.0
END DESCRIPTION:
XS GIS Cut Line= 3
      1922875.96       861480.55       1923283.2       861187.19
      1923789.15       860441.06
#Sta/Elev= 30
  4498.1  262.29    4535  257.65  4565.7  248.69  4572.7   246.1  4613.7  223.42
  4630.7  217.33    4638  216.29  4729.8  214.92  4782.2  215.35    4823  214.06
  4826.6  214.94  4887.3  215.16  4930.4  216.56  4957.5  215.15  4960.9   214.4
  4965.9  208.93  4998.3  208.43  5034.5  208.93    5045  216.38    5084  215.11
  5098.9  213.29  5106.6  214.77  5391.7  218.56  5517.4   218.4  5675.6  220.99
  5716.9  225.45  5741.1   225.6  5791.1     231  5826.5  237.05  5901.5  242.85
#Mann= 4 ,-1 , 0
  4498.1     .15       0  4965.9     .05       0  5034.5     .15       0
  5098.9      .1       0
Bank Sta=4965.9,5034.5
XS Rating Curve= 0 ,0
Exp/Cntr=0.3,0.1

Type RM Length L Ch R = 1 ,2500    ,500,500,500
BEGIN DESCRIPTION:
WATEREE CREEK 5.0
END DESCRIPTION:
XS GIS Cut Line= 3
      1923475.01       861724.96      1923513.59       861614.51
      1923944.35       860477.14
#Sta/Elev= 30
    4883  237.66  4935.1  220.54  4958.3  214.76  4968.7  213.87  4976.2  208.47
  4998.3  207.97  5027.4  208.59  5036.8  215.72  5072.4  213.22  5113.1  212.27
  5139.9  212.81  5175.6  215.91  5237.5  215.62  5310.1  216.66    5553  216.09
  5653.9  217.32  5708.6  216.79  5773.8  218.23  5796.4  220.73    5806  219.85
  5836.2  220.67  5894.4  223.88  5906.6  223.11  5928.4  223.44  5967.9   225.8
  5996.1   230.4  6070.6  237.23  6119.2  244.54  6157.6  249.17  6216.2  249.72
#Mann= 3 ,-1 , 0
    4883     .15       0  4976.2     .05       0  5027.4     .15       0
Bank Sta=4976.2,5027.4
XS Rating Curve= 0 ,0
Exp/Cntr=0.3,0.1

Type RM Length L Ch R = 1 ,2000    ,500,500,500
BEGIN DESCRIPTION:
WATEREE CREEK 4.0
END DESCRIPTION:
XS GIS Cut Line= 3
      1923973.23       861841.45      1923999.81       861706.24
       1924269.2       860646.75
#Sta/Elev= 30
  4862.2  238.29  4879.9   233.8  4914.4  220.62  4930.9  215.77  4938.2  215.01
  4945.8  207.58  4998.3  207.08  5052.5  207.68    5065  215.04  5070.7  215.76
  5079.6  215.27    5098  211.79  5114.1  211.45  5129.3  212.25  5147.3  216.26
    5338  213.45  5363.6  214.51  5385.1  213.87  5408.5  215.63  5540.9  215.09
  5610.7  216.14  5654.5  218.53  5698.9  223.43  5762.4  226.75  5846.8  228.91
  5892.5  231.43  5905.7  230.91  5963.9  234.28  6046.2  241.99  6093.2  244.54
#Mann= 3 ,-1 , 0
  4862.2     .15       0  4945.8     .05       0  5052.5     .15       0
Bank Sta=4945.8,5052.5
XS Rating Curve= 0 ,0
Exp/Cntr=0.3,0.1

Type RM Length L Ch R = 1 ,1500    ,500,500,500
BEGIN DESCRIPTION:
WATEREE CREEK 3.0
END DESCRIPTION:
XS GIS Cut Line= 3
      1924330.55        861787.3      1924434.01       861480.89
      1924391.91         860802.
#Sta/Elev= 30
  4676.6  226.29  4696.6  225.06  4700.8  225.76  4708.3  224.39  4741.8  221.86
  4799.9  219.01  4807.5  217.81  4816.7  218.01  4868.7  215.45  4942.8  214.11
  4949.1  213.33  4959.8  206.73  4998.3  206.19  5030.2  206.75  5039.1  213.24
  5053.3  213.28    5092  216.21  5125.6  216.63  5158.2  218.38  5176.5  218.15
    5216  219.49  5256.8  219.81  5288.5  221.21  5298.6  220.42  5320.5  220.96
  5329.6  221.81  5381.3   223.3  5399.2  224.62  5413.7  224.73  5680.2   236.8
#Mann= 3 ,-1 , 0
  4676.6     .15       0  4959.8     .05       0  5030.2     .15       0
Bank Sta=4959.8,5030.2
XS Rating Curve= 0 ,0
Exp/Cntr=0.3,0.1

Type RM Length L Ch R = 1 ,1000    ,500,500,500
BEGIN DESCRIPTION:
WATEREE CREEK 2.0
END DESCRIPTION:
XS GIS Cut Line= 3
      1924675.02       861774.98      1924887.36       861537.19
      1924975.03       861474.98
#Sta/Elev= 30
  4681.2  224.82  4682.6   225.3    4690  225.67  4693.9  225.03  4718.6  224.55
  4738.8  223.58  4792.4  220.33  4799.7  219.58  4836.6  218.22  4839.9  217.61
  4851.6  216.81  4883.3  216.13  4909.9  213.11  4926.3  212.89  4931.3  212.43
  4961.4  212.86  4964.1  210.42  4970.4  206.49  4998.3  205.89  5028.2  206.39
  5035.3  217.22  5036.7  218.78  5045.2  224.96  5049.3  228.63  5053.8  231.88
  5065.3  237.92  5070.3  240.21  5082.1  244.45  5101.3  246.56  5107.5  246.73
#Mann= 3 ,-1 , 0
  4681.2     .15       0  4970.4     .05       0  5028.2     .15       0
Bank Sta=4970.4,5028.2
XS Rating Curve= 0 ,0
Exp/Cntr=0.3,0.1

Type RM Length L Ch R = 1 ,500     ,0,0,0
BEGIN DESCRIPTION:
WATEREE CREEK 1.0
END DESCRIPTION:
XS GIS Cut Line= 3
      1924825.01         861775.      1925235.36       861895.56
      1925398.93       861718.71
#Sta/Elev= 30
  4572.3  224.16  4616.3  223.07  4632.6  223.51  4645.2  222.43  4660.7  223.05
    4665  222.19  4707.3  220.26  4788.2   220.5  4816.4  219.58  4889.3  219.21
  4905.3  217.85  4911.4  216.32  4918.2  211.92    4928  211.41    4938  206.19
  4998.3  205.69  5037.3  206.19  5046.8  211.08  5056.2  212.55  5061.6  214.74
  5076.5  218.72  5089.2  220.88  5103.1  225.33  5118.1  232.52    5126  237.28
  5152.4  246.67  5183.5  254.82  5203.1  258.78    5226  262.17  5240.9  263.19
#Mann= 3 ,-1 , 0
  4572.3     .15       0    4938     .05       0  5037.3     .15       0
Bank Sta=4938,5037.3
XS Rating Curve= 0 ,0
Exp/Cntr=0.3,0.1

Chan Stop Cuts=-1
Use User Specified Reach Order=0
Composite Channel Slope=5

--- WATEREE CREEK.g01 (geometry) ---

Geom Title=Existing Conditions

River Reach=WATEREE CREEK,Reach-1
Reach XY= 30
      1906522.55       839685.45      1907454.88       840084.19
      1907630.97       841090.74      1908813.61       841064.36
      1909769.86       842474.66      1909670.17       844932.94
      1909051.09       845925.62      1909146.08       846842.25
      1908529.66       847407.97      1908572.11       847792.83
      1909178.56       847843.53      1909523.51       849880.21
      1909565.35       850965.40      1908743.95       851885.32
      1909462.69       853579.58      1909223.82       855600.92
      1909810.86       855712.54      1909952.93       856304.41
      1912346.62       856424.22      1911781.31       857588.47
      1913437.54       857817.53      1913898.44       857399.05
      1914883.34       857985.34      1917231.78       858354.94
      1918723.14       859604.67      1918931.47       859305.69
      1923116.29       860073.55      1923464.58       861580.89
      1924784.72       861457.18      1925423.86       862349.49

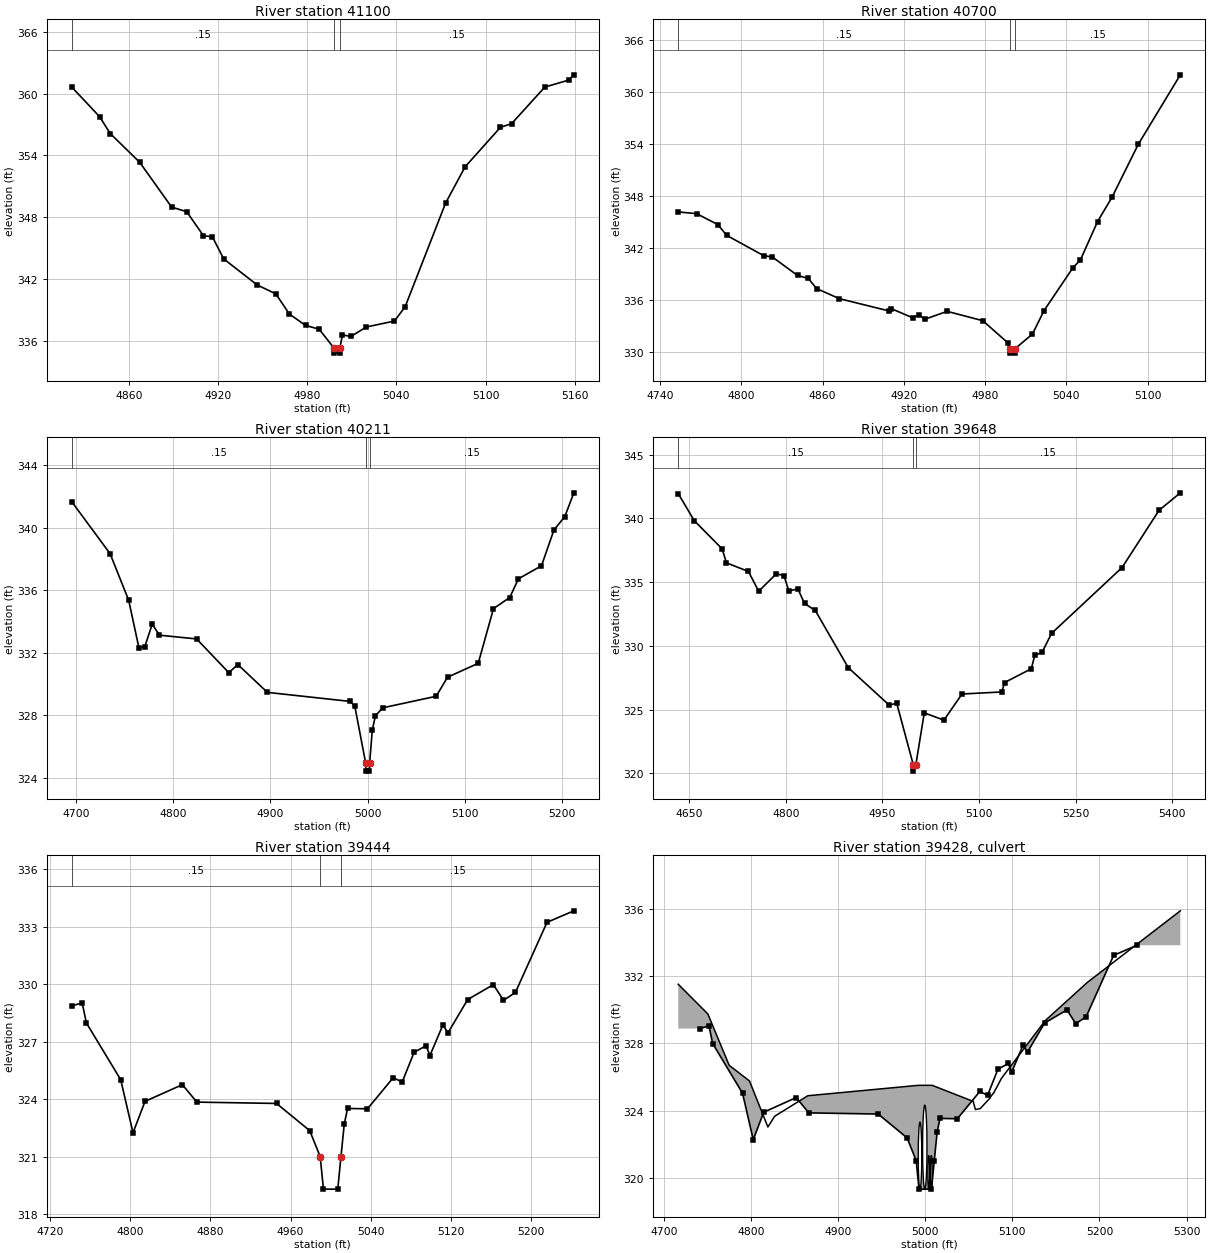
Type RM Length L Ch R = 1,41100,400,400,400
BEGIN DESCRIPTION:
WATEREE CREEK 82.0
END DESCRIPTION:
XS GIS Cut Line= 3
      1908746.81       841491.71      1908910.17       841420.03
      1909049.58       841342.73
#Sta/Elev= 30
  4821.6  360.64  4840.4  357.75  4847.5  356.12  4867.3  353.33  4888.8  348.97
  4898.9  348.53  4910.2  346.19  4916.2  346.09  4923.8  343.94  4946.3  341.41
  4958.9  340.54  4968.0  338.58  4978.9  337.47  4988.0  337.11  4998.0  335.28
  4998.3  334.78  5001.8  334.78  5002.0  335.28  5003.7  336.55  5009.4  336.40
  5019.8  337.32  5038.7  337.90  5045.9  339.29  5073.1  349.36  5086.2  352.88
  5110.0  356.73  5117.5  357.08  5139.9  360.64  5156.0  361.32  5159.4  361.83
#Mann=3,-1,0
  4821.6    0.15       0  4998.0    0.05       0  5002.0    0.15       0
Bank Sta=4998,5002
Exp/Cntr=0.3,0.1

Type RM Length L Ch R = 1,40700,489,489,489
BEGIN DESCRIPTION:
WATEREE CREEK 81.0
END DESCRIPTION:
XS GIS Cut Line= 3
      1909112.07       841717.20      1909203.90       841488.34
      1909218.88       841365.14
#Sta/Elev= 30
  4753.4  346.17  4767.0  345.97  4782.6  344.72  4789.2  343.47  4816.4  341.14
  4822.9  340.98  4841.5  338.85  4849.5  338.51  4855.5  337.35  4872.4  336.18
  4908.7  334.78  4910.7  335.03  4926.4  333.99  4931.1  334.35  4935.4  333.81
  4952.0  334.72  4978.3  333.64  4997.1  331.05  4998.0  330.41  4998.3  329.91
  5001.8  329.91  5002.0  330.41  5014.9  332.10  5023.5  334.81  5044.7  339.72
  5050.4  340.66  5063.0  345.06  5073.7  347.87  5093.0  353.94  5124.1  361.96
#Mann=3,-1,0
  4753.4    0.15       0  4998.0    0.05       0  5002.0    0.15       0
Bank Sta=4998,5002
Exp/Cntr=0.3,0.1

Type RM Length L Ch R = 1,40211,563,563,563
BEGIN DESCRIPTION:
WATEREE CREEK 80.0
END DESCRIPTION:
XS GIS Cut Line= 3
      1909278.89       841939.81      1909540.46       841783.91
      1909705.73       841650.82
#Sta/Elev= 30
  4695.5  341.65  4734.9  338.33  4754.1  335.34  4764.6  332.30  4770.7  332.38
  4778.3  333.82  4785.7  333.11  4824.0  332.87  4857.1  330.71  4866.4  331.23
  4896.8  329.45  4982.1  328.87  4986.8  328.56  4998.0  324.91  4998.3  324.41
  5001.8  324.41  5002.0  324.91  5004.8  327.05  5008.0  327.95  5015.4  328.46
  5070.5  329.20  5082.2  330.42  5113.8  331.31  5129.5  334.81  5146.2  335.52
  5155.2  336.72  5178.9  337.55  5191.7  339.84  5202.9  340.70  5212.2  342.22
#Mann=3,-1,0
  4695.5    0.15       0  4998.0    0.05       0  5002.0    0.15       0
Bank Sta=4998,5002
Exp/Cntr=0.3,0.1

Type RM Length L Ch R = 1,39648,204,204,204
BEGIN DESCRIPTION:
WATEREE CREEK 79.0
END DESCRIPTION:
XS GIS Cut Line= 3
      1909288.40       842162.44      1909653.24       842201.31
      1910032.13       842037.98
#Sta/Elev= 30
  4633.1  341.94  4657.9  339.82  4701.3  337.60  4707.9  336.51  4742.1  335.83
  4758.0  334.28  4785.4  335.65  4797.2  335.51  4804.7  334.32  4819.0  334.45
  4829.2  333.32  4845.9  332.77  4897.0  328.29  4961.0  325.33  4972.2  325.52
  4998.0  320.67  4998.3  320.17  5002.0  320.67  5015.1  324.74  5045.6  324.17
  5073.7  326.22  5135.4  326.38  5139.8  327.12  5181.2  328.20  5186.7  329.26
  5197.8  329.48  5212.8  330.98  5322.2  336.14  5379.6  340.63  5412.6  342.00
#Mann=3,-1,0
  4633.1    0.15       0  4998.0    0.05       0  5002.0    0.15       0
Bank Sta=4998,5002
Exp/Cntr=0.5,0.3

Type RM Length L Ch R = 1,39444,48,48,48
BEGIN DESCRIPTION:
WC_Private Dr-US
END DESCRIPTION:
XS GIS Cut Line= 4
      1909488.73       842459.12      1909618.24       842406.76
      1909735.30       842385.90      1909975.78       842350.27
#Sta/Elev= 30
  4741.4  328.88  4751.8  329.04  4756.0  327.99  4790.3  325.03  4802.6  322.26
  4814.6  323.90  4851.9  324.77  4866.4  323.86  4946.0  323.79  4979.2  322.37
  4989.6  321.02  4992.9  319.32  5007.2  319.32  5010.4  321.02  5013.7  322.72
  5017.0  323.53  5036.9  323.51  5062.7  325.14  5071.5  324.90  5083.5  326.46
  5095.4  326.80  5099.3  326.29  5112.2  327.88  5117.4  327.48  5137.0  329.21
  5162.7  329.99  5172.8  329.17  5184.7  329.58  5216.3  333.24  5243.1  333.84
#Mann=3,-1,0
  4741.4    0.15       0  4989.6    0.05       0  5010.4    0.15       0
#XS Ineff=2,0
    0.00 4984.00  320.00 5016.00    0.00  320.00
Permanent Ineff=
       F       F
Bank Sta=4989.6,5010.4
Exp/Cntr=0.5,0.3

Type RM Length L Ch R =2,39428,,,
BEGIN DESCRIPTION:
WC_Private Dr-TOR
Structure ID: lds 12
Approximate Survey Structure
END DESCRIPTION:
Bridge Culvert--1,0,-1,-1,0
Deck Dist Width WeirC Skew NumUp NumDn MinLoCord MaxHiCord MaxSubmerge Is_Ogee
8,16,3,,23,23,,,0.95,0,1,1,,
  4716.5  4750.5  4775.0  4798.3  4819.4  4827.2  4865.2  4992.0  5008.0  5054.3
  5054.9  5057.6  5063.0  5074.5  5075.5  5079.3  5080.0  5082.3  5087.2  5087.7
  5137.7  5185.9  5292.8
  331.52  329.75  326.69  325.76  323.02  323.66  324.88  325.50  325.50  324.56
  324.57  324.06  324.11  324.75  324.85  325.10  325.20  325.40  325.89  325.93
  329.35  331.62  335.89
  297.42  297.42  297.42  297.42  297.42  297.42  297.42  297.42  297.42  297.42
  297.42  297.42  297.42  297.42  297.42  297.42  297.42  297.42  297.42  297.42
  297.42  297.42  297.42
  4716.5  4750.5  4775.0  4798.3  4819.4  4827.2  4865.2  4992.0  5008.0  5054.3
  5054.9  5057.6  5063.0  5074.5  5075.5  5079.3  5080.0  5082.3  5087.2  5087.7
  5137.7  5185.9  5292.8
  331.52  329.75  326.69  325.76  323.02  323.66  324.88  325.50  325.50  324.56
  324.57  324.06  324.11  324.75  324.85  325.10  325.20  325.40  325.89  325.93
  329.35  331.62  335.89
  297.34  297.34  297.34  297.34  297.34  297.34  297.34  297.34  297.34  297.34
  297.34  297.34  297.34  297.34  297.34  297.34  297.34  297.34  297.34  297.34
  297.34  297.34  297.34
BR Coef=1,1,0,1.25,0,,,0.8,0,2,0,
WSPro=,,,, 1 ,,,, 0 ,,,, 0 ,,,,-1 ,-1 ,-1 , 0 , 0 , 0 , 0 , 0
Culvert=1,4,,16,0.024,0.9,1,2,3,319.32,4994,317.34,4994,Culvert #1,0,8
Culvert Bottom n=0.024
Culvert Bottom Depth=0
Culvert Depth Blocked=0
Culvert=1,5,,16,0.024,0.9,1,2,3,319.32,4999.5,317.34,4999.5,Culvert #2,0,8
Culvert Bottom n=0.024
Culvert Bottom Depth=0
Culvert Depth Blocked=0
Culvert=1,2,,16,0.024,0.9,1,2,3,319.32,5004,317.34,5004,Culvert #3,0,8
Culvert Bottom n=0.024
Culvert Bottom Depth=0
Culvert Depth Blocked=0
Culvert=1,2,,16,0.024,0.9,1,2,3,319.32,5007,317.34,5007,Culvert #4,0,8
Culvert Bottom n=0.024
Culvert Bottom Depth=0
Culvert Depth Blocked=0
BC Design=,,0,,0,,,,,,

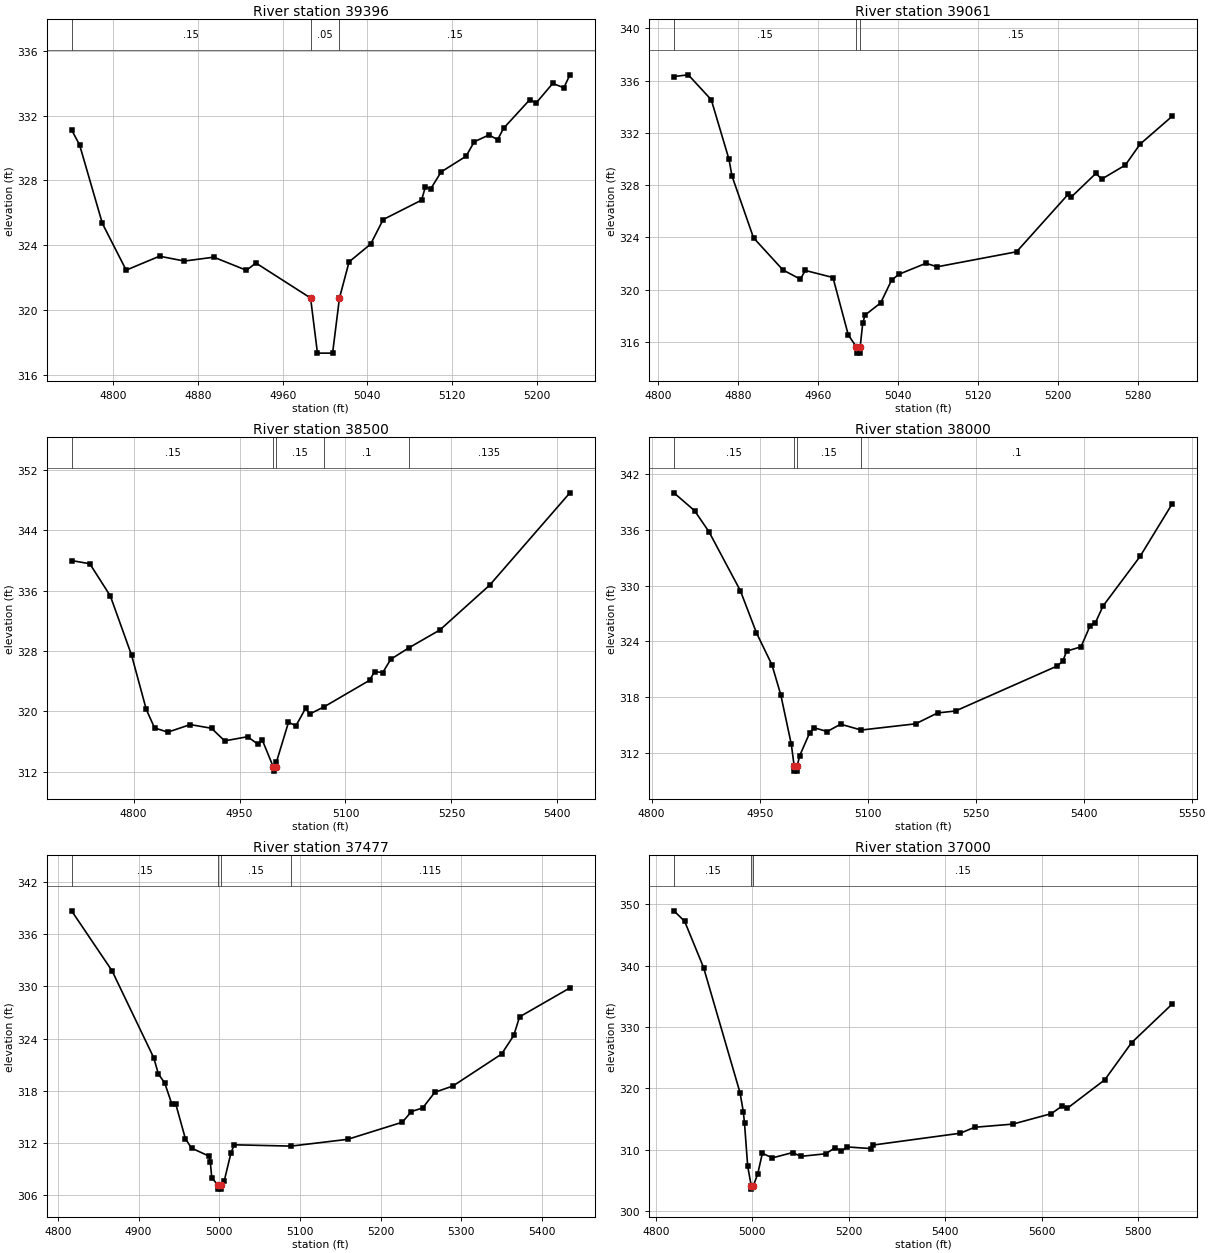
Type RM Length L Ch R = 1,39396,335,335,335
BEGIN DESCRIPTION:
WC_Private Dr-DS
END DESCRIPTION:
XS GIS Cut Line= 3
      1909521.98       842485.13      1909749.15       842430.88
      1909984.46       842399.09
#Sta/Elev= 30
  4760.5  331.12  4768.1  330.18  4789.6  325.34  4812.1  322.46  4843.6  323.32
  4867.1  323.02  4894.9  323.26  4925.8  322.45  4934.7  322.90  4986.4  320.74
  4992.9  317.34  5007.2  317.34  5013.7  320.74  5022.8  322.97  5043.2  324.07
  5055.0  325.58  5091.3  326.78  5094.9  327.60  5100.0  327.48  5109.8  328.52
  5133.4  329.49  5141.1  330.38  5155.0  330.80  5163.2  330.51  5168.8  331.21
  5193.5  332.97  5199.7  332.78  5215.3  333.98  5225.8  333.71  5231.5  334.51
#Mann=3,-1,0
  4760.5    0.15       0  4986.4    0.05       0  5013.7    0.15       0
#XS Ineff=2,0
    0.00 4968.00  320.00 5032.00    0.00  320.00
Permanent Ineff=
       F       F
Bank Sta=4986.4,5013.7
Exp/Cntr=0.5,0.3

Type RM Length L Ch R = 1,39061,561,561,561
BEGIN DESCRIPTION:
WATEREE CREEK 78.0
END DESCRIPTION:
XS GIS Cut Line= 3
      1909478.92       842623.41      1909639.47       842714.31
      1909953.77       842714.09
#Sta/Elev= 30
  4815.5  336.32  4829.9  336.45  4852.9  334.54  4870.6  329.99  4873.6  328.71
  4895.2  323.97  4924.6  321.51  4942.1  320.80  4947.0  321.47  4974.7  320.93
  4990.1  316.52  4998.0  315.64  4998.3  315.14  5001.8  315.14  5002.0  315.64
  5004.5  317.43  5006.8  318.05  5022.5  318.99  5033.4  320.73  5040.8  321.18
  5067.8  322.02  5079.0  321.75  5158.5  322.90  5210.0  327.29  5213.1  327.08
  5238.0  328.91  5243.6  328.46  5267.4  329.54  5282.1  331.14  5314.3  333.28
#Mann=3,-1,0
  4815.5    0.15       0  4998.0    0.05       0  5002.0    0.15       0
Bank Sta=4998,5002
Exp/Cntr=0.3,0.1

Type RM Length L Ch R = 1,38500,500,500,500
BEGIN DESCRIPTION:
WATEREE CREEK 77.0
END DESCRIPTION:
XS GIS Cut Line= 3
      1909407.65       843097.86      1909675.34       843203.53
      1910074.99       843325.00
#Sta/Elev= 30
  4712.2  340.00  4738.0  339.58  4767.1  335.30  4797.2  327.44  4817.9  320.28
  4829.7  317.81  4848.5  317.26  4880.3  318.26  4910.3  317.77  4928.9  316.10
  4961.4  316.65  4976.3  315.64  4982.0  316.26  4998.0  312.59  4998.3  312.09
  5002.0  312.59  5002.3  313.32  5019.3  318.56  5029.9  318.11  5043.4  320.40
  5049.4  319.66  5070.0  320.63  5134.1  324.13  5141.2  325.29  5152.7  325.15
  5164.1  326.92  5190.0  328.45  5233.6  330.80  5304.2  336.75  5417.7  348.98
#Mann=5,-1,0
  4712.2    0.15       0  4998.0    0.05       0  5002.0    0.15       0
  5070.0     0.1       0  5190.0   0.135       0
Bank Sta=4998,5002
Exp/Cntr=0.3,0.1

Type RM Length L Ch R = 1,38000,523,523,523
BEGIN DESCRIPTION:
WATEREE CREEK 76.0
END DESCRIPTION:
XS GIS Cut Line= 3
      1909359.89       843691.96      1909497.71       843593.98
      1909998.79       843444.16
#Sta/Elev= 30
  4830.9  339.98  4859.6  338.06  4879.6  335.79  4923.2  329.45  4945.6  324.91
  4967.1  321.47  4979.3  318.26  4994.0  312.91  4998.0  310.54  4998.3  310.04
  5001.8  310.04  5002.0  310.54  5005.5  311.68  5019.5  314.16  5025.8  314.70
  5043.8  314.30  5062.5  315.09  5091.0  314.46  5166.6  315.13  5197.2  316.30
  5222.0  316.51  5362.7  321.33  5371.0  321.86  5376.3  322.95  5396.3  323.41
  5409.0  325.69  5416.4  326.02  5426.9  327.80  5478.3  333.13  5523.0  338.80
#Mann=4,-1,0
  4830.9    0.15       0  4998.0    0.05       0  5002.0    0.15       0
  5091.0     0.1       0
Bank Sta=4998,5002
Exp/Cntr=0.3,0.1

Type RM Length L Ch R = 1,37477,477,477,477
BEGIN DESCRIPTION:
WATEREE CREEK 75.0
END DESCRIPTION:
XS GIS Cut Line= 3
      1909396.31       844014.24      1909579.37       844010.46
      1910011.36       844058.97
#Sta/Elev= 30
  4816.9  338.69  4867.0  331.80  4918.7  321.80  4924.6  319.90  4932.3  318.90
  4941.1  316.48  4946.0  316.48  4958.0  312.47  4965.6  311.39  4987.2  310.47
  4988.9  309.79  4990.7  307.98  4998.0  307.17  4998.3  306.67  5001.8  306.67
  5002.0  307.17  5006.2  307.63  5014.6  310.88  5018.7  311.77  5089.0  311.62
  5159.2  312.40  5227.0  314.37  5238.3  315.60  5252.2  316.01  5267.3  317.82
  5289.6  318.53  5350.0  322.21  5365.1  324.35  5372.3  326.49  5434.7  329.82
#Mann=4,-1,0
  4816.9    0.15       0  4998.0    0.05       0  5002.0    0.15       0
  5089.0   0.115       0
Bank Sta=4998,5002
Exp/Cntr=0.3,0.1

Type RM Length L Ch R = 1,37000,439,439,439
BEGIN DESCRIPTION:
WATEREE CREEK 74.0
END DESCRIPTION:
XS GIS Cut Line= 4
      1909338.97       844438.26      1909501.28       844432.72
      1910022.65       844405.42      1910348.05       844530.80
#Sta/Elev= 30
  4837.6  348.95  4859.8  347.25  4899.1  339.71  4974.7  319.30  4981.5  316.21
  4984.0  314.30  4990.6  307.32  4998.0  304.09  4998.3  303.59  5002.0  304.09
  5011.4  306.07  5021.0  309.44  5041.5  308.68  5083.9  309.55  5100.5  308.93
  5152.2  309.35  5172.1  310.34  5184.8  309.80  5197.5  310.46  5246.5  310.20
  5250.2  310.77  5431.2  312.70  5461.0  313.67  5540.4  314.19  5620.1  315.89
  5642.4  317.13  5653.5  316.78  5731.1  321.42  5786.4  327.44  5870.8  333.76
#Mann=3,-1,0
  4837.6    0.15       0  4998.0    0.05       0  5002.0    0.15       0
Bank Sta=4998,5002
Exp/Cntr=0.3,0.1

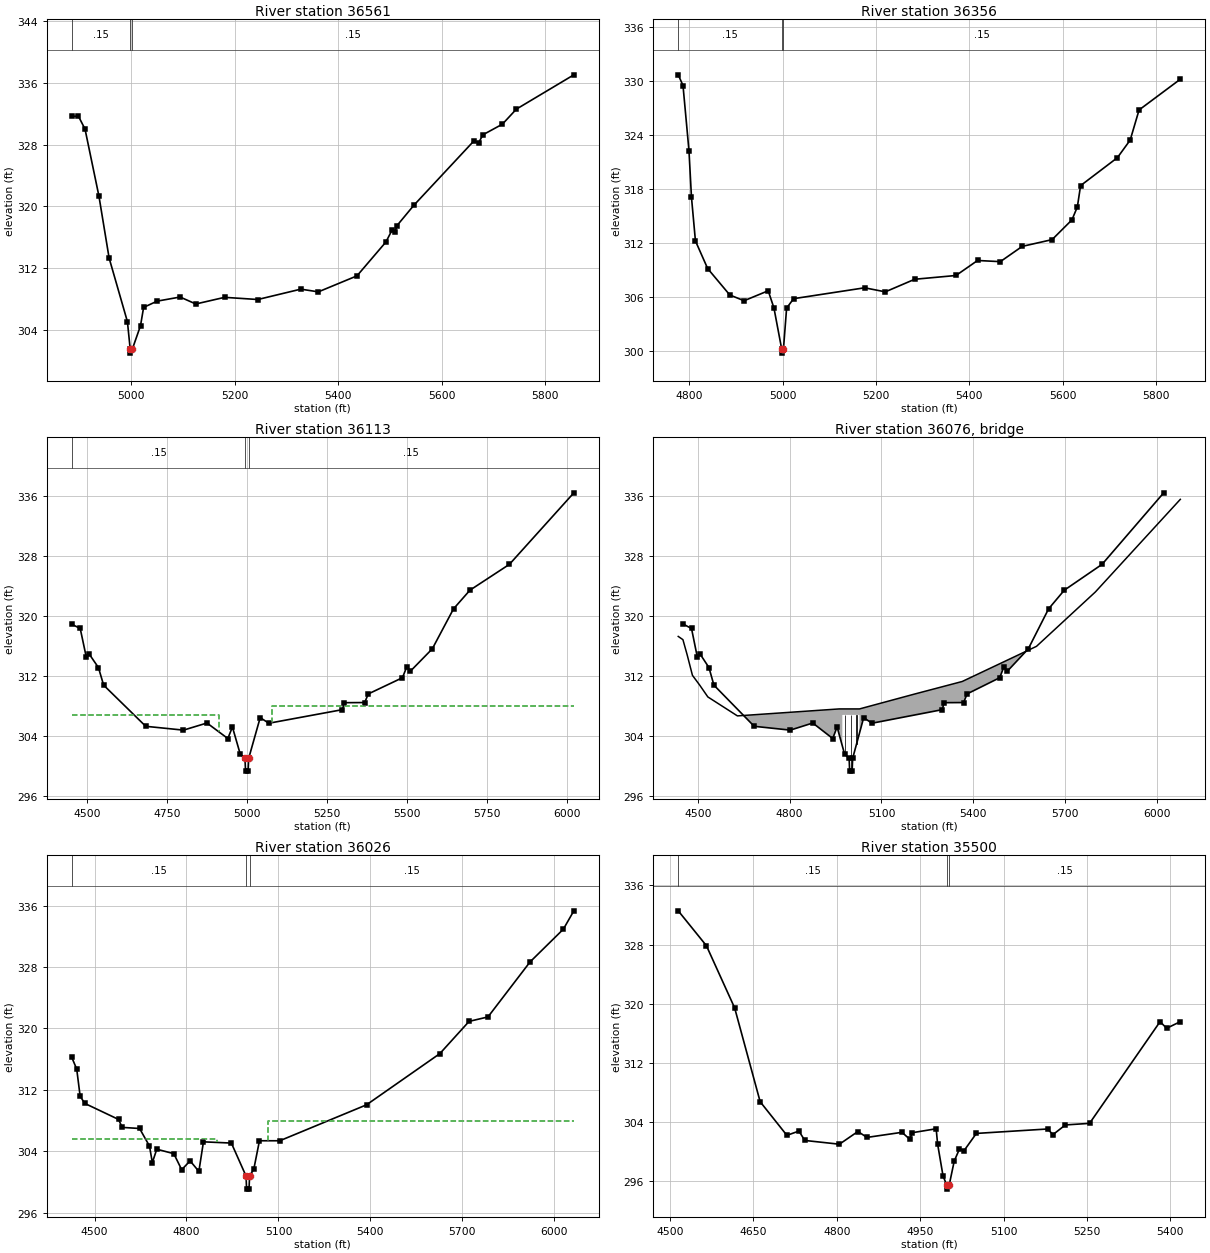
Type RM Length L Ch R = 1,36561,205,205,205
BEGIN DESCRIPTION:
WATEREE CREEK 73.0
END DESCRIPTION:
XS GIS Cut Line= 3
      1909478.98       844819.23      1909587.37       844828.26
      1910425.00       844625.00
#Sta/Elev= 30
  4885.0  331.67  4897.9  331.68  4910.6  330.02  4937.5  321.35  4957.2  313.33
  4992.6  305.09  4998.0  301.52  4998.3  301.02  5002.0  301.52  5017.9  304.57
  5023.9  306.94  5050.1  307.75  5094.5  308.28  5124.8  307.38  5180.5  308.24
  5244.7  307.96  5327.8  309.30  5361.7  308.95  5436.4  311.02  5492.3  315.40
  5504.5  316.98  5510.0  316.65  5513.2  317.48  5546.3  320.15  5662.1  328.46
  5671.9  328.28  5679.9  329.28  5717.5  330.65  5744.6  332.60  5855.7  337.04
#Mann=3,-1,0
  4885.0    0.15       0  4998.0    0.05       0  5002.0    0.15       0
Bank Sta=4998,5002
Exp/Cntr=0.3,0.1

Type RM Length L Ch R = 1,36356,243,243,243
BEGIN DESCRIPTION:
WATEREE CREEK 72.0
END DESCRIPTION:
XS GIS Cut Line= 3
      1909475.93       844840.30      1909635.56       844990.90
      1910274.02       845560.09
#Sta/Elev= 30
  4776.7  330.73  4786.9  329.54  4799.7  322.28  4805.0  317.13  4813.5  312.25
  4839.7  309.17  4887.1  306.23  4917.7  305.59  4969.3  306.70  4981.6  304.78
  4998.0  300.26  4998.3  299.76  5002.0  300.26  5008.7  304.77  5023.7  305.82
  5175.7  307.03  5220.0  306.58  5282.9  307.98  5371.3  308.40  5417.5  310.07
  5466.2  309.94  5513.1  311.64  5577.0  312.39  5619.5  314.59  5631.1  316.03
  5638.0  318.40  5716.8  321.51  5744.2  323.47  5763.2  326.82  5851.5  330.24
#Mann=3,-1,0
  4776.7    0.15       0  4998.0    0.05       0  5002.0    0.15       0
Bank Sta=4998,5002
Exp/Cntr=0.5,0.3

Type RM Length L Ch R = 1,36113,87,87,87
BEGIN DESCRIPTION:
WC_Old Hilton RD - US
END DESCRIPTION:
XS GIS Cut Line= 6
      1909364.50       844731.91      1909358.48       844966.80
      1909774.10       845493.86      1909840.36       845560.12
      1909918.66       845602.28      1910364.43       845779.99
#Sta/Elev= 30
  4453.0  318.95  4479.4  318.38  4498.3  314.57  4507.1  314.99  4536.3  313.17
  4552.6  310.82  4684.1  305.33  4802.1  304.82  4875.5  305.77  4940.7  303.70
  4955.0  305.24  4979.5  301.61  4994.3  301.05  4996.0  299.35  5004.0  299.35
  5005.8  301.05  5041.8  306.49  5068.8  305.74  5298.5  307.55  5304.5  308.48
  5368.3  308.50  5379.6  309.65  5486.2  311.81  5499.3  313.20  5511.3  312.69
  5579.6  315.67  5645.9  321.00  5697.2  323.49  5820.6  326.94  6021.9  336.48
#Mann=3,-1,0
  4453.0    0.15       0  4994.3    0.05       0  5005.8    0.15       0
#XS Ineff=2,0
    0.00 4913.00  306.87 5080.00    0.00  308.00
Permanent Ineff=
       F       F
Bank Sta=4994.3,5005.8
Exp/Cntr=0.5,0.3

Type RM Length L Ch R =3,36076,,,
BEGIN DESCRIPTION:
WC_Old Hilton RD (DS) - TOR
Structure ID: lds 15
Approximate Survey Structure
END DESCRIPTION:
Bridge Culvert--1,0,-1,-1,0
Deck Dist Width WeirC Skew NumUp NumDn MinLoCord MaxHiCord MaxSubmerge Is_Ogee
24,26,3,,18,18,,,0.95,0,1,1,,
  4436.0  4451.3  4465.2  4482.4  4506.0  4532.7  4629.3  4961.8  4972.0  4972.0
  5028.0  5028.0  5028.3  5208.6  5363.7  5606.4  5798.6  6076.2
  317.32  316.89  314.86  312.13  310.83  309.25  306.72  307.65  307.65  307.65
  307.65  307.65  307.65  309.64  311.31  316.00  323.25  335.61
  279.32  279.32  279.32  279.32  279.32  279.32  279.32  279.32  279.32  306.85
  306.85  279.32  279.32  279.32  279.32  279.32  279.32  279.32
  4436.0  4451.3  4465.2  4482.4  4506.0  4532.7  4629.3  4961.8  4972.0  4972.0
  5028.0  5028.0  5028.3  5208.6  5363.7  5606.4  5798.6  6076.2
  317.32  316.89  314.86  312.13  310.83  309.25  306.72  307.65  307.65  307.65
  307.65  307.65  307.65  309.64  311.31  316.00  323.25  335.61
  279.32  279.32  279.32  279.32  279.32  279.32  279.32  279.32  279.32  306.85
  306.85  279.32  279.32  279.32  279.32  279.32  279.32  279.32
Pier Skew, UpSta & Num, DnSta & Num=,4981.3,2,4981.3,2,0,0,0,0,0
       1       1
  301.70  306.85
       1       1
  301.00  306.85
Pier Skew, UpSta & Num, DnSta & Num=,5000,2,5000,2,0,0,0,0,0
       1       1
  299.35  306.85
       1       1
  298.00  306.85
Pier Skew, UpSta & Num, DnSta & Num=,5018.7,2,5018.7,2,0,0,0,0,0
       1       1
  304.00  306.85
       1       1
  301.00  306.85
Abutment Skew #Up #Dn=,2,2
  4972.0  4979.0
  306.85  301.68
  4972.0  4979.0
  306.85  301.92
Abutment Skew #Up #Dn=,2,2
  5021.1  5028.0
  304.23  306.85
  5021.0  5028.0
  302.12  306.85
BR Coef=1,1,0,1.25,0,,,0.8,0,2,0,
WSPro=,,,, 1 ,,,, 0 ,,,, 0 ,,,,-1 ,-1 ,-1 , 0 , 0 , 0 , 0 , 0
BC Design=,,0,,0,,,,,,

Type RM Length L Ch R = 1,36026,526,526,526
BEGIN DESCRIPTION:
WC_Old Hilton RD (DS) - DS
END DESCRIPTION:
XS GIS Cut Line= 6
      1909304.26       844764.99      1909304.26       845060.17
      1909698.80       845530.00      1909807.23       845629.39
      1909903.60       845686.61      1910343.28       845852.24
#Sta/Elev= 30
  4425.8  316.23  4441.9  314.71  4453.1  311.18  4468.0  310.24  4578.3  308.15
  4590.3  307.11  4647.0  306.97  4679.3  304.68  4688.6  302.53  4703.1  304.27
  4758.6  303.69  4784.3  301.60  4811.8  302.75  4840.4  301.38  4855.3  305.23
  4946.4  305.07  4994.3  300.77  4996.0  299.07  5004.0  299.07  5005.8  300.77
  5019.6  301.68  5038.0  305.37  5104.2  305.37  5387.2  310.05  5626.4  316.72
  5721.8  320.92  5783.4  321.50  5920.8  328.67  6029.3  332.93  6063.5  335.32
#Mann=3,-1,0
  4425.8    0.15       0  4994.3    0.05       0  5005.8    0.15       0
#XS Ineff=2,0
    0.00 4900.00  305.64 5065.00    0.00  308.00
Permanent Ineff=
       F       F
Bank Sta=4994.3,5005.8
Exp/Cntr=0.5,0.3

Type RM Length L Ch R = 1,35500,591,591,591
BEGIN DESCRIPTION:
WATEREE CREEK 71.0
END DESCRIPTION:
XS GIS Cut Line= 3
      1908841.62       845479.36      1909266.01       845714.97
      1909639.65       845902.36
#Sta/Elev= 30
  4514.6  332.57  4565.3  327.85  4616.1  319.43  4662.0  306.73  4710.1  302.18
  4731.8  302.76  4742.3  301.49  4804.6  300.98  4837.9  302.70  4854.2  301.90
  4917.2  302.59  4930.9  301.67  4936.0  302.54  4978.7  303.07  4981.3  301.00
  4991.1  296.67  4998.0  295.40  4998.3  294.90  5002.0  295.40  5011.2  298.70
  5020.5  300.31  5029.0  300.12  5051.0  302.44  5179.1  303.04  5188.9  302.28
  5211.2  303.59  5254.7  303.80  5381.6  317.57  5393.4  316.67  5418.0  317.57
#Mann=3,-1,0
  4514.6    0.15       0  4998.0    0.05       0  5002.0    0.15       0
Bank Sta=4998,5002
Exp/Cntr=0.3,0.1