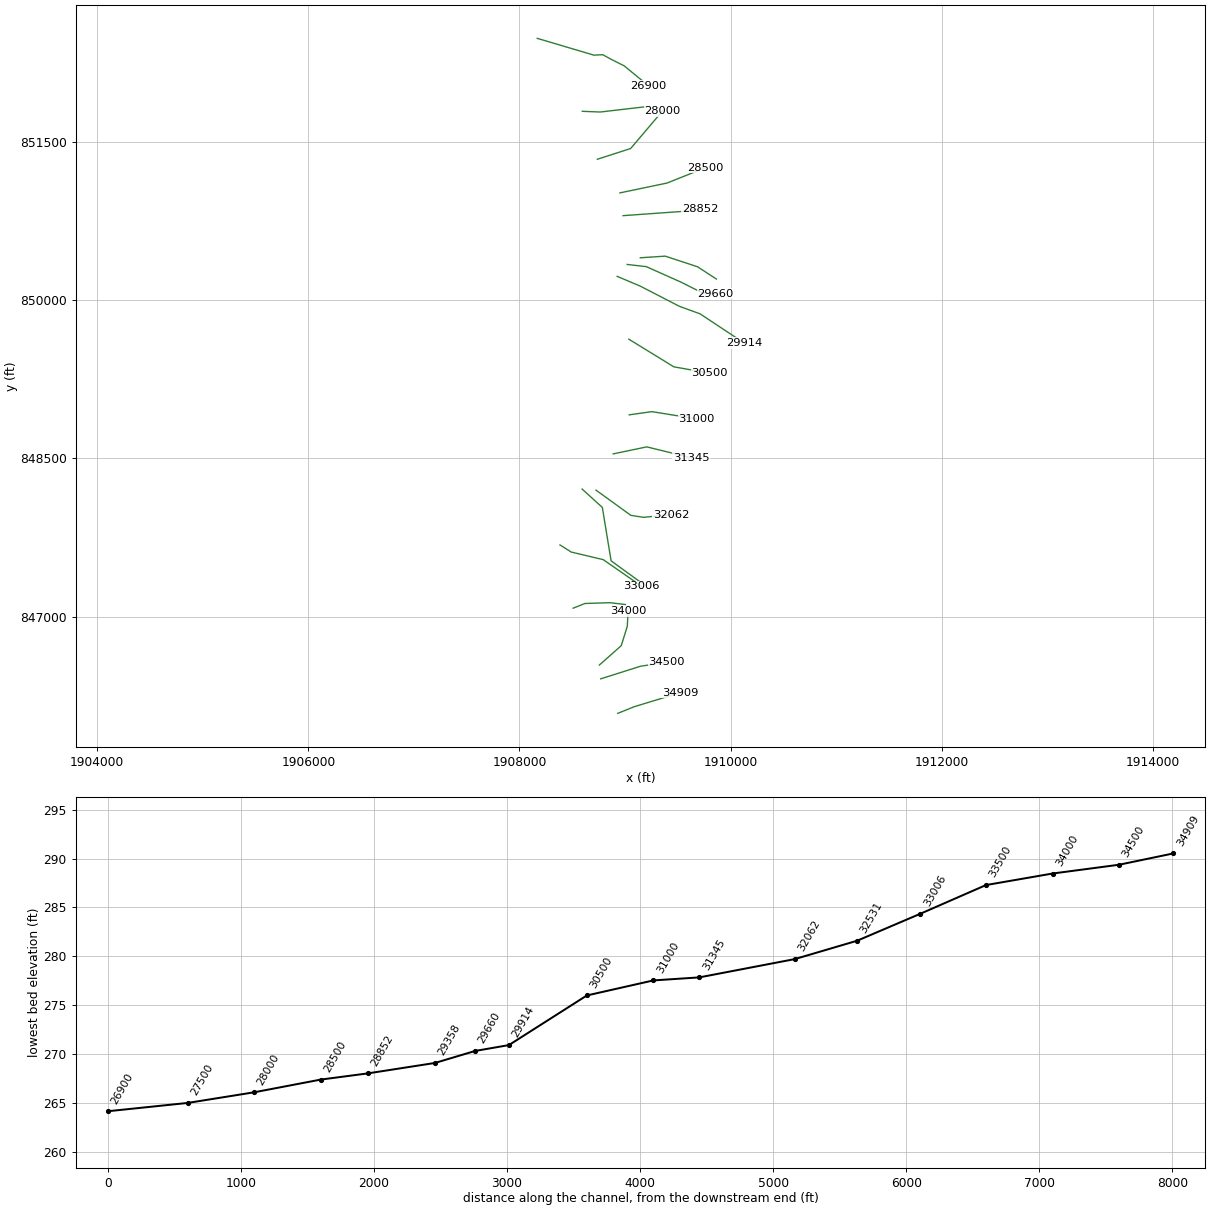
HEC-RAS study WATEREE CREEK.prj: WATEREE CREEK Limited Detail Study

--- WATEREE CREEK.g01 (geometry) --- (continued)

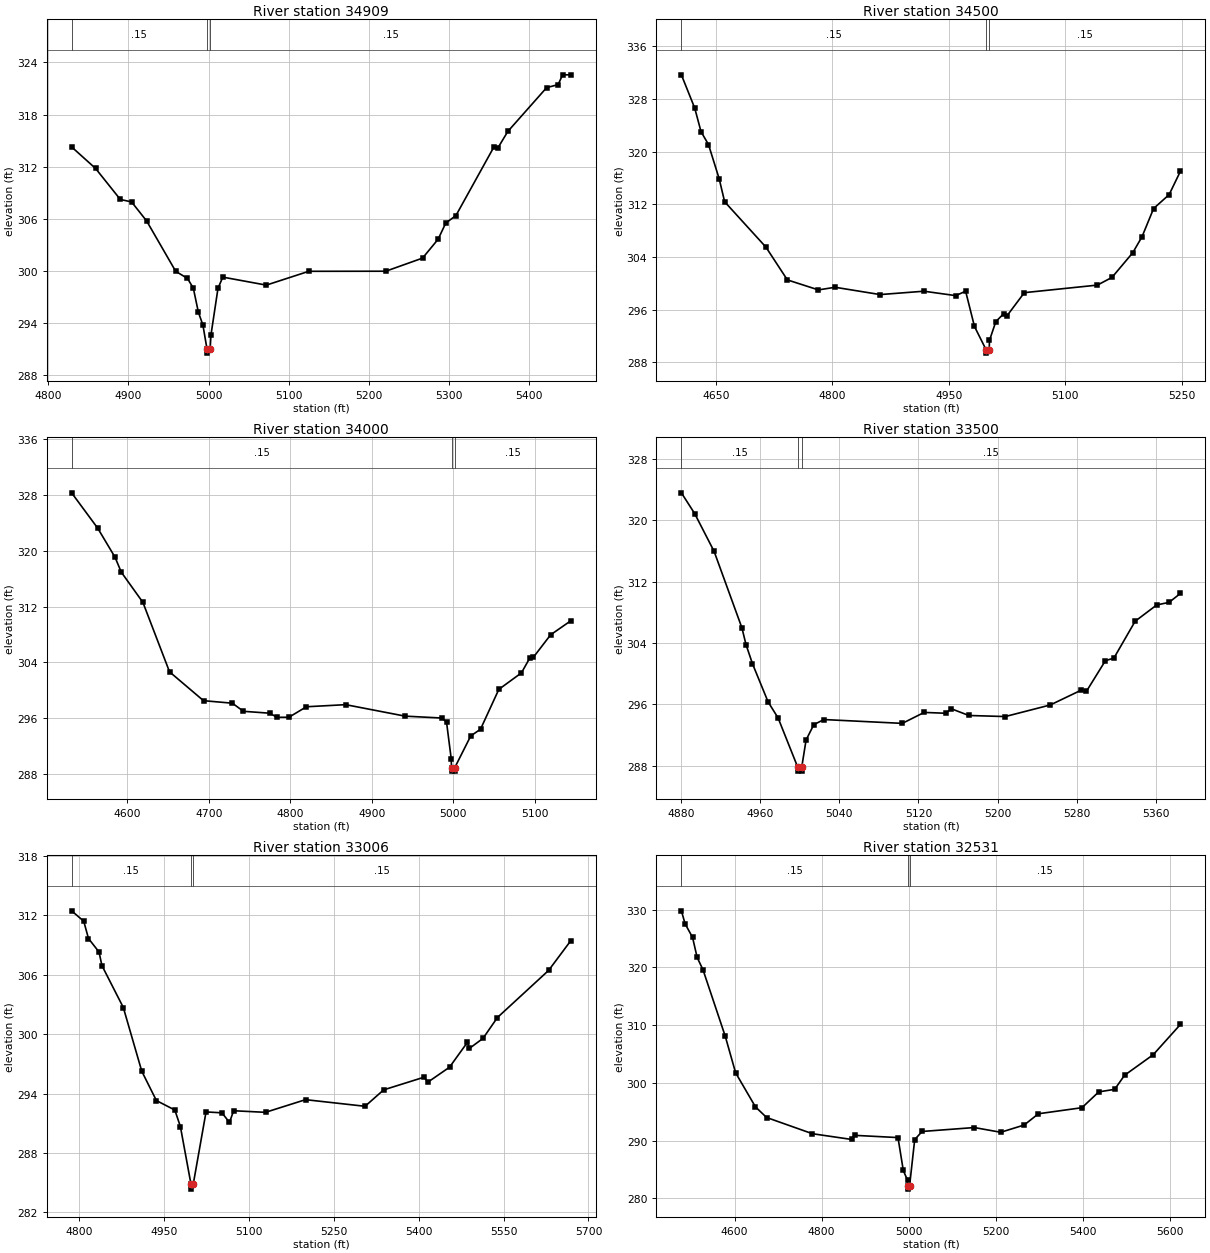
Type RM Length L Ch R = 1,34909,409,409,409
BEGIN DESCRIPTION:
WATEREE CREEK 70.0
END DESCRIPTION:
XS GIS Cut Line= 3
      1908930.30       846083.04      1909088.84       846146.86
      1909521.16       846278.76
#Sta/Elev= 30
  4829.1  314.27  4859.0  311.79  4889.9  308.22  4903.9  307.94  4922.7  305.75
  4959.0  299.95  4973.7  299.13  4981.0  298.01  4987.3  295.24  4993.0  293.75
  4998.0  291.03  4998.3  290.53  5002.0  291.03  5003.0  292.61  5011.8  298.00
  5017.8  299.28  5072.1  298.36  5125.1  299.95  5221.2  299.96  5267.1  301.47
  5286.5  303.64  5296.1  305.51  5308.7  306.36  5356.0  314.24  5360.9  314.12
  5373.5  316.05  5422.0  321.10  5436.3  321.44  5441.9  322.57  5452.0  322.57
#Mann=3,-1,0
  4829.1    0.15       0  4998.0    0.05       0  5002.0    0.15       0
Bank Sta=4998,5002
Exp/Cntr=0.3,0.1

Type RM Length L Ch R = 1,34500,500,500,500
BEGIN DESCRIPTION:
WATEREE CREEK 69.0
END DESCRIPTION:
XS GIS Cut Line= 3
      1908769.64       846410.46      1909145.72       846529.58
      1909391.12       846567.46
#Sta/Elev= 30
  4605.5  331.67  4622.7  326.61  4630.8  323.03  4640.4  321.08  4654.2  315.86
  4661.2  312.38  4714.4  305.48  4742.0  300.50  4782.0  298.98  4803.5  299.38
  4861.5  298.27  4917.9  298.78  4958.8  298.11  4971.6  298.78  4983.0  293.42
  4998.0  289.87  4998.3  289.37  5002.0  289.87  5002.3  291.30  5010.5  294.16
  5020.4  295.34  5024.6  295.00  5047.2  298.56  5141.3  299.71  5160.1  300.88
  5186.8  304.62  5198.8  307.06  5213.7  311.35  5233.7  313.46  5248.3  317.03
#Mann=3,-1,0
  4605.5    0.15       0  4998.0    0.05       0  5002.0    0.15       0
Bank Sta=4998,5002
Exp/Cntr=0.3,0.1

Type RM Length L Ch R = 1,34000,500,500,500
BEGIN DESCRIPTION:
WATEREE CREEK 68.0
END DESCRIPTION:
XS GIS Cut Line= 4
      1908756.57       846541.32      1908963.70       846724.46
      1909020.97       846907.53      1909029.12       847051.60
#Sta/Elev= 30
  4531.7  328.25  4563.7  323.20  4585.0  319.04  4592.6  316.92  4619.2  312.59
  4651.9  302.66  4693.6  298.54  4729.0  298.18  4742.6  297.02  4774.9  296.75
  4783.8  296.16  4798.4  296.17  4819.9  297.67  4868.1  297.97  4941.0  296.33
  4986.2  296.06  4991.9  295.47  4997.6  290.27  4998.0  288.97  4998.3  288.47
  5001.8  288.47  5002.0  288.97  5021.6  293.50  5033.6  294.46  5056.1  300.16
  5083.8  302.51  5093.9  304.60  5098.4  304.73  5119.6  307.95  5144.3  309.95
#Mann=3,-1,0
  4531.7    0.15       0  4998.0    0.05       0  5002.0    0.15       0
Bank Sta=4998,5002
Exp/Cntr=0.3,0.1

Type RM Length L Ch R = 1,33500,494,494,494
BEGIN DESCRIPTION:
WATEREE CREEK 67.0
END DESCRIPTION:
XS GIS Cut Line= 4
      1908507.99       847079.91      1908619.08       847124.49
      1908856.85       847132.23      1909002.91       847114.79
#Sta/Elev= 30
  4880.3  323.60  4893.8  320.88  4913.4  315.96  4941.5  305.99  4945.7  303.78
  4952.2  301.30  4968.0  296.32  4978.1  294.23  4998.0  287.79  4998.3  287.29
  5001.8  287.29  5002.0  287.79  5006.4  291.35  5014.2  293.35  5024.4  294.02
  5103.7  293.52  5125.8  294.95  5147.5  294.84  5153.4  295.42  5171.0  294.55
  5207.8  294.41  5253.3  295.92  5284.4  297.84  5289.9  297.70  5309.1  301.70
  5317.7  302.04  5339.2  306.85  5361.0  308.97  5373.5  309.31  5385.0  310.48
#Mann=3,-1,0
  4880.3    0.15       0  4998.0    0.05       0  5002.0    0.15       0
Bank Sta=4998,5002
Exp/Cntr=0.3,0.1

Type RM Length L Ch R = 1,33006,475,475,475
BEGIN DESCRIPTION:
WATEREE CREEK 66.0
END DESCRIPTION:
XS GIS Cut Line= 4
      1908383.65       847679.57      1908490.51       847611.96
      1908793.61       847540.00      1909157.80       847287.04
#Sta/Elev= 30
  4787.2  312.47  4808.6  311.42  4817.0  309.67  4835.6  308.31  4840.7  306.94
  4878.5  302.70  4911.1  296.26  4936.9  293.30  4969.5  292.34  4979.3  290.67
  4998.0  284.85  4998.3  284.35  5002.0  284.85  5024.6  292.15  5052.7  292.06
  5066.0  291.09  5073.3  292.27  5129.6  292.11  5200.3  293.39  5305.4  292.72
  5338.3  294.38  5409.7  295.66  5416.4  295.16  5454.6  296.67  5486.3  299.19
  5489.5  298.56  5513.7  299.58  5539.2  301.69  5629.6  306.45  5668.6  309.44
#Mann=3,-1,0
  4787.2    0.15       0  4998.0    0.05       0  5002.0    0.15       0
Bank Sta=4998,5002
Exp/Cntr=0.3,0.1

Type RM Length L Ch R = 1,32531,469,469,469
BEGIN DESCRIPTION:
WATEREE CREEK 65.0
END DESCRIPTION:
XS GIS Cut Line= 4
      1908592.97       848209.47      1908784.89       848035.00
      1908867.75       847529.10      1909170.87       847308.85
#Sta/Elev= 30
  4477.8  329.81  4486.3  327.57  4503.5  325.20  4514.0  321.74  4527.6  319.57
  4578.6  308.08  4602.4  301.75  4648.0  295.84  4673.6  294.00  4778.9  291.19
  4868.7  290.20  4875.8  290.91  4975.5  290.52  4987.7  284.82  4997.4  283.13
  4998.0  282.09  4998.3  281.59  5002.0  282.09  5013.9  290.18  5030.9  291.58
  5150.9  292.26  5211.6  291.44  5265.4  292.70  5298.2  294.65  5398.2  295.70
  5436.8  298.44  5473.3  298.88  5496.1  301.32  5561.9  304.88  5624.5  310.13
#Mann=3,-1,0
  4477.8    0.15       0  4998.0    0.05       0  5002.0    0.15       0
Bank Sta=4998,5002
Exp/Cntr=0.3,0.1

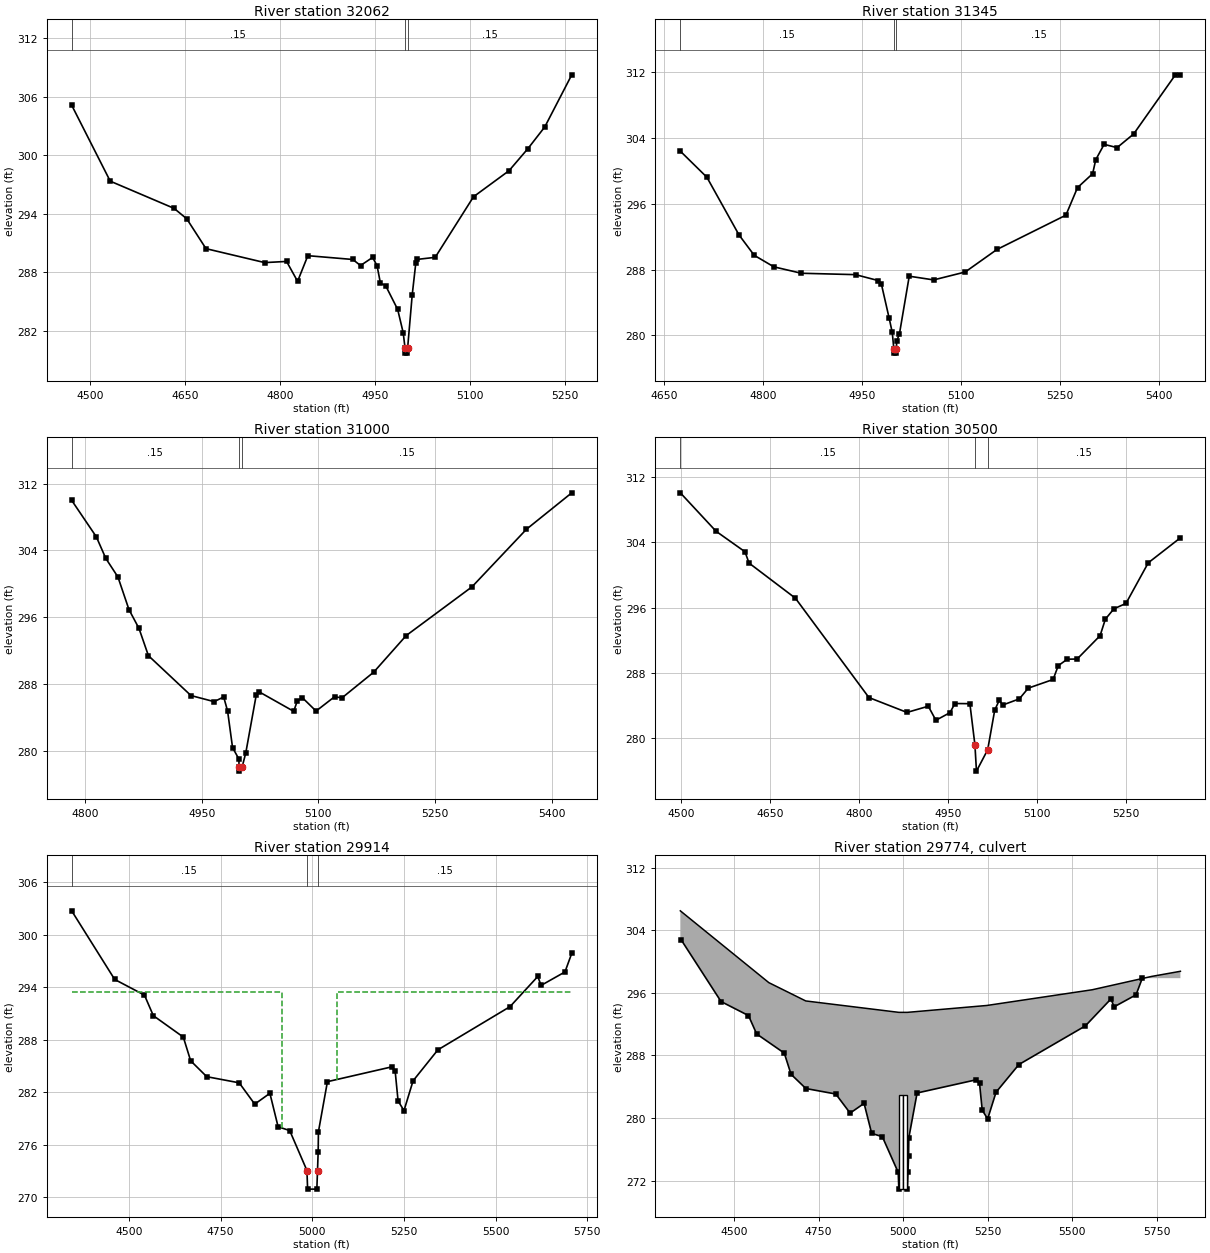
Type RM Length L Ch R = 1,32062,717,717,717
BEGIN DESCRIPTION:
WATEREE CREEK 64.0
END DESCRIPTION:
XS GIS Cut Line= 4
      1908724.94       848198.82      1909055.20       847959.90
      1909174.83       847941.21      1909434.88       847966.80
#Sta/Elev= 30
  4471.3  305.13  4532.2  297.34  4633.1  294.55  4653.1  293.48  4683.5  290.42
  4776.3  288.99  4810.8  289.11  4828.2  287.07  4844.4  289.70  4915.4  289.31
  4927.6  288.69  4946.7  289.52  4953.7  288.68  4959.1  286.87  4967.2  286.64
  4986.3  284.19  4995.0  281.81  4998.0  280.21  4998.3  279.71  5001.8  279.71
  5002.0  280.21  5009.3  285.70  5015.0  288.99  5017.4  289.32  5045.6  289.53
  5106.1  295.74  5162.2  298.41  5192.0  300.67  5218.7  302.90  5261.3  308.24
#Mann=3,-1,0
  4471.3    0.15       0  4998.0    0.05       0  5002.0    0.15       0
Bank Sta=4998,5002
Exp/Cntr=0.3,0.1

Type RM Length L Ch R = 1,31345,345,345,345
BEGIN DESCRIPTION:
WATEREE CREEK 63.0
END DESCRIPTION:
XS GIS Cut Line= 3
      1908887.63       848542.51      1909206.07       848608.95
      1909625.52       848506.00
#Sta/Elev= 30
  4674.7  302.39  4714.9  299.22  4763.6  292.20  4786.6  289.73  4816.3  288.33
  4857.8  287.55  4940.0  287.38  4974.4  286.66  4979.1  286.24  4990.9  282.09
  4995.6  280.35  4998.0  278.34  4998.3  277.84  5001.8  277.84  5002.0  278.34
  5002.2  279.30  5006.4  280.15  5021.3  287.19  5058.3  286.74  5106.0  287.70
  5154.1  290.44  5258.5  294.61  5276.1  297.96  5299.0  299.65  5303.7  301.35
  5316.4  303.22  5336.0  302.82  5361.1  304.48  5424.3  311.67  5431.9  311.66
#Mann=3,-1,0
  4674.7    0.15       0  4998.0    0.05       0  5002.0    0.15       0
Bank Sta=4998,5002
Exp/Cntr=0.3,0.1

Type RM Length L Ch R = 1,31000,500,500,500
BEGIN DESCRIPTION:
WATEREE CREEK 62.0
END DESCRIPTION:
XS GIS Cut Line= 3
      1909039.44       848912.69      1909254.52       848942.98
      1909674.96       848875.01
#Sta/Elev= 30
  4782.8  309.99  4814.5  305.62  4826.7  303.03  4842.3  300.80  4856.5  296.89
  4869.4  294.63  4881.5  291.37  4936.2  286.59  4966.0  285.86  4978.3  286.42
  4983.3  284.74  4989.7  280.35  4997.9  278.97  4998.0  278.03  4998.3  277.53
  5002.0  278.03  5006.7  279.71  5020.1  286.63  5023.4  287.06  5068.3  284.70
  5073.0  285.95  5079.5  286.33  5097.1  284.73  5120.9  286.45  5130.4  286.31
  5171.3  289.40  5213.0  293.78  5297.6  299.62  5367.6  306.52  5425.9  310.89
#Mann=3,-1,0
  4782.8    0.15       0  4998.0    0.05       0  5002.0    0.15       0
Bank Sta=4998,5002
Exp/Cntr=0.3,0.1

Type RM Length L Ch R = 1,30500,586,586,586
BEGIN DESCRIPTION:
WATEREE CREEK 61.0
END DESCRIPTION:
XS GIS Cut Line= 3
      1909035.56       849629.85      1909462.29       849367.55
      1909799.19       849308.11
#Sta/Elev= 30
  4499.1  310.03  4559.3  305.33  4608.1  302.82  4614.9  301.44  4693.1  297.14
  4817.0  284.99  4881.2  283.17  4917.1  283.93  4929.9  282.21  4953.6  283.14
  4962.0  284.26  4987.2  284.24  4995.7  279.20  4998.3  275.99  5017.2  278.60
  5029.1  283.46  5036.9  284.68  5042.4  284.07  5070.6  284.83  5085.6  286.14
  5127.5  287.20  5136.2  288.89  5151.4  289.68  5168.0  289.70  5206.7  292.56
  5215.6  294.58  5230.1  295.85  5250.3  296.50  5287.9  301.47  5342.1  304.53
#Mann=3,-1,0
  4499.1    0.15       0  4995.7    0.05       0  5017.2    0.15       0
Bank Sta=4995.7,5017.2
Exp/Cntr=0.5,0.3

Type RM Length L Ch R = 1,29914,254,254,254
BEGIN DESCRIPTION:
WC_I-26 - US
END DESCRIPTION:
XS GIS Cut Line= 5
      1908925.36       850225.20      1909142.71       850133.21
      1909515.74       849940.90      1909710.07       849870.21
      1910127.52       849593.91
#Sta/Elev= 30
  4344.3  302.74  4461.6  294.89  4542.7  293.10  4566.9  290.75  4648.6  288.30
  4668.6  285.59  4712.5  283.77  4800.9  283.07  4843.3  280.63  4884.6  281.87
  4907.0  278.04  4938.6  277.61  4985.6  273.04  4987.4  270.91  5012.6  270.91
  5014.4  273.04  5016.2  275.16  5016.9  277.47  5041.4  283.20  5216.4  284.89
  5226.0  284.43  5234.0  281.00  5250.1  279.89  5274.9  283.30  5342.5  286.84
  5539.1  291.78  5614.8  295.23  5623.8  294.21  5688.9  295.75  5707.4  297.88
#Mann=3,-1,0
  4344.3    0.15       0  4985.6    0.05       0  5014.4    0.15       0
#XS Ineff=2,0
    0.00 4917.00  293.41 5066.40    0.00  293.44
Permanent Ineff=
       F       F
Bank Sta=4985.6,5014.4
Exp/Cntr=0.5,0.3

Type RM Length L Ch R =2,29774,,,
BEGIN DESCRIPTION:
WC_I-26 - TOR
Structure ID: lds 17
Approximate Survey Structure
END DESCRIPTION:
Bridge Culvert--1,0,-1,-1,0
Deck Dist Width WeirC Skew NumUp NumDn MinLoCord MaxHiCord MaxSubmerge Is_Ogee
80,120,3,,9,9,,,0.95,0,1,1,,
  4341.2  4602.9  4712.0  4987.5  5012.5  5247.6  5559.4  5734.5  5820.1
  306.49  297.31  294.97  293.51  293.51  294.39  296.40  298.10  298.76
  250.91  250.91  250.91  250.91  250.91  250.91  250.91  250.91  250.91
  4341.2  4602.9  4712.0  4987.5  5012.5  5247.6  5559.4  5734.5  5820.1
  306.49  297.31  294.97  293.51  293.51  294.39  296.40  298.10  298.76
  250.31  250.31  250.31  250.31  250.31  250.31  250.31  250.31  250.31
BR Coef=1,1,0,1.25,0,,,0.8,0,2,0,
WSPro=,,,, 1 ,,,, 0 ,,,, 0 ,,,,-1 ,-1 ,-1 , 0 , 0 , 0 , 0 , 0
Culvert=2,12,12,120,0.012,0.4,1,8,1,270.91,4993.5,270.31,4993.5,Culvert #1,0,80
Culvert Bottom n=0.012
Culvert Bottom Depth=0
Culvert Depth Blocked=0
Culvert=2,12,12,120,0.012,0.4,1,8,1,270.91,5006.5,270.31,5006.5,Culvert #2,0,80
Culvert Bottom n=0.012
Culvert Bottom Depth=0
Culvert Depth Blocked=0
BC Design=,,0,,0,,,,,,

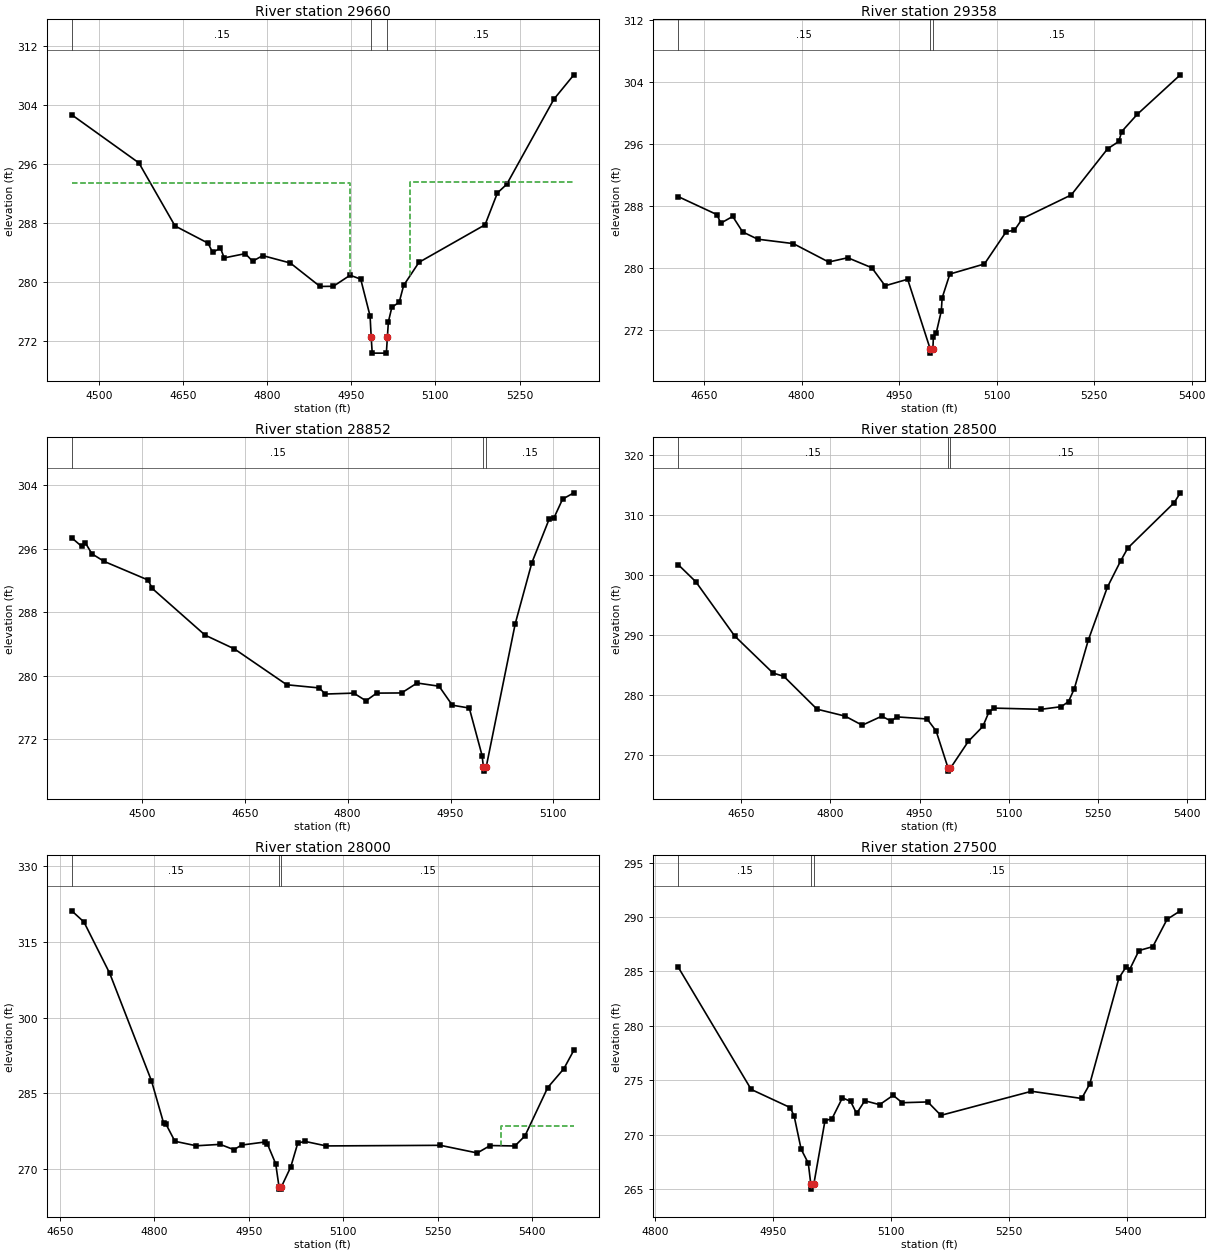
Type RM Length L Ch R = 1,29660,302,302,302
BEGIN DESCRIPTION:
WC_I-26 - DS
END DESCRIPTION:
XS GIS Cut Line= 5
      1909019.78       850338.11      1909201.35       850317.25
      1909534.80       850168.22      1909733.33       850067.92
      1909857.36       850060.17
#Sta/Elev= 30
  4452.0  302.62  4571.6  296.10  4636.0  287.55  4694.8  285.22  4703.0  283.97
  4717.0  284.55  4723.6  283.22  4761.2  283.80  4774.2  282.77  4792.3  283.53
  4841.4  282.53  4894.4  279.35  4918.1  279.37  4948.0  280.87  4966.9  280.34
  4983.6  275.33  4985.6  272.44  4987.4  270.31  5012.6  270.31  5014.4  272.44
  5016.2  274.56  5022.4  276.53  5035.5  277.21  5043.4  279.49  5070.7  282.62
  5188.5  287.71  5210.5  292.03  5227.1  293.20  5311.2  304.74  5346.7  308.04
#Mann=3,-1,0
  4452.0    0.15       0  4985.6    0.05       0  5014.4    0.15       0
#XS Ineff=2,0
    0.00 4947.00  293.37 5054.00    0.00  293.57
Permanent Ineff=
       F       F
Bank Sta=4985.6,5014.4
Exp/Cntr=0.5,0.3

Type RM Length L Ch R = 1,29358,506,506,506
BEGIN DESCRIPTION:
WATEREE CREEK 59.0
END DESCRIPTION:
XS GIS Cut Line= 4
      1909144.09       850401.31      1909380.56       850416.82
      1909686.81       850316.02      1909865.15       850199.72
#Sta/Elev= 30
  4610.3  289.23  4669.9  286.91  4675.7  285.81  4694.1  286.68  4709.3  284.69
  4732.5  283.75  4787.3  283.18  4841.7  280.81  4871.1  281.36  4908.1  280.07
  4928.5  277.75  4963.2  278.59  4998.0  269.58  4998.3  269.08  5002.0  269.58
  5002.8  271.22  5007.1  271.66  5015.0  274.52  5016.2  276.18  5028.1  279.26
  5081.3  280.56  5114.9  284.73  5127.3  284.88  5139.7  286.40  5214.9  289.45
  5270.7  295.38  5287.9  296.33  5292.5  297.61  5316.2  299.81  5382.6  304.91
#Mann=3,-1,0
  4610.3    0.15       0  4998.0    0.05       0  5002.0    0.15       0
Bank Sta=4998,5002
Exp/Cntr=0.3,0.1

Type RM Length L Ch R = 1,28852,352,352,352
BEGIN DESCRIPTION:
WATEREE CREEK 58.0
END DESCRIPTION:
XS GIS Cut Line= 3
      1908981.29       850800.60      1909578.26       850843.24
      1909710.03       850866.50
#Sta/Elev= 30
  4397.6  297.37  4412.2  296.29  4417.5  296.73  4427.0  295.36  4445.0  294.40
  4509.0  292.06  4514.9  291.01  4592.0  285.13  4634.9  283.39  4711.2  278.88
  4758.8  278.48  4767.1  277.71  4808.9  277.83  4826.7  276.86  4842.3  277.83
  4878.6  277.85  4901.3  279.10  4933.3  278.70  4952.6  276.31  4977.4  275.95
  4996.1  269.96  4998.0  268.51  4998.3  268.01  5002.0  268.51  5044.4  286.56
  5068.7  294.25  5094.2  299.80  5100.8  299.87  5113.5  302.25  5129.9  303.04
#Mann=3,-1,0
  4397.6    0.15       0  4998.0    0.05       0  5002.0    0.15       0
#XS Ineff=2,0
    0.00 4901.30  279.10               0
Permanent Ineff=
       F       F
Bank Sta=4998,5002
Exp/Cntr=0.3,0.1

Type RM Length L Ch R = 1,28500,500,500,500
BEGIN DESCRIPTION:
WATEREE CREEK 57.0
END DESCRIPTION:
XS GIS Cut Line= 3
      1908951.55       851016.46      1909397.73       851109.63
      1909758.49       851253.80
#Sta/Elev= 30
  4544.2  301.78  4573.8  298.93  4639.0  289.91  4703.6  283.72  4721.7  283.18
  4777.6  277.70  4824.7  276.55  4853.6  275.03  4886.4  276.53  4902.4  275.71
  4911.5  276.42  4962.7  276.07  4977.9  274.06  4998.0  267.88  4998.3  267.38
  5002.0  267.88  5032.1  272.35  5056.4  274.82  5066.8  277.27  5075.3  277.88
  5154.3  277.68  5188.4  278.12  5200.6  278.98  5210.3  281.13  5233.6  289.16
  5265.8  298.02  5288.1  302.39  5300.2  304.55  5378.1  312.10  5388.5  313.75
#Mann=3,-1,0
  4544.2    0.15       0  4998.0    0.05       0  5002.0    0.15       0
Bank Sta=4998,5002
Exp/Cntr=0.3,0.1

Type RM Length L Ch R = 1,28000,500,500,500
BEGIN DESCRIPTION:
WATEREE CREEK 56.0
END DESCRIPTION:
XS GIS Cut Line= 3
      1908737.90       851335.18      1909053.13       851437.09
      1909354.99       851792.90
#Sta/Elev= 30
  4668.7  321.10  4688.0  318.90  4729.1  308.72  4795.4  287.48  4814.8  279.07
  4818.0  279.03  4832.6  275.54  4866.5  274.65  4904.5  274.93  4926.4  273.88
  4938.5  274.79  4975.8  275.40  4979.7  274.97  4992.8  271.09  4998.0  266.58
  4998.3  266.08  5001.8  266.08  5002.0  266.58  5016.7  270.46  5027.9  275.19
  5039.3  275.52  5073.1  274.62  5254.4  274.74  5313.1  273.23  5333.7  274.70
  5372.9  274.61  5388.9  276.60  5425.1  286.16  5450.7  289.88  5466.6  293.54
#Mann=3,-1,0
  4668.7    0.15       0  4998.0    0.05       0  5002.0    0.15       0
#XS Ineff=2,0
       0                 5350.70    0.00  278.50
Permanent Ineff=
       F       F
Bank Sta=4998,5002
Exp/Cntr=0.3,0.1

Type RM Length L Ch R = 1,27500,600,600,600
BEGIN DESCRIPTION:
WATEREE CREEK 55.0
END DESCRIPTION:
XS GIS Cut Line= 3
      1908595.49       851789.54      1908765.56       851782.91
      1909229.52       851837.01
#Sta/Elev= 30
  4829.8  285.38  4922.4  274.15  4972.0  272.48  4977.0  271.68  4985.8  268.66
  4994.9  267.37  4998.0  265.49  4998.3  264.99  5002.0  265.49  5016.1  271.29
  5024.9  271.45  5038.2  273.38  5048.6  273.05  5056.2  271.94  5066.6  273.11
  5085.4  272.75  5102.6  273.61  5114.1  272.93  5146.6  273.00  5163.2  271.77
  5278.2  273.98  5341.9  273.32  5352.1  274.64  5389.2  284.39  5398.6  285.44
  5402.7  285.15  5414.6  286.91  5432.2  287.27  5450.3  289.78  5467.1  290.56
#Mann=3,-1,0
  4829.8    0.15       0  4998.0    0.05       0  5002.0    0.15       0
Bank Sta=4998,5002
Exp/Cntr=0.5,0.3

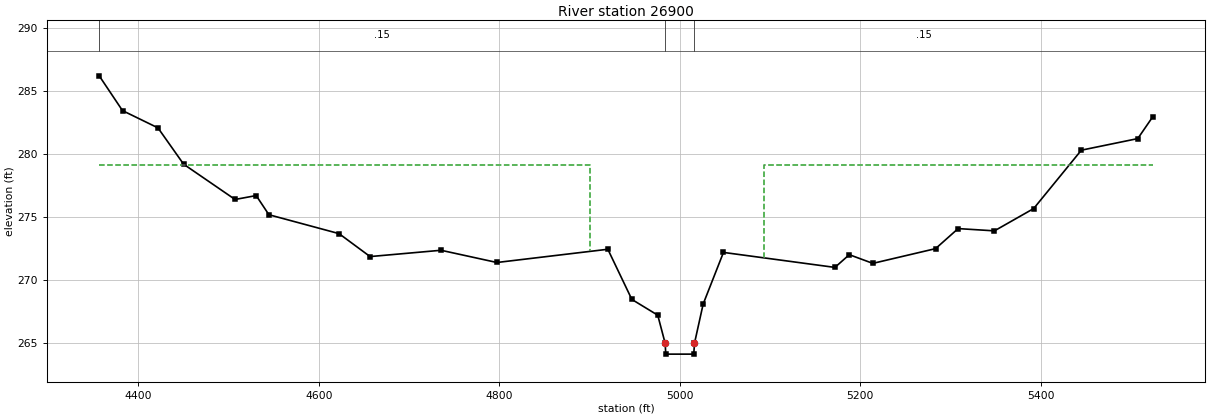
Type RM Length L Ch R = 1,26900,159,159,159
BEGIN DESCRIPTION:
WC_Chapin Rd - US
END DESCRIPTION:
XS GIS Cut Line= 6
      1908168.22       852481.26      1908705.60       852321.77
      1908788.13       852326.28      1908870.55       852281.38
      1908992.20       852220.16      1909219.40       852033.65
#Sta/Elev= 30
  4356.8  286.22  4382.6  283.46  4421.9  282.09  4450.3  279.21  4507.3  276.41
  4530.7  276.72  4544.8  275.20  4622.5  273.70  4656.9  271.88  4735.5  272.38
  4797.4  271.41  4920.3  272.46  4946.9  268.48  4975.6  267.23  4983.8  265.00
  4984.5  264.14  5015.5  264.14  5016.3  265.00  5025.9  268.11  5048.4  272.21
  5171.9  271.02  5187.8  272.03  5213.9  271.34  5283.4  272.51  5308.4  274.10
  5348.6  273.92  5392.1  275.69  5444.9  280.32  5507.4  281.24  5524.0  282.97
#Mann=3,-1,0
  4356.8    0.15       0  4983.8    0.05       0  5016.3    0.15       0
#XS Ineff=2,0
    0.00 4900.00  279.14 5093.00    0.00  279.14
Permanent Ineff=
       F       F
Bank Sta=4983.8,5016.3
Exp/Cntr=0.5,0.3