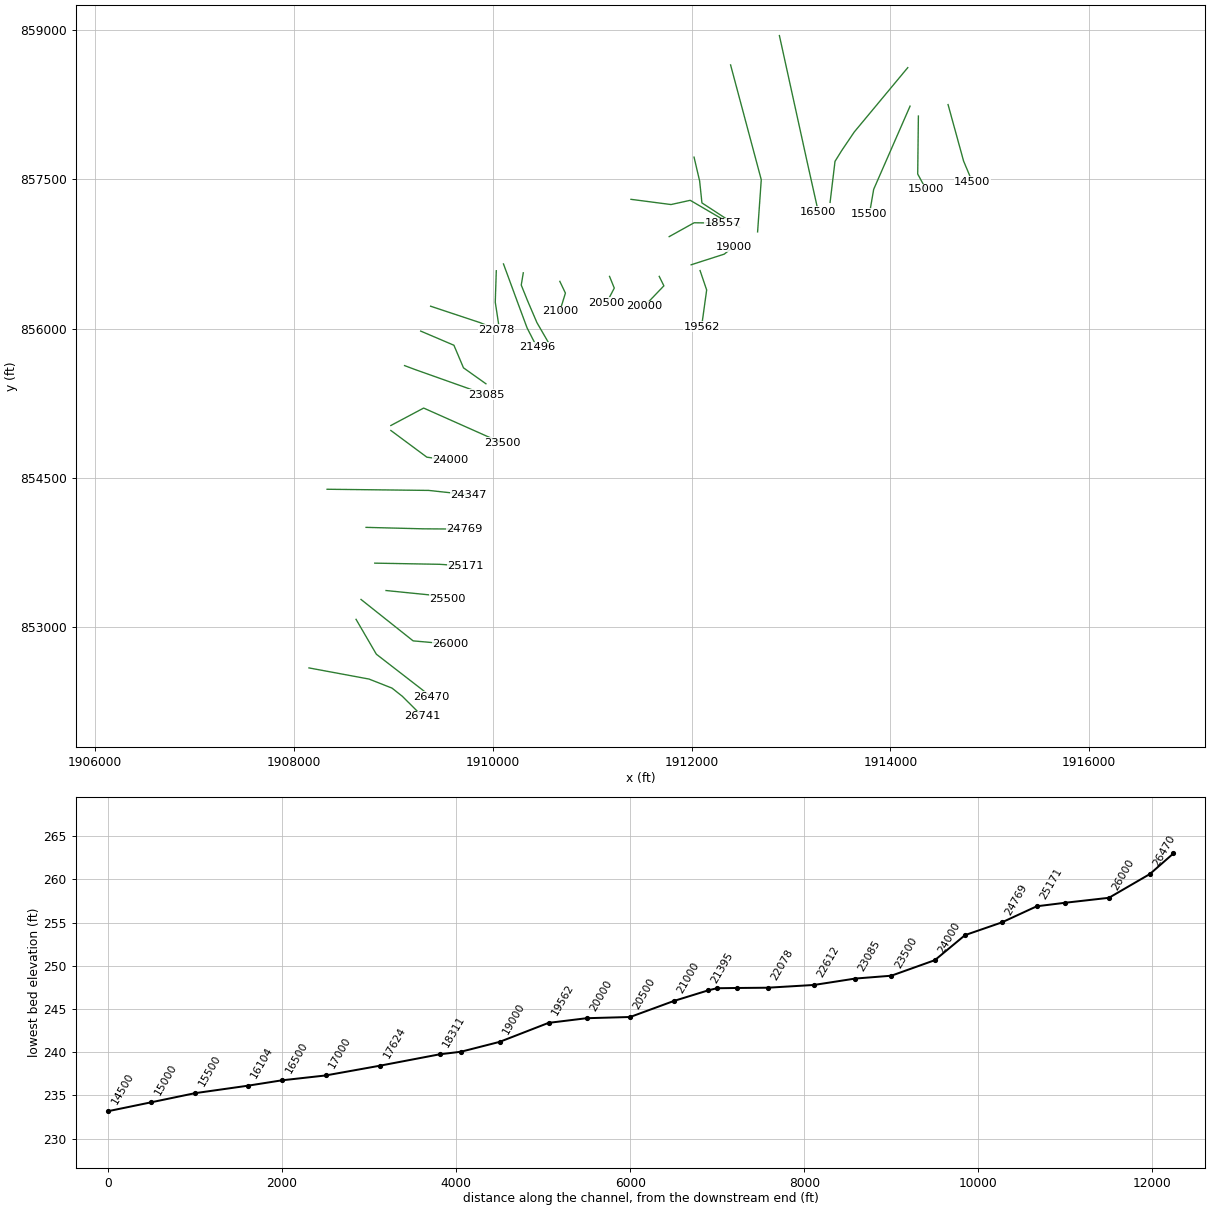
HEC-RAS study WATEREE CREEK.prj: WATEREE CREEK Limited Detail Study

--- WATEREE CREEK.g01 (geometry) --- (continued)

Type RM Length L Ch R =3,26851,,,
BEGIN DESCRIPTION:
WC_Chapin Rd - TOR
Structure ID: lds 19
Approximate Survey Structure
END DESCRIPTION:
Bridge Culvert--1,0,-1,-1,0
Deck Dist Width WeirC Skew NumUp NumDn MinLoCord MaxHiCord MaxSubmerge Is_Ogee
30.5,37,3,,12,12,,,0.95,0,1,1,,
  4323.6  4476.6  4673.2  4760.3  4940.0  4940.0  5060.0  5060.0  5081.7  5411.2
  5540.3  5610.0
  281.74  279.80  278.80  279.14  279.14  279.14  279.14  279.14  279.14  279.61
  281.97  284.65
  243.27  243.27  243.27  243.27  243.27  275.44  275.44  243.27  243.27  243.27
  243.27  243.27
  4323.6  4476.6  4673.2  4760.3  4940.0  4940.0  5060.0  5060.0  5081.7  5411.2
  5540.3  5610.0
  281.74  279.80  278.80  279.14  279.14  279.14  279.14  279.14  279.14  279.61
  281.97  284.65
  243.27  243.27  243.27  243.27  243.27  275.44  275.44  243.27  243.27  243.27
  243.27  243.27
Pier Skew, UpSta & Num, DnSta & Num=,4970,2,4970,2,0,0,0,0,0
       3       3
  264.48  275.44
       3       3
  267.49  275.44
Pier Skew, UpSta & Num, DnSta & Num=,5030,2,5030,2,0,0,0,0,0
       3       3
  268.50  275.44
       3       3
  268.00  275.44
Abutment Skew #Up #Dn=,2,2
  4940.0  4974.5
  275.44  266.97
  4940.0  4974.5
  275.44  267.64
Abutment Skew #Up #Dn=,2,2
  5025.5  5060.0
  268.02  275.44
  5025.5  5060.0
  267.33  275.44
BR Coef=1,1,0,1.25,0,,,0.8,0,2,0,
WSPro=,,,, 1 ,,,, 0 ,,,, 0 ,,,,-1 ,-1 ,-1 , 0 , 0 , 0 , 0 , 0
BC Design=,,0,,0,,,,,,

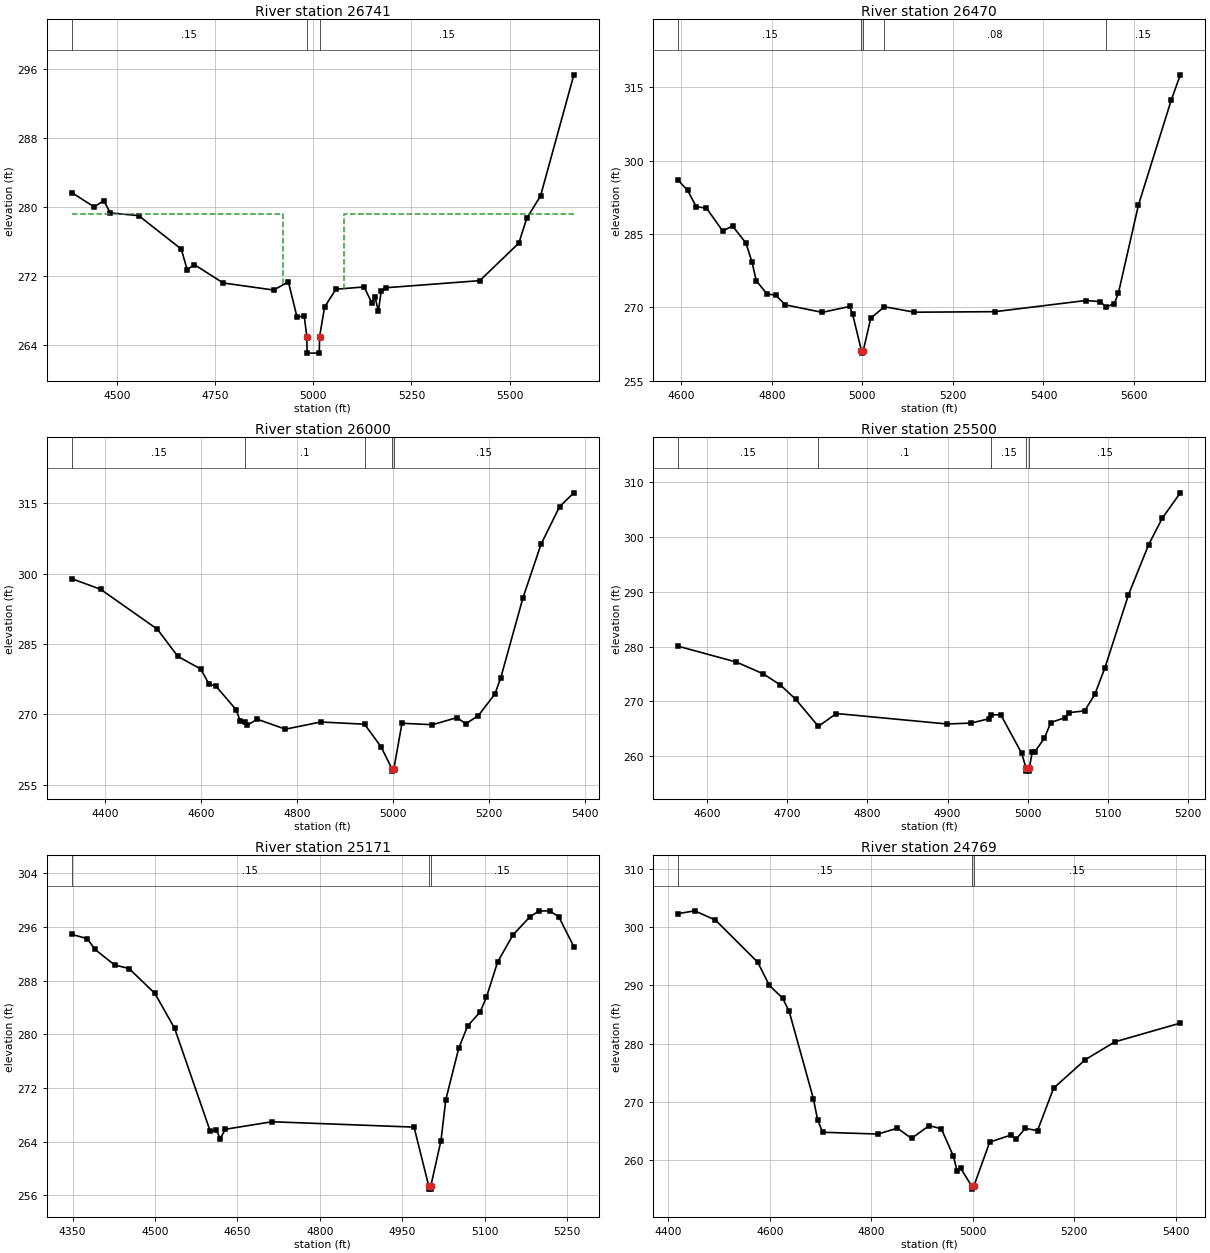
Type RM Length L Ch R = 1,26741,271,271,271
BEGIN DESCRIPTION:
WC_Chapin Rd - DS
END DESCRIPTION:
XS GIS Cut Line= 5
      1908151.29       852586.36      1908755.48       852474.29
      1908986.62       852383.18      1909090.65       852300.82
      1909290.62       852101.46
#Sta/Elev= 30
  4385.5  281.67  4442.4  280.01  4467.0  280.73  4483.6  279.31  4555.9  278.99
  4664.2  275.11  4679.3  272.72  4697.6  273.30  4770.9  271.17  4899.4  270.35
  4936.9  271.30  4958.7  267.24  4977.3  267.29  4983.8  264.95  4984.5  263.02
  5015.5  263.02  5016.3  264.95  5029.1  268.38  5057.9  270.44  5129.6  270.71
  5149.1  268.88  5157.7  269.51  5165.9  267.87  5173.0  270.18  5186.3  270.62
  5424.1  271.44  5523.5  275.80  5543.5  278.67  5578.7  281.28  5663.5  295.35
#Mann=3,-1,0
  4385.5    0.15       0  4983.8    0.05       0  5016.3    0.15       0
#XS Ineff=2,0
    0.00 4922.00  279.14 5078.00    0.00  279.14
Permanent Ineff=
       F       F
Bank Sta=4983.8,5016.3
Exp/Cntr=0.5,0.3

Type RM Length L Ch R = 1,26470,470,470,470
BEGIN DESCRIPTION:
WATEREE CREEK 53.0
END DESCRIPTION:
XS GIS Cut Line= 3
      1908624.99       853075.02      1908828.88       852724.51
      1909385.14       852293.99
#Sta/Elev= 30
  4593.3  295.96  4614.0  293.93  4633.0  290.57  4655.7  290.29  4691.4  285.62
  4713.3  286.62  4742.9  283.14  4756.3  279.23  4765.6  275.46  4789.1  272.73
  4808.4  272.49  4830.0  270.50  4911.3  268.97  4971.9  270.17  4978.5  268.56
  4998.0  261.13  4998.3  260.63  5002.0  261.13  5018.5  267.78  5048.5  270.12
  5115.0  269.00  5292.9  269.11  5493.4  271.39  5525.4  271.16  5538.3  270.05
  5556.5  270.78  5565.4  272.88  5609.7  290.91  5682.1  312.36  5702.2  317.55
#Mann=5,-1,0
  4593.3    0.15       0  4998.0    0.05       0  5002.0    0.15       0
  5048.5    0.08       0  5538.3    0.15       0
Bank Sta=4998,5002
Exp/Cntr=0.3,0.1

Type RM Length L Ch R = 1,26000,500,500,500
BEGIN DESCRIPTION:
WATEREE CREEK 52.0
END DESCRIPTION:
XS GIS Cut Line= 3
      1908675.00       853275.00      1909199.14       852858.46
      1909574.95       852825.00
#Sta/Elev= 30
  4330.5  298.93  4390.6  296.67  4509.1  288.14  4551.5  282.37  4599.4  279.66
  4616.6  276.46  4631.0  276.02  4672.8  271.02  4681.9  268.58  4692.6  268.35
  4696.1  267.67  4717.4  268.95  4775.9  266.83  4849.4  268.36  4940.9  267.89
  4975.4  263.07  4998.0  258.38  4998.3  257.88  5002.0  258.38  5019.0  268.09
  5082.3  267.78  5133.8  269.30  5151.8  267.98  5177.8  269.68  5212.6  274.31
  5224.7  277.71  5271.3  294.88  5308.9  306.28  5347.5  314.30  5377.3  317.25
#Mann=5,-1,0
  4330.5    0.15       0  4692.6     0.1       0  4940.9    0.15       0
  4998.0    0.05       0  5002.0    0.15       0
Bank Sta=4998,5002
Exp/Cntr=0.3,0.1

Type RM Length L Ch R = 1,25500,329,329,329
BEGIN DESCRIPTION:
WATEREE CREEK 51.0
END DESCRIPTION:
XS GIS Cut Line= 3
      1908926.64       853364.91      1909360.54       853321.18
      1909547.16       853282.94
#Sta/Elev= 30
  4563.9  280.07  4636.6  277.18  4670.1  275.03  4691.1  273.04  4710.5  270.40
  4738.8  265.47  4761.3  267.81  4899.6  265.90  4929.2  266.07  4952.0  266.86
  4954.8  267.56  4966.4  267.59  4992.6  260.55  4998.0  257.81  4998.3  257.31
  5001.8  257.31  5002.0  257.81  5005.7  260.78  5008.7  260.79  5020.7  263.28
  5028.9  266.16  5046.1  267.04  5051.3  267.96  5071.2  268.30  5083.9  271.34
  5096.3  276.09  5125.8  289.45  5151.0  298.59  5167.8  303.36  5190.5  308.03
#Mann=5,-1,0
  4563.9    0.15       0  4738.8     0.1       0  4954.8    0.15       0
  4998.0    0.05       0  5002.0    0.15       0
Bank Sta=4998,5002
Exp/Cntr=0.3,0.1

Type RM Length L Ch R = 1,25171,402,402,402
BEGIN DESCRIPTION:
WATEREE CREEK 50.0
END DESCRIPTION:
XS GIS Cut Line= 3
      1908813.36       853640.35      1909465.97       853628.64
      1909726.37       853611.09
#Sta/Elev= 30
  4348.5  294.89  4376.8  294.26  4390.6  292.66  4426.3  290.34  4452.7  289.80
  4499.8  286.09  4535.8  280.86  4600.4  265.55  4611.3  265.72  4618.7  264.44
  4628.0  265.83  4712.9  266.95  4971.4  266.15  4998.0  257.40  4998.3  256.90
  5001.8  256.90  5002.0  257.40  5020.4  264.14  5029.2  270.25  5052.6  277.88
  5068.8  281.22  5091.3  283.28  5103.0  285.49  5123.4  290.76  5151.3  294.80
  5182.0  297.50  5198.6  298.38  5217.9  298.41  5234.6  297.54  5262.2  293.07
#Mann=3,-1,0
  4348.5    0.15       0  4998.0    0.05       0  5002.0    0.15       0
Bank Sta=4998,5002
Exp/Cntr=0.3,0.1

Type RM Length L Ch R = 1,24769,422,422,422
BEGIN DESCRIPTION:
WATEREE CREEK 49.5
END DESCRIPTION:
XS GIS Cut Line= 3
      1908725.59       854000.29      1909296.24       853985.65
      1909714.69       853982.73
#Sta/Elev= 30
  4419.6  302.31  4452.0  302.79  4493.0  301.20  4576.2  293.97  4599.1  290.01
  4625.3  287.79  4638.1  285.56  4685.9  270.55  4694.1  266.96  4704.0  264.79
  4812.9  264.48  4851.4  265.48  4879.3  263.74  4913.9  265.92  4937.9  265.40
  4961.8  260.69  4969.0  258.16  4976.2  258.59  4998.0  255.53  4998.3  255.03
  5002.0  255.53  5033.3  263.10  5074.7  264.30  5084.9  263.57  5103.4  265.45
  5127.5  265.07  5159.2  272.35  5221.9  277.26  5280.1  280.31  5408.9  283.52
#Mann=3,-1,0
  4419.6    0.15       0  4998.0    0.05       0  5002.0    0.15       0
Bank Sta=4998,5002
Exp/Cntr=0.3,0.1

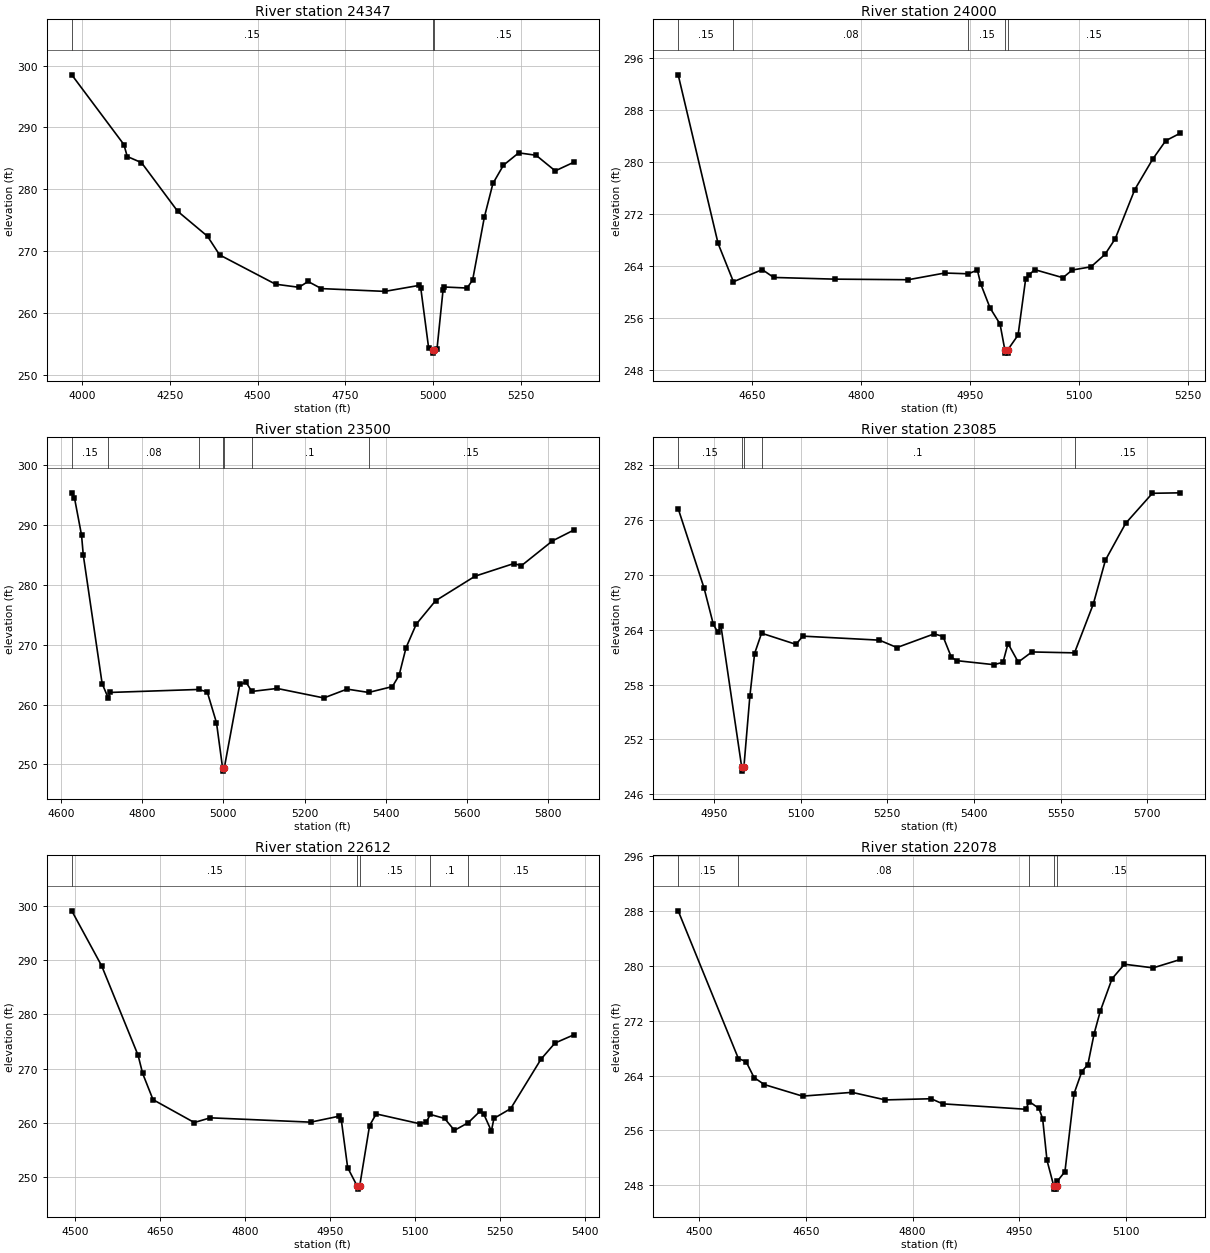
Type RM Length L Ch R = 1,24347,347,347,347
BEGIN DESCRIPTION:
WATEREE CREEK 49.0
END DESCRIPTION:
XS GIS Cut Line= 3
      1908333.47       854383.63      1909357.69       854371.93
      1909758.60       854328.03
#Sta/Elev= 30
  3971.8  298.50  4120.0  287.24  4129.5  285.31  4170.0  284.32  4273.0  276.46
  4357.7  272.43  4392.1  269.42  4551.2  264.69  4617.7  264.19  4643.6  265.13
  4681.4  263.98  4861.9  263.53  4959.7  264.50  4964.0  264.08  4986.3  254.44
  4998.0  254.06  4998.3  253.56  5002.0  254.06  5010.3  254.30  5027.5  263.83
  5030.2  264.24  5095.5  264.07  5111.4  265.35  5144.9  275.54  5169.2  280.96
  5199.1  283.91  5242.5  285.90  5291.9  285.51  5346.3  282.99  5399.4  284.39
#Mann=3,-1,0
  3971.8    0.15       0  4998.0    0.05       0  5002.0    0.15       0
Bank Sta=4998,5002
Exp/Cntr=0.3,0.1

Type RM Length L Ch R = 1,24000,500,500,500
BEGIN DESCRIPTION:
WATEREE CREEK 48.0
END DESCRIPTION:
XS GIS Cut Line= 3
      1908975.01       854974.99      1909337.63       854706.16
      1909575.00       854675.00
#Sta/Elev= 30
  4548.6  293.39  4603.5  267.50  4624.6  261.62  4664.3  263.48  4680.0  262.28
  4763.7  262.02  4865.1  261.93  4915.4  262.96  4947.7  262.84  4960.2  263.41
  4964.8  261.29  4977.7  257.59  4991.4  255.13  4998.0  251.16  4998.3  250.66
  5001.8  250.66  5002.0  251.16  5016.2  253.43  5026.6  262.01  5030.9  262.63
  5039.1  263.48  5077.9  262.24  5090.7  263.42  5116.5  263.91  5135.8  265.82
  5149.9  268.23  5176.8  275.78  5201.3  280.42  5219.3  283.27  5239.4  284.43
#Mann=5,-1,0
  4548.6    0.15       0  4624.6    0.08       0  4947.7    0.15       0
  4998.0    0.05       0  5002.0    0.15       0
Bank Sta=4998,5002
Exp/Cntr=0.3,0.1

Type RM Length L Ch R = 1,23500,415,415,415
BEGIN DESCRIPTION:
WATEREE CREEK 47.0
END DESCRIPTION:
XS GIS Cut Line= 3
      1908975.03       855025.01      1909305.08       855200.48
      1910094.20       854849.14
#Sta/Elev= 30
  4626.2  295.41  4632.9  294.55  4650.3  288.32  4654.5  285.04  4701.0  263.51
  4716.2  261.06  4720.0  262.02  4938.7  262.52  4960.1  262.11  4982.9  256.95
  4998.0  249.36  4998.3  248.86  5002.0  249.36  5040.1  263.35  5055.7  263.73
  5070.0  262.19  5132.3  262.69  5247.5  261.10  5304.7  262.58  5357.9  262.02
  5416.4  263.00  5432.9  264.88  5450.1  269.51  5475.3  273.45  5522.7  277.35
  5620.3  281.47  5715.7  283.58  5734.4  283.22  5810.9  287.37  5863.8  289.19
#Mann=7,-1,0
  4626.2    0.15       0  4716.2    0.08       0  4938.7    0.15       0
  4998.0    0.05       0  5002.0    0.15       0  5070.0     0.1       0
  5357.9    0.15       0
Bank Sta=4998,5002
Exp/Cntr=0.3,0.1

Type RM Length L Ch R = 1,23085,473,473,473
BEGIN DESCRIPTION:
WATEREE CREEK 46.0
END DESCRIPTION:
XS GIS Cut Line= 3
      1909112.99       855627.56      1909217.68       855588.32
      1909931.23       855334.94
#Sta/Elev= 30
  4888.2  277.25  4933.0  268.56  4949.1  264.58  4956.9  263.72  4962.1  264.46
  4998.0  249.03  4998.3  248.53  5002.0  249.03  5012.3  256.75  5020.5  261.40
  5032.5  263.62  5092.1  262.40  5103.9  263.30  5236.5  262.86  5266.8  262.05
  5331.3  263.55  5346.6  263.26  5360.9  261.00  5369.9  260.62  5434.3  260.18
  5450.3  260.43  5459.0  262.49  5476.7  260.46  5500.4  261.57  5574.1  261.47
  5606.6  266.81  5627.7  271.63  5662.7  275.65  5708.9  278.93  5757.2  278.98
#Mann=5,-1,0
  4888.2    0.15       0  4998.0    0.05       0  5002.0    0.15       0
  5032.5     0.1       0  5574.1    0.15       0
Bank Sta=4998,5002
Exp/Cntr=0.3,0.1

Type RM Length L Ch R = 1,22612,534,534,534
BEGIN DESCRIPTION:
WATEREE CREEK 45.0
END DESCRIPTION:
XS GIS Cut Line= 4
      1909275.04       855974.98      1909609.47       855832.38
      1909705.67       855605.20      1909931.16       855444.94
#Sta/Elev= 30
  4493.6  299.11  4546.5  288.94  4610.7  272.48  4618.8  269.12  4637.1  264.29
  4710.0  260.07  4738.2  260.94  4915.6  260.14  4965.8  261.24  4969.8  260.45
  4980.9  251.75  4998.0  248.29  4998.3  247.79  5002.0  248.29  5019.6  259.51
  5031.3  261.66  5108.1  259.85  5119.6  260.13  5126.9  261.56  5152.0  260.83
  5169.5  258.63  5193.9  260.04  5214.3  262.12  5221.4  261.61  5234.7  258.50
  5239.3  260.84  5268.8  262.63  5322.5  271.77  5347.1  274.73  5380.5  276.25
#Mann=5,-1,0
  4493.6    0.15       0  4998.0    0.05       0  5002.0    0.15       0
  5126.9     0.1       0  5193.9    0.15       0
Bank Sta=4998,5002
Exp/Cntr=0.3,0.1

Type RM Length L Ch R = 1,22078,347,347,347
BEGIN DESCRIPTION:
WATEREE CREEK 44.0
END DESCRIPTION:
XS GIS Cut Line= 3
      1909375.02       856224.99      1909874.18       856059.28
      1910039.18       855990.53
#Sta/Elev= 30
  4471.0  287.96  4555.5  266.47  4566.3  266.02  4577.5  263.70  4592.0  262.68
  4645.5  261.00  4715.1  261.55  4761.7  260.45  4826.1  260.62  4842.2  259.88
  4958.9  259.09  4963.7  260.21  4977.3  259.21  4982.5  257.71  4988.6  251.66
  4998.0  247.97  4998.3  247.47  5001.8  247.47  5002.0  247.97  5003.1  248.62
  5013.8  250.02  5026.6  261.37  5037.5  264.58  5045.9  265.57  5054.8  270.10
  5063.3  273.34  5079.9  278.08  5097.3  280.19  5137.5  279.66  5175.7  280.88
#Mann=5,-1,0
  4471.0    0.15       0  4555.5    0.08       0  4963.7    0.15       0
  4998.0    0.05       0  5002.0    0.15       0
Bank Sta=4998,5002
Exp/Cntr=0.3,0.1

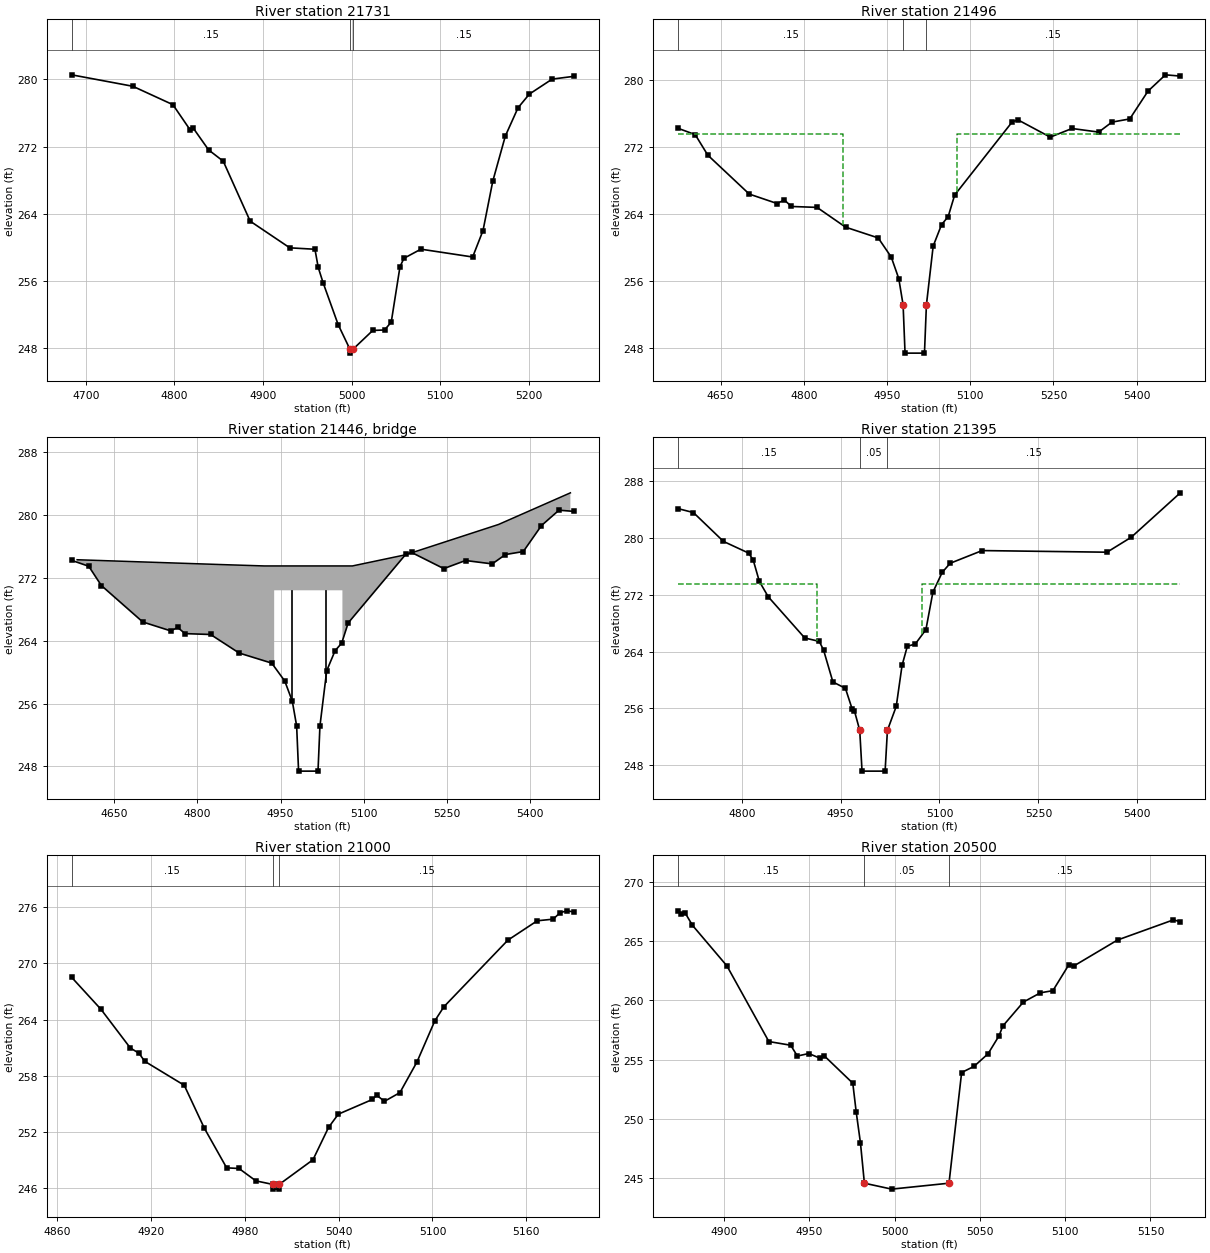
Type RM Length L Ch R = 1,21731,235,235,235
BEGIN DESCRIPTION:
WATEREE CREEK 43.0
END DESCRIPTION:
XS GIS Cut Line= 3
      1910035.76       856581.79      1910025.45       856265.55
      1910063.26       856018.03
#Sta/Elev= 30
  4684.1  280.53  4753.1  279.17  4798.4  276.98  4818.1  273.94  4821.3  274.20
  4838.7  271.60  4855.2  270.26  4885.6  263.13  4930.3  259.96  4958.7  259.79
  4962.4  257.63  4967.9  255.81  4984.9  250.83  4998.0  247.94  4998.3  247.44
  5002.0  247.94  5024.0  250.14  5037.2  250.19  5044.8  251.12  5054.7  257.73
  5059.2  258.72  5078.3  259.80  5136.7  258.87  5148.4  262.02  5159.4  267.88
  5173.6  273.26  5187.9  276.61  5200.7  278.24  5226.4  280.02  5250.9  280.35
#Mann=3,-1,0
  4684.1    0.15       0  4998.0    0.05       0  5002.0    0.15       0
Bank Sta=4998,5002
Exp/Cntr=0.5,0.3

Type RM Length L Ch R = 1,21496,101,101,101
BEGIN DESCRIPTION:
WC_Broad River Rd - US
END DESCRIPTION:
XS GIS Cut Line= 4
      1910107.96       856650.59      1910255.79       856248.36
      1910345.17       856007.71      1910444.86       855811.76
#Sta/Elev= 30
  4573.5  274.22  4604.3  273.47  4627.0  271.02  4701.7  266.38  4752.0  265.25
  4764.8  265.68  4777.8  264.90  4823.9  264.79  4875.4  262.43  4934.1  261.15
  4957.6  258.87  4971.2  256.30  4979.0  253.16  4982.5  247.41  5017.5  247.41
  5021.0  253.16  5033.2  260.18  5048.3  262.73  5060.2  263.69  5071.9  266.26
  5175.9  275.01  5186.3  275.22  5244.2  273.17  5283.4  274.20  5331.5  273.77
  5355.4  274.96  5387.5  275.34  5420.3  278.65  5451.8  280.60  5478.6  280.45
#Mann=3,-1,0
  4573.5    0.15       0  4979.0    0.05       0  5021.0    0.15       0
#XS Ineff=2,0
    0.00 4870.00  273.51 5076.00    0.00  273.51
Permanent Ineff=
       F       F
Bank Sta=4979,5021
Exp/Cntr=0.5,0.3

Type RM Length L Ch R =3,21446,,,
BEGIN DESCRIPTION:
WC_Broad River Rd - TOR
Structure ID: lds 05
Approximate Survey Structure
END DESCRIPTION:
Bridge Culvert--1,0,-1,-1,0
Deck Dist Width WeirC Skew NumUp NumDn MinLoCord MaxHiCord MaxSubmerge Is_Ogee
26.5,47,3,,11,11,,,0.95,0,1,1,,
  4583.3  4841.1  4920.8  4938.5  4938.5  5061.5  5061.5  5079.5  5175.2  5343.0
  5472.4
  274.30  273.69  273.51  273.51  273.51  273.51  273.51  273.51  274.93  278.79
  282.81
  227.41  227.41  227.41  227.41  270.41  270.41  227.41  227.41  227.41  227.41
  227.41
  4583.3  4841.1  4920.8  4938.5  4938.5  5061.5  5061.5  5079.5  5175.2  5343.0
  5472.4
  274.30  273.69  273.51  273.51  273.51  273.51  273.51  273.51  274.93  278.79
  282.81
  227.41  227.41  227.41  227.41  270.41  270.41  227.41  227.41  227.41  227.41
  227.41
Pier Skew, UpSta & Num, DnSta & Num=,4969.3,2,4969.3,2,0,0,0,0,0
     2.2     2.2
  256.86  270.41
     2.2     2.2
  255.78  270.41
Pier Skew, UpSta & Num, DnSta & Num=,5030.8,2,5030.8,2,0,0,0,0,0
     2.2     2.2
  258.50  270.41
     2.2     2.2
  255.26  270.41
Abutment Skew #Up #Dn=,2,2
  4938.5  4971.5
  270.41  256.48
  4938.5  4971.5
  270.41  255.98
Abutment Skew #Up #Dn=,2,2
  5028.5  5061.5
  257.70  270.41
  5028.5  5061.5
  254.57  270.41
BR Coef=1,1,0,1.25,0,,,0.8,0,2,0,
WSPro=,,,, 1 ,,,, 0 ,,,, 0 ,,,,-1 ,-1 ,-1 , 0 , 0 , 0 , 0 , 0
BC Design=,,0,,0,,,,,,

Type RM Length L Ch R = 1,21395,395,395,395
BEGIN DESCRIPTION:
WC_Broad River Rd - DS
END DESCRIPTION:
XS GIS Cut Line= 5
      1910307.36       856561.21      1910286.73       856437.44
      1910352.05       856275.86      1910444.87       856059.28
      1910558.31       855863.34
#Sta/Elev= 30
  4703.5  284.16  4726.7  283.61  4772.3  279.54  4810.4  277.90  4817.4  276.92
  4826.7  273.91  4840.2  271.74  4895.6  265.93  4917.6  265.45  4924.1  264.24
  4938.3  259.73  4957.3  258.83  4967.5  255.92  4971.0  255.64  4979.0  252.91
  4982.5  247.16  5017.5  247.16  5021.0  252.91  5034.4  256.29  5043.2  262.06
  5051.2  264.76  5063.3  265.08  5079.4  267.11  5090.0  272.39  5104.2  275.19
  5116.2  276.46  5164.7  278.25  5354.1  278.02  5390.9  280.13  5465.3  286.39
#Mann=3,-1,0
  4703.5    0.15       0  4979.0    0.05       0  5021.0    0.15       0
#XS Ineff=2,0
    0.00 4914.00  273.51 5074.00    0.00  273.51
Permanent Ineff=
       F       F
Bank Sta=4979,5021
Exp/Cntr=0.5,0.3

Type RM Length L Ch R = 1,21000,500,500,500
BEGIN DESCRIPTION:
WATEREE CREEK 42.0
END DESCRIPTION:
XS GIS Cut Line= 3
      1910675.00       856475.00      1910731.12       856356.97
      1910675.01       856175.02
#Sta/Elev= 30
  4869.3  268.51  4888.1  265.09  4906.8  260.98  4912.4  260.41  4916.0  259.56
  4941.3  257.00  4954.1  252.44  4968.4  248.20  4976.3  248.13  4987.1  246.81
  4998.0  246.43  4998.3  245.93  5001.8  245.93  5002.0  246.43  5023.6  249.06
  5033.6  252.52  5039.8  253.92  5061.6  255.49  5064.3  255.95  5069.3  255.29
  5079.2  256.22  5090.1  259.49  5101.5  263.87  5107.3  265.37  5148.2  272.47
  5167.0  274.54  5177.1  274.71  5181.8  275.42  5186.2  275.60  5190.4  275.48
#Mann=3,-1,0
  4869.3    0.15       0  4998.0    0.05       0  5002.0    0.15       0
Bank Sta=4998,5002
Exp/Cntr=0.3,0.1

Type RM Length L Ch R = 1,20500,500,500,500
BEGIN DESCRIPTION:
WATEREE CREEK 41.0
END DESCRIPTION:
XS GIS Cut Line= 3
      1911175.01       856524.98      1911222.63       856407.35
      1911144.98       856258.94
#Sta/Elev= 30
  4873.1  267.54  4874.9  267.26  4877.1  267.39  4881.5  266.32  4901.7  262.90
  4926.3  256.52  4939.1  256.21  4943.0  255.30  4949.7  255.51  4956.4  255.11
  4958.9  255.30  4975.5  253.01  4977.5  250.58  4980.0  247.97  4982.3  244.58
  4998.3  244.08  5031.9  244.58  5039.3  253.91  5046.6  254.43  5054.8  255.49
  5061.3  257.02  5063.4  257.82  5075.5  259.85  5085.5  260.63  5092.8  260.81
  5102.1  262.98  5105.3  262.91  5130.7  265.08  5163.5  266.78  5167.5  266.62
#Mann=3,-1,0
  4873.1    0.15       0  4982.3    0.05       0  5031.9    0.15       0
Bank Sta=4982.3,5031.9
Exp/Cntr=0.3,0.1

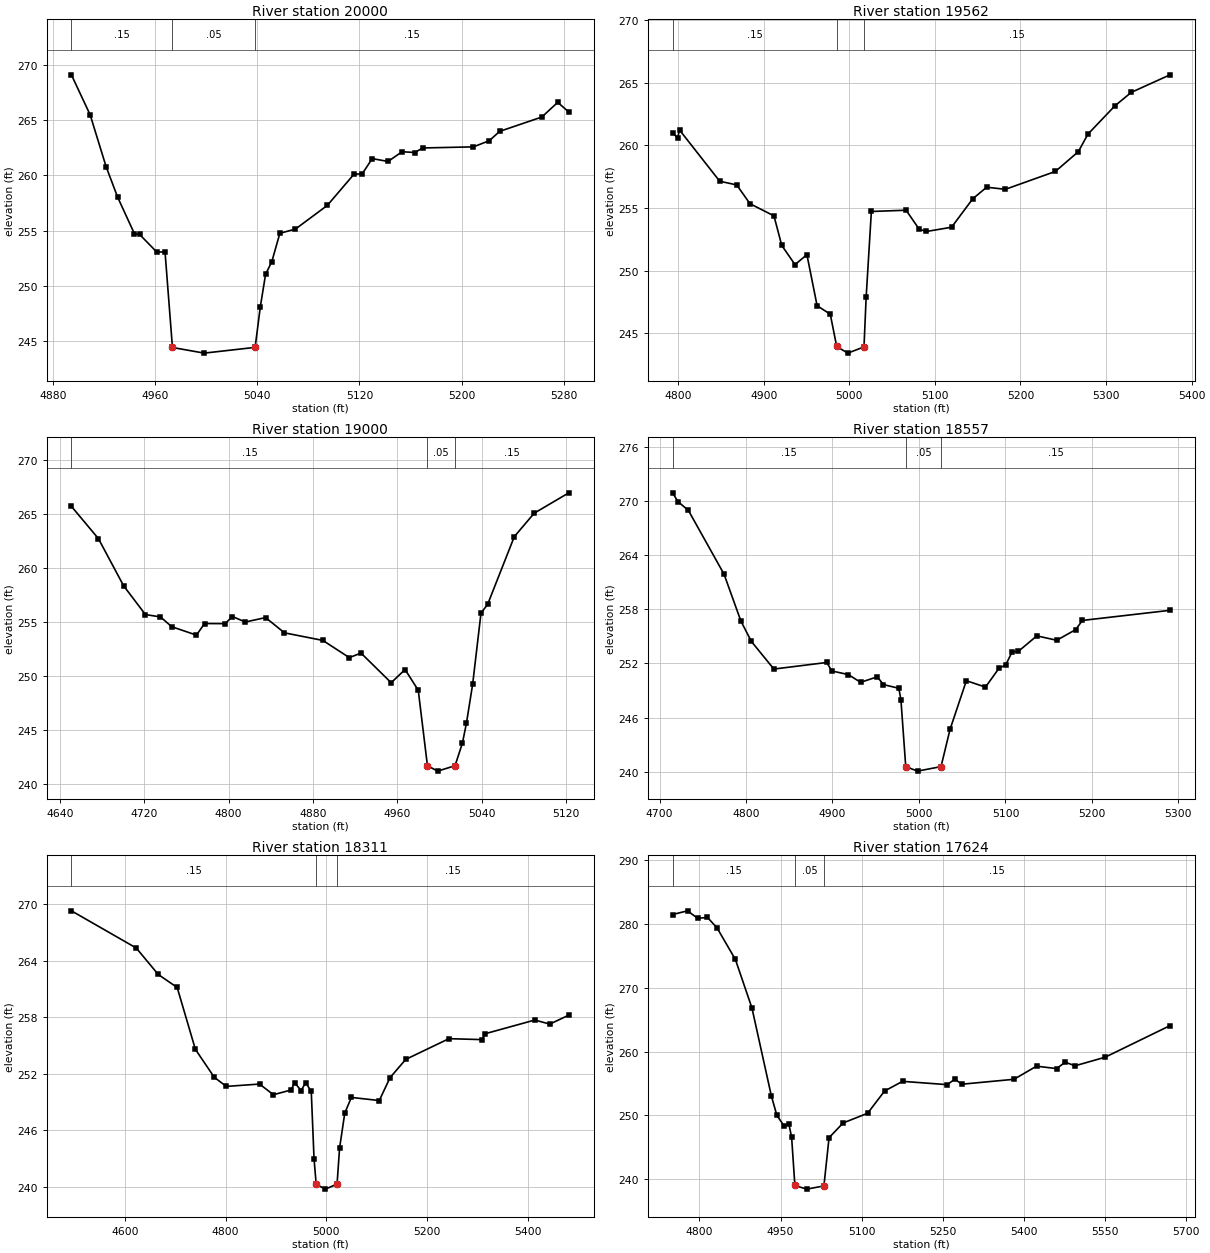
Type RM Length L Ch R = 1,20000,438,438,438
BEGIN DESCRIPTION:
WATEREE CREEK 40.0
END DESCRIPTION:
XS GIS Cut Line= 3
      1911675.00       856525.00      1911721.66       856430.04
      1911525.01       856225.01
#Sta/Elev= 30
  4894.2  269.09  4908.9  265.47  4921.4  260.79  4930.4  258.04  4943.6  254.73
  4947.6  254.67  4961.0  253.09  4967.6  253.07  4973.4  244.45  4998.3  243.94
  5038.2  244.46  5042.3  248.14  5046.4  251.06  5051.3  252.21  5057.6  254.77
  5069.8  255.15  5094.8  257.29  5115.7  260.11  5122.2  260.15  5130.0  261.52
  5142.4  261.26  5153.4  262.14  5163.4  262.07  5169.6  262.48  5209.3  262.58
  5221.8  263.14  5229.9  263.98  5263.0  265.28  5275.4  266.60  5284.1  265.73
#Mann=3,-1,0
  4894.2    0.15       0  4973.4    0.05       0  5038.2    0.15       0
Bank Sta=4973.4,5038.2
Exp/Cntr=0.3,0.1

Type RM Length L Ch R = 1,19562,562,562,562
BEGIN DESCRIPTION:
WATEREE CREEK 39.0
END DESCRIPTION:
XS GIS Cut Line= 3
      1912085.73       856583.74      1912152.04       856388.28
      1912100.65       856017.12
#Sta/Elev= 30
  4793.6  260.97  4799.5  260.62  4801.7  261.23  4848.6  257.14  4868.5  256.84
  4884.0  255.34  4912.0  254.37  4921.1  252.01  4936.6  250.47  4950.5  251.27
  4962.4  247.19  4977.8  246.51  4985.3  243.93  4998.3  243.40  5017.2  243.90
  5019.7  247.86  5025.8  254.72  5066.4  254.82  5081.6  253.31  5090.0  253.12
  5119.5  253.46  5144.2  255.73  5160.5  256.66  5182.3  256.49  5240.8  257.92
  5267.6  259.50  5278.8  260.90  5310.3  263.16  5329.5  264.24  5374.7  265.64
#Mann=3,-1,0
  4793.6    0.15       0  4985.3    0.05       0  5017.2    0.15       0
Bank Sta=4985.3,5017.2
Exp/Cntr=0.3,0.1

Type RM Length L Ch R = 1,19000,443,443,443
BEGIN DESCRIPTION:
WATEREE CREEK 38.0
END DESCRIPTION:
XS GIS Cut Line= 3
      1911996.40       856642.01      1912328.75       856748.84
      1912424.97       856824.98
#Sta/Elev= 30
  4650.9  265.67  4676.5  262.69  4700.4  258.33  4721.1  255.67  4735.4  255.45
  4746.0  254.55  4769.5  253.77  4777.2  254.84  4796.7  254.83  4803.6  255.49
  4815.8  254.98  4835.1  255.39  4853.0  253.98  4889.4  253.28  4914.5  251.69
  4925.6  252.11  4954.2  249.37  4967.4  250.59  4979.9  248.67  4988.6  241.70
  4998.3  241.20  5014.8  241.70  5021.8  243.80  5025.6  245.63  5031.5  249.24
  5039.4  255.81  5045.7  256.61  5071.0  262.87  5089.9  265.04  5122.7  266.92
#Mann=3,-1,0
  4650.9    0.15       0  4988.6    0.05       0  5014.8    0.15       0
Bank Sta=4988.6,5014.8
Exp/Cntr=0.3,0.1

Type RM Length L Ch R = 1,18557,246,246,246
BEGIN DESCRIPTION:
WATEREE CREEK 37.0
END DESCRIPTION:
XS GIS Cut Line= 3
      1911775.01       856925.01      1912025.87       857064.46
      1912314.03       857061.19
#Sta/Elev= 30
  4715.1  270.90  4721.3  269.92  4733.3  268.96  4774.6  261.88  4794.1  256.68
  4806.2  254.43  4832.2  251.37  4893.4  252.10  4899.2  251.16  4918.3  250.76
  4932.5  249.90  4951.8  250.51  4958.9  249.65  4976.7  249.24  4979.1  247.99
  4984.7  240.56  4998.3  240.06  5025.5  240.56  5035.9  244.68  5054.8  250.08
  5076.9  249.37  5092.7  251.48  5100.3  251.82  5107.7  253.28  5114.9  253.33
  5136.3  255.05  5159.3  254.56  5181.2  255.74  5189.0  256.76  5290.3  257.88
#Mann=3,-1,0
  4715.1    0.15       0  4984.7    0.05       0  5025.5    0.15       0
Bank Sta=4984.7,5025.5
Exp/Cntr=0.3,0.1

Type RM Length L Ch R = 1,18311,687,687,687
BEGIN DESCRIPTION:
WATEREE CREEK 36.0
END DESCRIPTION:
XS GIS Cut Line= 4
      1911390.57       857300.25      1911793.36       857247.85
      1911986.57       857290.43      1912317.34       857097.20
#Sta/Elev= 30
  4494.2  269.32  4622.9  265.37  4666.5  262.56  4704.1  261.18  4740.2  254.61
  4777.7  251.64  4801.6  250.67  4867.5  250.92  4895.1  249.79  4930.3  250.29
  4937.1  251.07  4950.1  250.23  4959.1  251.08  4970.2  250.13  4975.7  242.98
  4980.0  240.26  4998.3  239.76  5021.4  240.30  5026.4  244.13  5036.7  247.84
  5049.8  249.50  5105.2  249.17  5126.5  251.60  5157.7  253.54  5243.4  255.74
  5309.5  255.64  5314.9  256.26  5413.8  257.72  5443.6  257.29  5481.3  258.24
#Mann=3,-1,0
  4494.2    0.15       0  4980.0    0.05       0  5021.4    0.15       0
Bank Sta=4980,5021.4
Exp/Cntr=0.3,0.1

Type RM Length L Ch R = 1,17624,624,624,624
BEGIN DESCRIPTION:
WATEREE CREEK 35.0
END DESCRIPTION:
XS GIS Cut Line= 4
      1912025.01       857724.96      1912081.54       857483.64
      1912104.47       857264.23      1912482.71       857017.98
#Sta/Elev= 30
  4750.3  281.52  4777.9  282.10  4796.6  280.93  4814.8  281.06  4832.5  279.42
  4866.4  274.47  4897.0  266.86  4933.0  253.03  4943.1  250.01  4956.6  248.33
  4965.4  248.63  4970.4  246.56  4976.4  239.01  4998.3  238.44  5030.1  238.94
  5039.6  246.51  5065.6  248.82  5110.9  250.34  5142.3  253.83  5175.5  255.35
  5258.1  254.83  5272.2  255.69  5285.2  254.90  5381.5  255.67  5423.3  257.73
  5460.3  257.35  5476.3  258.35  5494.5  257.79  5550.0  259.13  5670.1  264.09
#Mann=3,-1,0
  4750.3    0.15       0  4976.4    0.05       0  5030.1    0.15       0
Bank Sta=4976.4,5030.1
Exp/Cntr=0.3,0.1

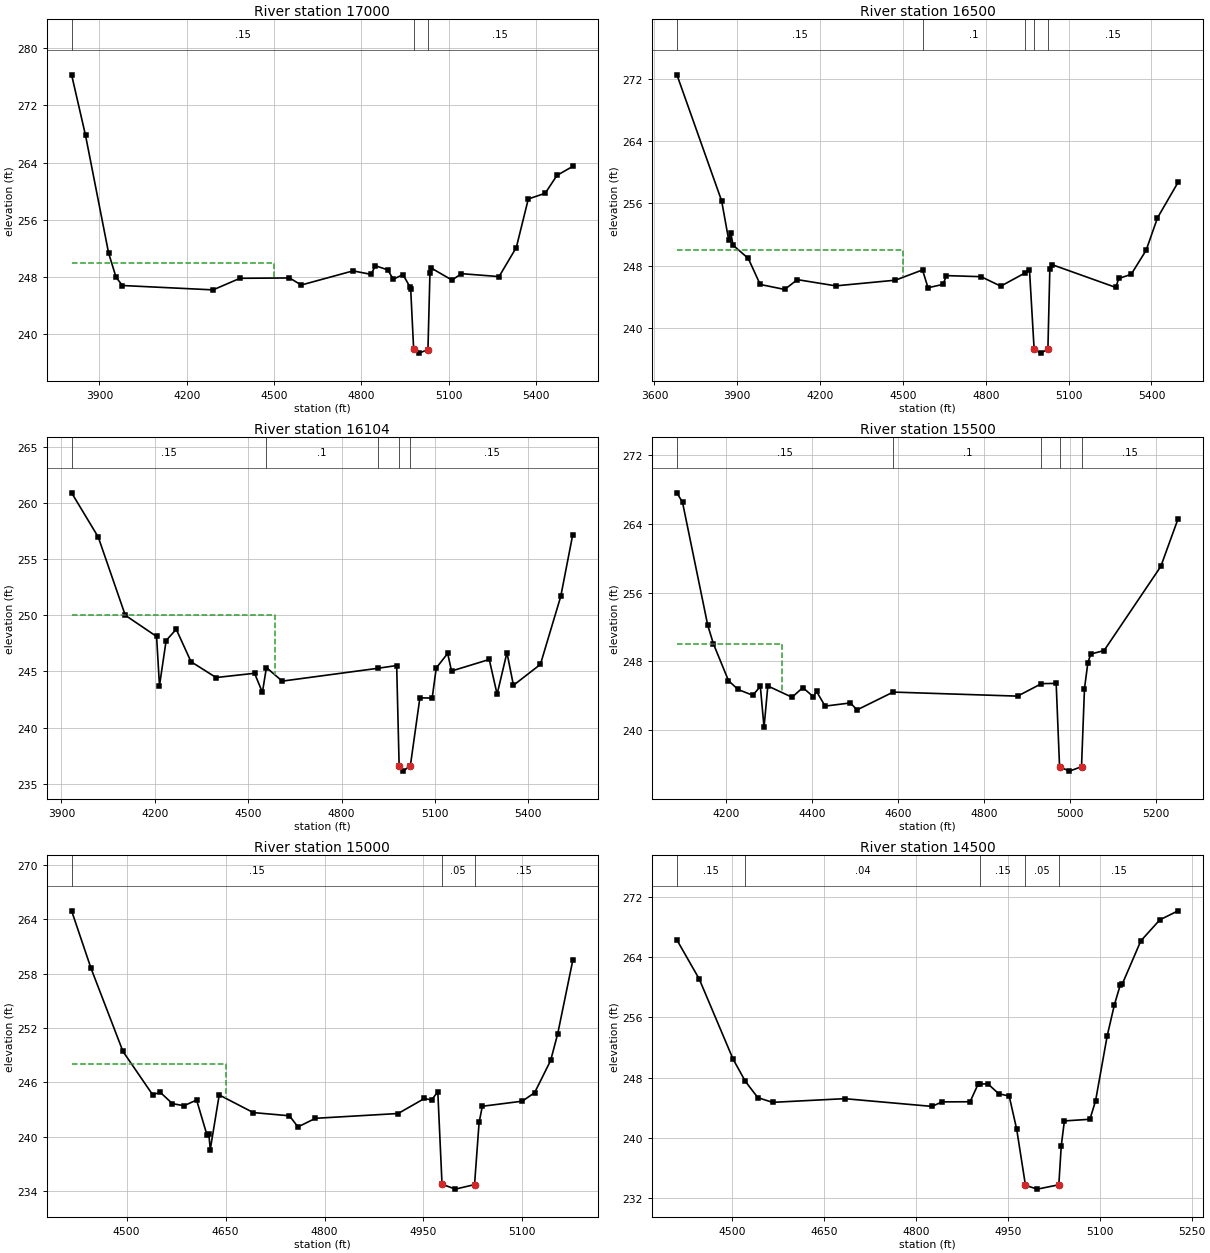
Type RM Length L Ch R = 1,17000,500,500,500
BEGIN DESCRIPTION:
WATEREE CREEK 34.0
END DESCRIPTION:
XS GIS Cut Line= 3
      1912392.66       858652.72      1912701.29       857497.85
      1912664.46       856972.74
#Sta/Elev= 30
  3804.6  276.29  3852.5  267.80  3931.8  251.31  3957.4  247.93  3979.2  246.78
  4290.6  246.17  4383.0  247.79  4553.2  247.84  4593.7  246.85  4771.4  248.83
  4833.6  248.34  4848.1  249.55  4891.2  248.97  4909.4  247.65  4943.0  248.31
  4967.6  246.55  4969.6  246.30  4979.8  237.82  4998.3  237.31  5028.9  237.81
  5035.8  248.59  5040.0  249.23  5111.6  247.54  5144.0  248.44  5273.2  248.03
  5332.4  252.10  5373.7  258.90  5431.7  259.70  5472.1  262.20  5526.4  263.47
#Mann=3,-1,0
  3804.6    0.15       0  4979.8    0.05       0  5028.9    0.15       0
#XS Ineff=2,0
    0.00 4500.00  250.00               0
Permanent Ineff=
       F       F
Bank Sta=4979.8,5028.9
Exp/Cntr=0.3,0.1

Type RM Length L Ch R = 1,16500,396,396,396
BEGIN DESCRIPTION:
WATEREE CREEK 33.0
END DESCRIPTION:
XS GIS Cut Line= 3
      1912883.89       858947.46      1913166.79       857659.56
      1913275.00       857175.00
#Sta/Elev= 30
  3681.4  272.54  3843.3  256.33  3869.1  251.26  3876.2  252.25  3884.6  250.63
  3939.8  248.93  3982.9  245.58  4071.6  244.94  4117.7  246.20  4256.6  245.40
  4472.5  246.13  4570.9  247.45  4590.7  245.16  4645.5  245.59  4657.3  246.72
  4783.1  246.58  4854.3  245.36  4942.6  247.07  4958.2  247.50  4975.1  237.25
  4998.3  236.75  5025.0  237.25  5032.0  247.60  5039.2  248.14  5270.8  245.20
  5281.5  246.35  5326.6  246.88  5380.8  249.98  5421.9  254.15  5496.5  258.72
#Mann=5,-1,0
  3681.4    0.15       0  4570.9     0.1       0  4942.6    0.15       0
  4975.1    0.05       0  5025.0    0.15       0
#XS Ineff=2,0
    0.00 4500.00  250.00               0
Permanent Ineff=
       F       F
Bank Sta=4975.1,5025
Exp/Cntr=0.3,0.1

Type RM Length L Ch R = 1,16104,604,604,604
BEGIN DESCRIPTION:
WATEREE CREEK 32.0
END DESCRIPTION:
XS GIS Cut Line= 5
      1914175.02       858625.03      1913636.80       857977.63
      1913510.49       857790.71      1913443.31       857682.68
      1913393.76       857269.76
#Sta/Elev= 30
  3932.5  260.92  4018.1  256.98  4105.0  250.01  4205.6  248.12  4214.9  243.74
  4236.4  247.76  4268.8  248.76  4316.3  245.87  4396.8  244.46  4520.5  244.84
  4545.7  243.14  4558.6  245.35  4609.4  244.14  4915.7  245.28  4977.2  245.53
  4985.1  236.62  4998.3  236.12  5021.3  236.62  5051.8  242.65  5091.3  242.63
  5104.4  245.31  5141.1  246.61  5153.5  245.04  5274.7  246.07  5300.0  242.97
  5331.6  246.68  5352.5  243.77  5439.1  245.63  5504.5  251.69  5543.1  257.20
#Mann=5,-1,0
  3932.5    0.15       0  4558.6     0.1       0  4915.7    0.15       0
  4985.1    0.05       0  5021.3    0.15       0
#XS Ineff=2,0
    0.00 4585.00  250.00               0
Permanent Ineff=
       F       F
Bank Sta=4985.1,5021.3
Exp/Cntr=0.3,0.1

Type RM Length L Ch R = 1,15500,500,500,500
BEGIN DESCRIPTION:
WATEREE CREEK 31.0
END DESCRIPTION:
XS GIS Cut Line= 3
      1914198.11       858237.75      1913832.13       857400.66
      1913789.52       857153.40
#Sta/Elev= 30
  4086.4  267.58  4099.4  266.47  4158.0  252.20  4171.2  250.04  4206.2  245.77
  4228.4  244.74  4262.7  244.07  4280.2  245.10  4288.8  240.34  4297.6  245.15
  4353.9  243.84  4378.9  244.96  4403.4  243.90  4410.8  244.52  4430.7  242.81
  4489.4  243.18  4504.9  242.37  4588.8  244.44  4878.0  243.97  4933.5  245.42
  4967.6  245.45  4975.5  235.76  4998.3  235.26  5026.5  235.77  5033.4  244.85
  5041.3  247.87  5048.1  248.86  5078.9  249.26  5210.7  259.03  5250.9  264.57
#Mann=5,-1,0
  4086.4    0.15       0  4588.8     0.1       0  4933.5    0.15       0
  4975.5    0.05       0  5026.5    0.15       0
#XS Ineff=2,0
    0.00 4330.00  250.00               0
Permanent Ineff=
       F       F
Bank Sta=4975.5,5026.5
Exp/Cntr=0.3,0.1

Type RM Length L Ch R = 1,15000,500,500,500
BEGIN DESCRIPTION:
WATEREE CREEK 30.0
END DESCRIPTION:
XS GIS Cut Line= 3
      1914281.94       858138.24      1914275.17       857554.78
      1914359.59       857400.01
#Sta/Elev= 30
  4416.5  264.94  4445.9  258.60  4494.4  249.41  4539.3  244.64  4550.9  244.90
  4569.3  243.65  4587.0  243.42  4606.0  244.05  4621.9  240.15  4624.6  240.29
  4626.7  238.57  4640.3  244.61  4692.0  242.66  4746.7  242.31  4759.7  241.08
  4786.2  242.03  4911.6  242.56  4951.4  244.22  4962.2  244.05  4971.7  244.96
  4978.1  234.75  4998.3  234.21  5027.4  234.71  5034.3  241.57  5039.2  243.36
  5099.7  243.92  5118.5  244.86  5142.8  248.42  5153.5  251.37  5176.3  259.46
#Mann=3,-1,0
  4416.5    0.15       0  4978.1    0.05       0  5027.4    0.15       0
#XS Ineff=2,0
    0.00 4650.00  248.00               0
Permanent Ineff=
       F       F
Bank Sta=4978.1,5027.4
Exp/Cntr=0.3,0.1

Type RM Length L Ch R = 1,14500,500,500,500
BEGIN DESCRIPTION:
WATEREE CREEK 29.0
END DESCRIPTION:
XS GIS Cut Line= 3
      1914580.54       858253.49      1914736.82       857685.09
      1914824.98       857475.04
#Sta/Elev= 30
  4410.5  266.30  4446.8  261.12  4502.0  250.47  4522.1  247.50  4542.4  245.34
  4566.4  244.71  4684.0  245.20  4826.5  244.17  4842.8  244.77  4888.6  244.79
  4901.5  247.10  4905.2  247.15  4917.6  247.17  4935.5  245.84  4952.3  245.56
  4964.6  241.13  4978.9  233.67  4998.3  233.17  5033.3  233.75  5037.3  238.97
  5042.4  242.24  5084.0  242.46  5093.2  244.90  5112.2  253.56  5124.0  257.71
  5133.4  260.29  5136.5  260.39  5167.0  266.18  5198.0  268.98  5227.8  270.18
#Mann=5,-1,0
  4410.5    0.15       0  4522.1    0.04       0  4905.2    0.15       0
  4978.9    0.05       0  5033.3    0.15       0
#XS Ineff=2,0
    0.00 4913.90  247.08               0
Permanent Ineff=
       F       F
Bank Sta=4978.9,5033.3
Exp/Cntr=0.3,0.1