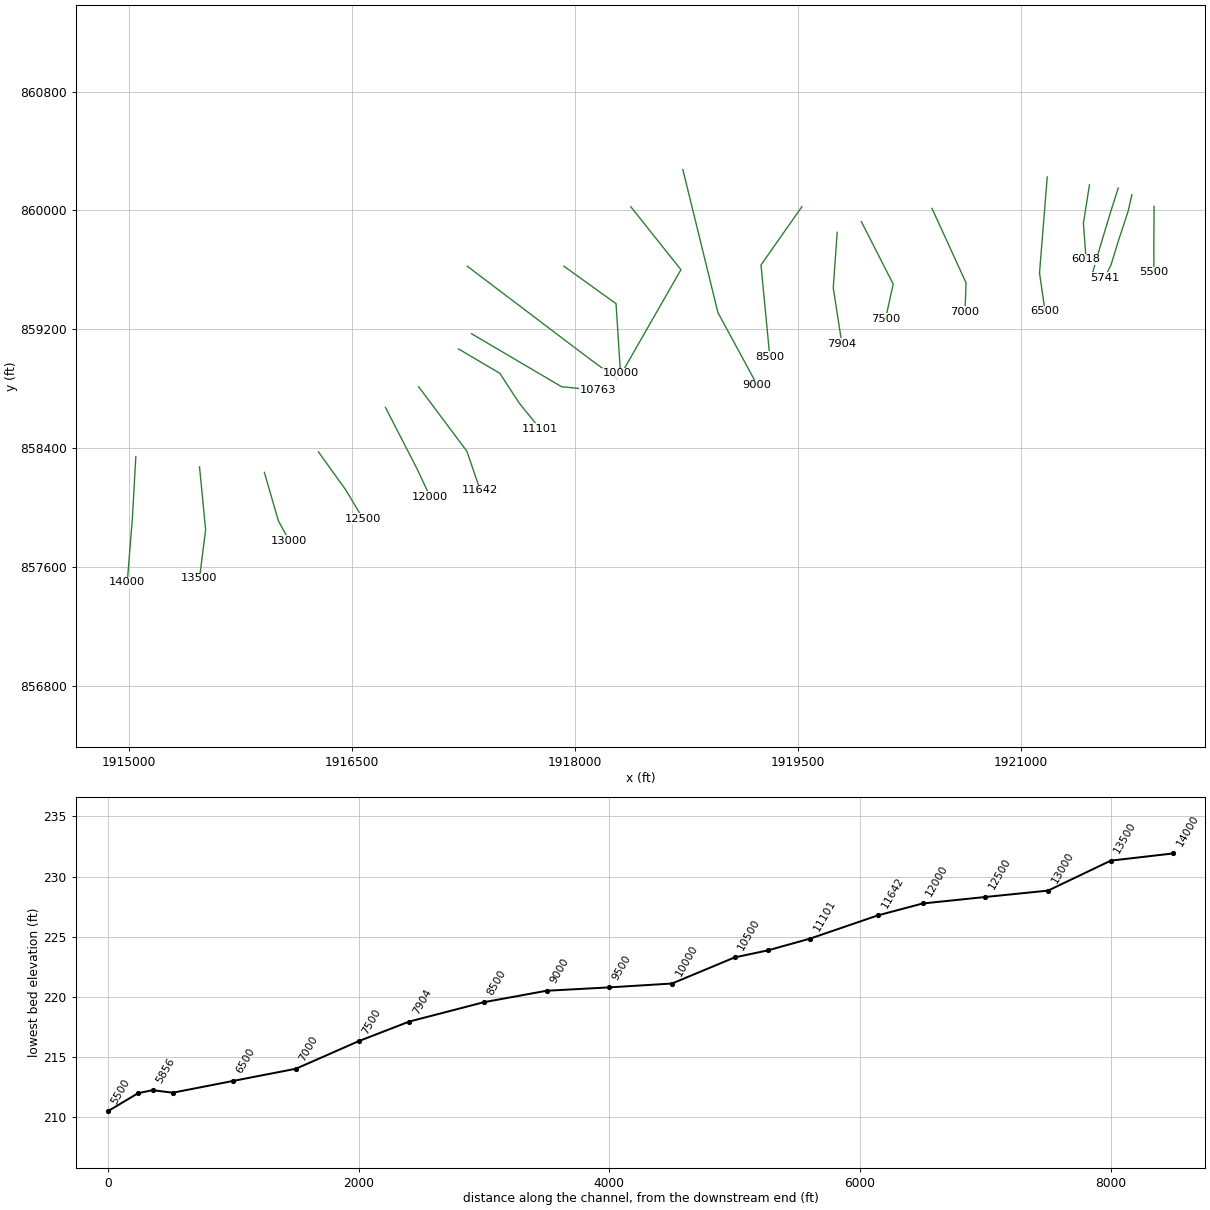
HEC-RAS study WATEREE CREEK.prj: WATEREE CREEK Limited Detail Study

--- WATEREE CREEK.g01 (geometry) --- (continued)

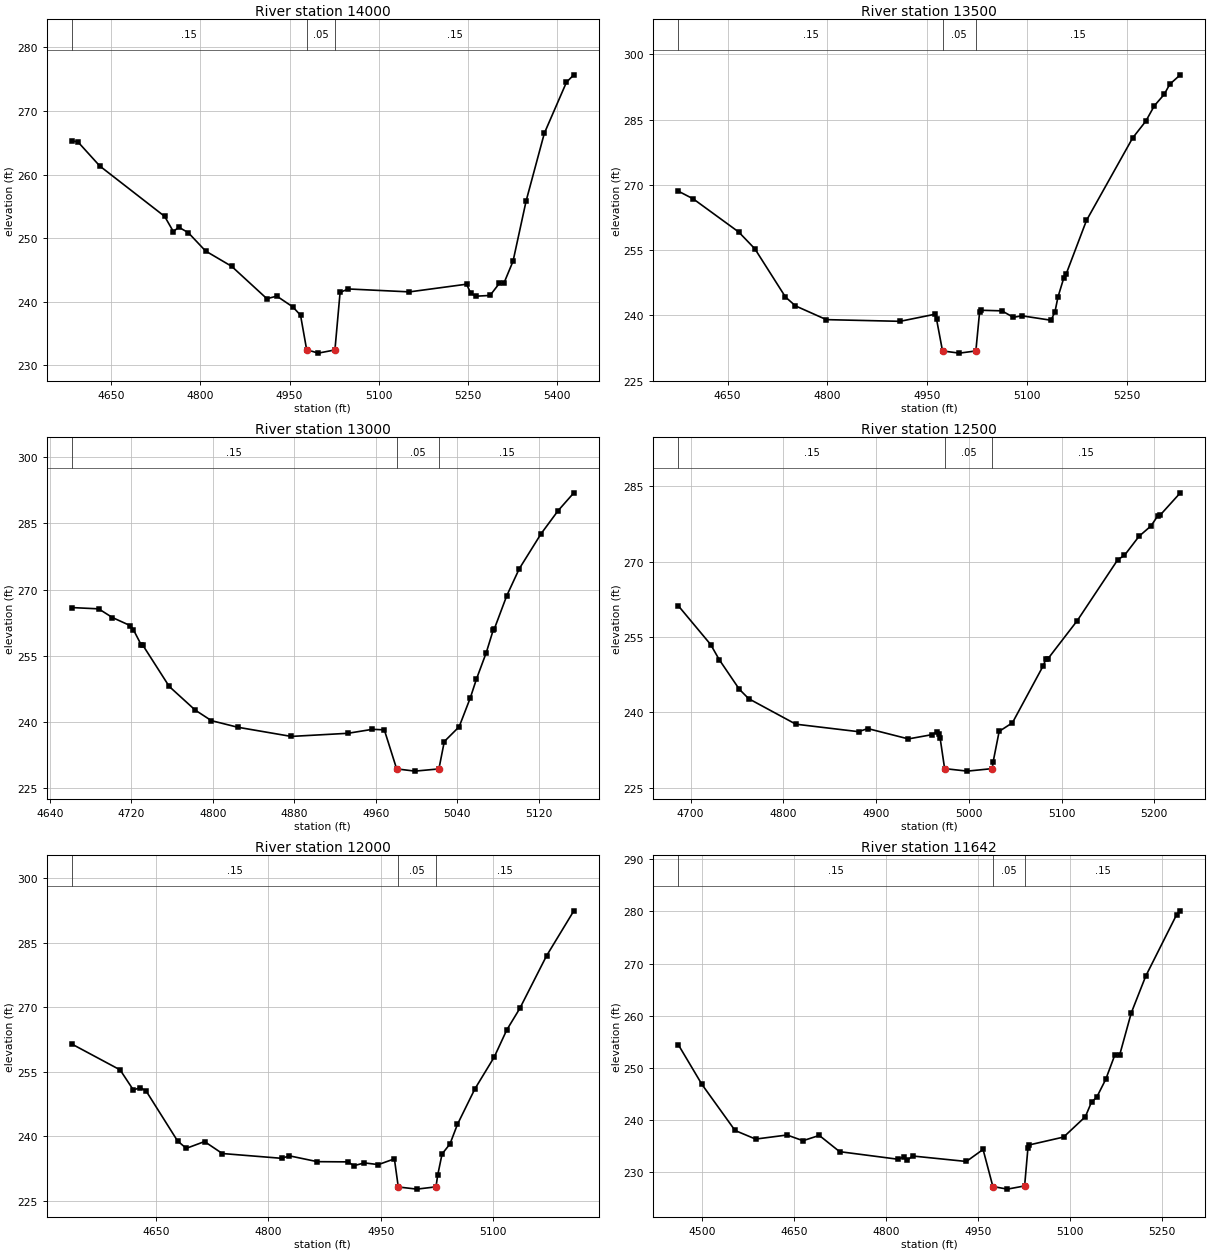
Type RM Length L Ch R = 1,14000,500,500,500
BEGIN DESCRIPTION:
WATEREE CREEK 28.0
END DESCRIPTION:
XS GIS Cut Line= 3
      1915046.77       858342.50      1915023.48       857926.45
      1914989.15       857499.13
#Sta/Elev= 30
  4583.3  265.31  4593.7  265.13  4630.5  261.34  4739.7  253.42  4754.3  251.04
  4763.6  251.72  4779.6  250.85  4808.6  247.98  4852.5  245.57  4911.8  240.48
  4928.6  240.88  4955.5  239.19  4968.5  237.88  4978.8  232.46  4998.3  231.92
  5026.4  232.42  5035.1  241.47  5049.0  242.01  5151.9  241.55  5248.2  242.76
  5254.8  241.37  5263.4  240.87  5287.6  240.99  5303.1  242.87  5311.1  242.95
  5326.3  246.37  5348.4  255.87  5379.0  266.49  5416.3  274.52  5428.7  275.68
#Mann=3,-1,0
  4583.3    0.15       0  4978.8    0.05       0  5026.4    0.15       0
Bank Sta=4978.8,5026.4
Exp/Cntr=0.3,0.1

Type RM Length L Ch R = 1,13500,500,500,500
BEGIN DESCRIPTION:
WATEREE CREEK 27.0
END DESCRIPTION:
XS GIS Cut Line= 3
      1915475.00       858275.03      1915516.02       857852.72
      1915475.00       857524.97
#Sta/Elev= 30
  4575.7  268.56  4598.2  266.78  4666.6  259.16  4690.9  255.29  4736.9  244.21
  4751.9  242.18  4798.3  239.02  4909.1  238.63  4961.6  240.26  4964.0  239.06
  4972.9  231.82  4998.3  231.32  5023.0  231.82  5028.6  240.72  5031.1  241.17
  5062.2  241.04  5079.4  239.54  5092.0  239.90  5136.0  238.88  5141.9  240.81
  5146.4  244.20  5155.3  248.67  5159.0  249.61  5189.3  261.83  5258.7  280.79
  5278.4  284.63  5291.3  288.18  5306.0  290.78  5314.5  293.13  5330.3  295.29
#Mann=3,-1,0
  4575.7    0.15       0  4972.9    0.05       0  5023.0    0.15       0
Bank Sta=4972.9,5023
Exp/Cntr=0.3,0.1

Type RM Length L Ch R = 1,13000,500,500,500
BEGIN DESCRIPTION:
WATEREE CREEK 26.0
END DESCRIPTION:
XS GIS Cut Line= 3
      1915911.14       858237.76      1916005.03       857912.44
      1916078.77       857776.78
#Sta/Elev= 30
  4661.4  265.92  4687.8  265.63  4701.3  263.66  4718.6  261.85  4721.9  260.91
  4729.4  257.54  4731.0  257.45  4757.1  248.03  4782.6  242.67  4798.5  240.28
  4824.2  238.79  4876.9  236.70  4932.6  237.41  4956.6  238.31  4968.3  238.19
  4980.4  229.34  4998.3  228.83  5021.9  229.33  5027.2  235.54  5041.8  238.90
  5052.8  245.49  5058.8  249.73  5068.4  255.70  5075.1  260.73  5076.4  261.13
  5088.6  268.65  5100.8  274.72  5122.3  282.69  5139.0  287.91  5154.4  291.94
#Mann=3,-1,0
  4661.4    0.15       0  4980.4    0.05       0  5021.9    0.15       0
Bank Sta=4980.4,5021.9
Exp/Cntr=0.3,0.1

Type RM Length L Ch R = 1,12500,500,500,500
BEGIN DESCRIPTION:
WATEREE CREEK 25.0
END DESCRIPTION:
XS GIS Cut Line= 3
      1916274.98       858375.02      1916457.69       858120.51
      1916575.00       857925.01
#Sta/Elev= 30
  4686.7  261.22  4721.7  253.48  4730.9  250.48  4752.6  244.58  4762.7  242.71
  4813.5  237.64  4881.1  236.15  4891.0  236.77  4934.8  234.71  4959.8  235.54
  4966.2  236.12  4968.0  235.71  4969.0  234.93  4973.9  228.80  4998.3  228.30
  5025.3  228.80  5026.1  230.05  5032.7  236.21  5047.0  237.92  5080.3  249.30
  5083.2  250.65  5085.5  250.71  5117.0  258.27  5160.6  270.38  5167.7  271.22
  5183.6  275.05  5196.4  277.09  5203.7  279.10  5206.0  279.19  5228.0  283.68
#Mann=3,-1,0
  4686.7    0.15       0  4973.9    0.05       0  5025.3    0.15       0
Bank Sta=4973.9,5025.3
Exp/Cntr=0.3,0.1

Type RM Length L Ch R = 1,12000,358,358,358
BEGIN DESCRIPTION:
WATEREE CREEK 24.0
END DESCRIPTION:
XS GIS Cut Line= 3
      1916724.99       858675.01      1916936.61       858263.43
      1917024.99       858075.03
#Sta/Elev= 30
  4537.2  261.47  4601.8  255.46  4619.5  250.79  4629.0  251.35  4636.8  250.49
  4678.5  238.97  4690.2  237.23  4714.6  238.81  4738.4  236.03  4817.5  234.92
  4828.1  235.49  4865.3  234.14  4906.2  234.09  4914.2  233.21  4928.3  233.85
  4946.9  233.46  4968.3  234.79  4973.5  228.26  4998.3  227.76  5023.9  228.29
  5026.1  230.95  5032.0  235.92  5042.6  238.26  5052.6  242.82  5075.8  251.02
  5101.7  258.44  5118.5  264.75  5135.9  269.74  5171.6  281.95  5208.1  292.41
#Mann=3,-1,0
  4537.2    0.15       0  4973.5    0.05       0  5023.9    0.15       0
Bank Sta=4973.5,5023.9
Exp/Cntr=0.3,0.1

Type RM Length L Ch R = 1,11642,541,541,541
BEGIN DESCRIPTION:
WATEREE CREEK 23.0
END DESCRIPTION:
XS GIS Cut Line= 3
      1916948.38       858814.00      1917273.16       858379.22
      1917362.23       858117.24
#Sta/Elev= 30
  4461.2  254.47  4499.9  246.83  4553.9  238.01  4587.5  236.36  4638.8  237.14
  4664.8  236.05  4691.4  237.06  4724.6  233.95  4820.4  232.49  4828.9  232.97
  4834.9  232.29  4843.6  233.12  4931.4  232.07  4958.7  234.37  4974.7  227.27
  4998.3  226.77  5026.5  227.38  5031.9  234.63  5033.7  235.23  5090.2  236.75
  5125.7  240.66  5135.7  243.46  5144.1  244.36  5158.9  247.81  5173.7  252.47
  5181.6  252.47  5200.5  260.52  5224.1  267.57  5274.4  279.32  5280.6  280.10
#Mann=3,-1,0
  4461.2    0.15       0  4974.7    0.05       0  5026.5    0.15       0
Bank Sta=4974.7,5026.5
Exp/Cntr=0.3,0.1

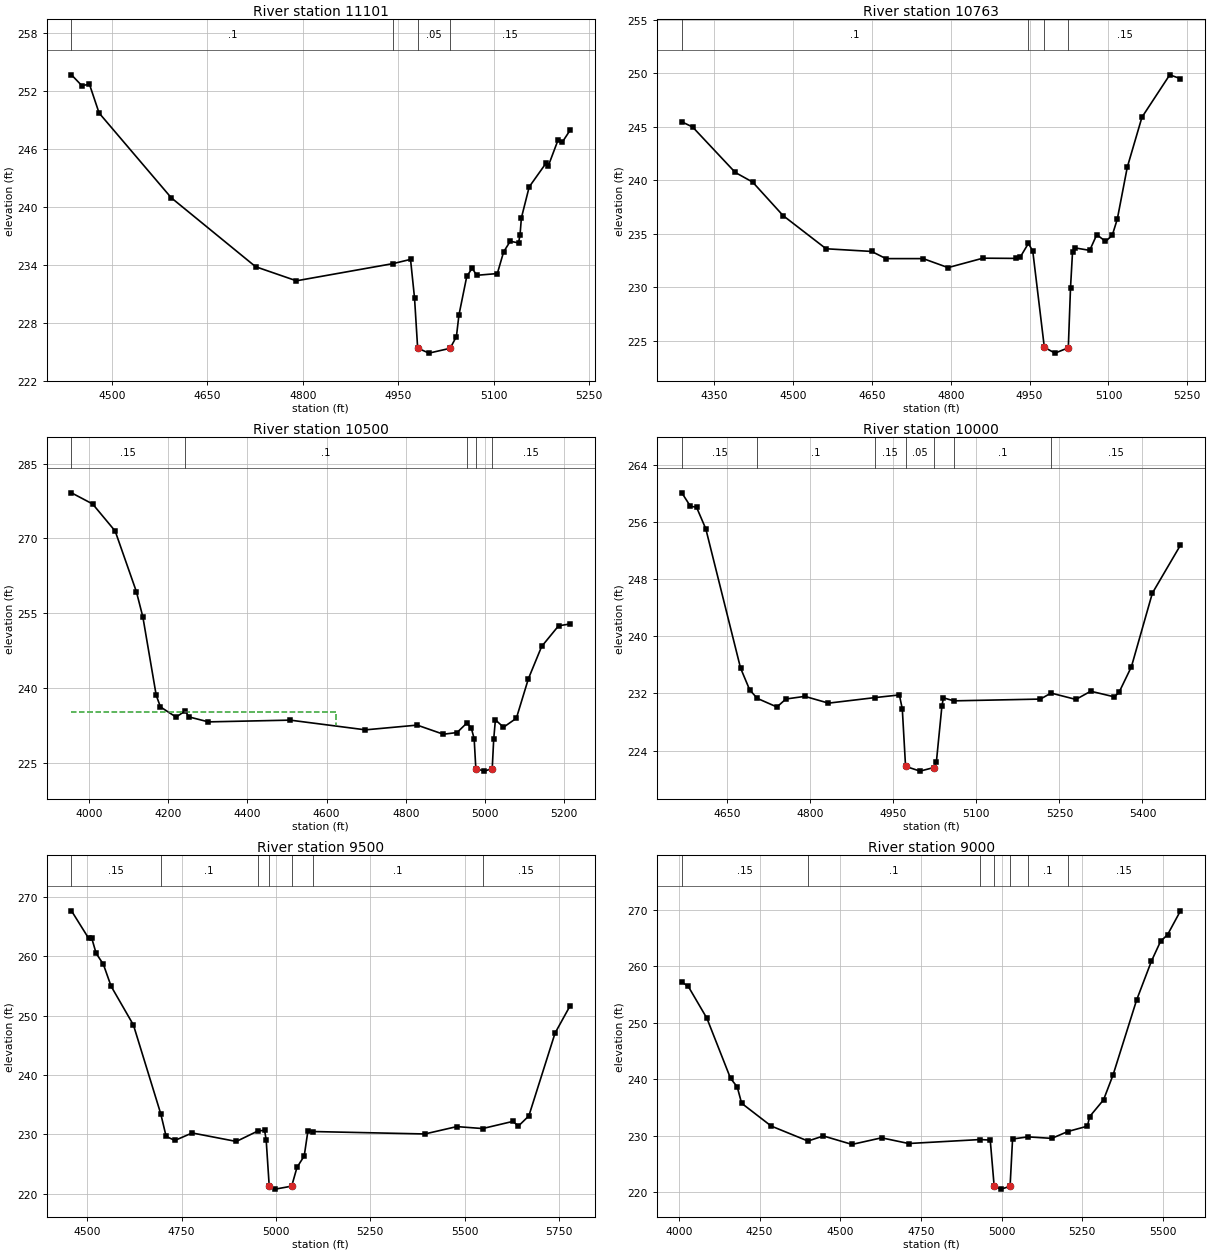
Type RM Length L Ch R = 1,11101,338,338,338
BEGIN DESCRIPTION:
WATEREE CREEK 22.5
END DESCRIPTION:
XS GIS Cut Line= 4
      1917216.74       859068.16      1917494.48       858904.13
      1917625.88       858702.17      1917764.72       858531.39
#Sta/Elev= 30
  4436.5  253.70  4452.6  252.59  4464.8  252.71  4479.9  249.74  4593.3  240.95
  4725.9  233.80  4790.0  232.34  4942.3  234.13  4969.3  234.56  4975.6  230.56
  4980.5  225.36  4998.3  224.84  5031.5  225.34  5041.4  226.55  5045.4  228.80
  5057.7  232.80  5066.2  233.65  5073.2  232.91  5105.7  233.09  5115.6  235.34
  5126.0  236.44  5139.0  236.27  5141.4  237.09  5143.5  238.86  5155.8  242.08
  5182.6  244.57  5185.9  244.27  5201.0  246.92  5207.9  246.73  5220.1  247.96
#Mann=4,-1,0
  4436.5     0.1       0  4942.3    0.15       0  4980.5    0.05       0
  5031.5    0.15       0
Bank Sta=4980.5,5031.5
Exp/Cntr=0.3,0.1

Type RM Length L Ch R = 1,10763,263,263,263
BEGIN DESCRIPTION:
WATEREE CREEK 22.0
END DESCRIPTION:
XS GIS Cut Line= 3
      1917304.56       859170.26      1917909.43       858813.96
      1918154.80       858789.42
#Sta/Elev= 30
  4288.4  245.47  4309.0  244.98  4390.0  240.74  4423.1  239.84  4481.0  236.71
  4562.8  233.61  4649.5  233.36  4676.6  232.69  4747.5  232.69  4794.8  231.85
  4861.1  232.73  4923.6  232.71  4932.5  232.86  4947.7  234.11  4956.0  233.39
  4978.0  224.40  4998.3  223.86  5023.6  224.36  5027.8  229.97  5031.6  233.28
  5036.5  233.69  5064.3  233.46  5077.8  234.93  5094.3  234.30  5107.1  234.85
  5116.8  236.38  5135.8  241.23  5163.7  245.90  5216.6  249.86  5237.0  249.50
#Mann=4,-1,0
  4288.4     0.1       0  4947.7    0.15       0  4978.0    0.05       0
  5023.6    0.15       0
Bank Sta=4978,5023.6
Exp/Cntr=0.3,0.1

Type RM Length L Ch R = 1,10500,500,500,500
BEGIN DESCRIPTION:
WATEREE CREEK 21.0
END DESCRIPTION:
XS GIS Cut Line= 3
      1917274.99       859625.01      1918107.05       858994.60
      1918280.98       858868.73
#Sta/Elev= 30
  3956.1  279.17  4009.5  276.93  4066.4  271.49  4119.9  259.33  4136.3  254.23
  4170.0  238.51  4180.6  236.18  4220.1  234.13  4243.3  235.37  4252.1  234.18
  4301.8  233.17  4508.2  233.52  4698.1  231.57  4828.7  232.52  4894.7  230.69
  4929.3  231.03  4953.8  232.92  4965.0  232.01  4972.5  229.78  4976.7  223.78
  4998.3  223.28  5018.1  223.80  5021.8  229.66  5026.1  233.59  5046.5  232.09
  5079.0  233.90  5109.4  241.84  5142.8  248.31  5185.6  252.47  5214.7  252.83
#Mann=5,-1,0
  3956.1    0.15       0  4243.3     0.1       0  4953.8    0.15       0
  4976.7    0.05       0  5018.1    0.15       0
#XS Ineff=2,0
    0.00 4623.80  235.06               0
Permanent Ineff=
       F       F
Bank Sta=4976.7,5018.1
Exp/Cntr=0.3,0.1

Type RM Length L Ch R = 1,10000,500,500,500
BEGIN DESCRIPTION:
WATEREE CREEK 20.0
END DESCRIPTION:
XS GIS Cut Line= 3
      1917924.99       859625.01      1918275.76       859372.85
      1918305.54       858905.10
#Sta/Elev= 30
  4568.0  260.12  4583.5  258.23  4594.5  258.11  4611.3  255.07  4674.0  235.57
  4690.5  232.51  4704.2  231.31  4739.8  230.10  4756.0  231.22  4790.2  231.59
  4832.9  230.64  4916.1  231.41  4960.9  231.79  4966.2  229.85  4972.1  221.78
  4998.3  221.11  5022.9  221.61  5027.8  222.41  5037.8  230.25  5040.5  231.39
  5059.1  230.96  5215.7  231.21  5234.9  232.05  5279.8  231.16  5306.6  232.31
  5349.2  231.52  5357.7  232.15  5380.1  235.75  5417.9  246.06  5468.7  252.79
#Mann=7,-1,0
  4568.0    0.15       0  4704.2     0.1       0  4916.1    0.15       0
  4972.1    0.05       0  5022.9    0.15       0  5059.1     0.1       0
  5234.9    0.15       0
Bank Sta=4972.1,5022.9
Exp/Cntr=0.3,0.1

Type RM Length L Ch R = 1,9500,500,500,500
BEGIN DESCRIPTION:
WATEREE CREEK 19.0
END DESCRIPTION:
XS GIS Cut Line= 3
      1918375.00       860025.00      1918712.01       859601.27
      1918324.99       858924.98
#Sta/Elev= 30
  4458.6  267.61  4503.9  263.00  4511.8  263.12  4523.9  260.46  4543.1  258.61
  4563.5  254.93  4622.7  248.40  4695.0  233.47  4709.3  229.66  4732.4  228.98
  4778.3  230.24  4895.2  228.81  4951.3  230.54  4969.9  230.70  4974.2  229.11
  4982.3  221.29  4998.3  220.79  5041.8  221.29  5055.8  224.44  5075.0  226.37
  5084.9  230.64  5098.4  230.48  5394.4  230.07  5479.2  231.31  5547.4  230.98
  5627.3  232.18  5642.4  231.41  5669.9  233.11  5739.3  247.04  5779.2  251.64
#Mann=7,-1,0
  4458.6    0.15       0  4695.0     0.1       0  4951.3    0.15       0
  4982.3    0.05       0  5041.8    0.15       0  5098.4     0.1       0
  5547.4    0.15       0
Bank Sta=4982.3,5041.8
Exp/Cntr=0.3,0.1

Type RM Length L Ch R = 1,9000,500,500,500
BEGIN DESCRIPTION:
WATEREE CREEK 18.0
END DESCRIPTION:
XS GIS Cut Line= 3
      1918725.00       860274.99      1918960.89       859312.48
      1919224.99       858825.02
#Sta/Elev= 30
  4009.0  257.25  4029.1  256.45  4086.7  250.81  4160.0  240.15  4180.6  238.65
  4194.3  235.74  4285.9  231.70  4399.9  229.04  4447.6  229.94  4536.4  228.44
  4628.0  229.61  4711.9  228.60  4932.6  229.30  4964.8  229.21  4977.0  221.01
  4998.3  220.51  5026.3  221.01  5034.0  229.40  5081.7  229.78  5155.4  229.51
  5205.4  230.73  5266.0  231.68  5272.8  233.37  5315.9  236.34  5345.6  240.79
  5418.5  254.06  5464.3  260.94  5492.6  264.45  5514.5  265.65  5554.4  269.87
#Mann=7,-1,0
  4009.0    0.15       0  4399.9     0.1       0  4932.6    0.15       0
  4977.0    0.05       0  5026.3    0.15       0  5081.7     0.1       0
  5205.4    0.15       0
Bank Sta=4977,5026.3
Exp/Cntr=0.3,0.1

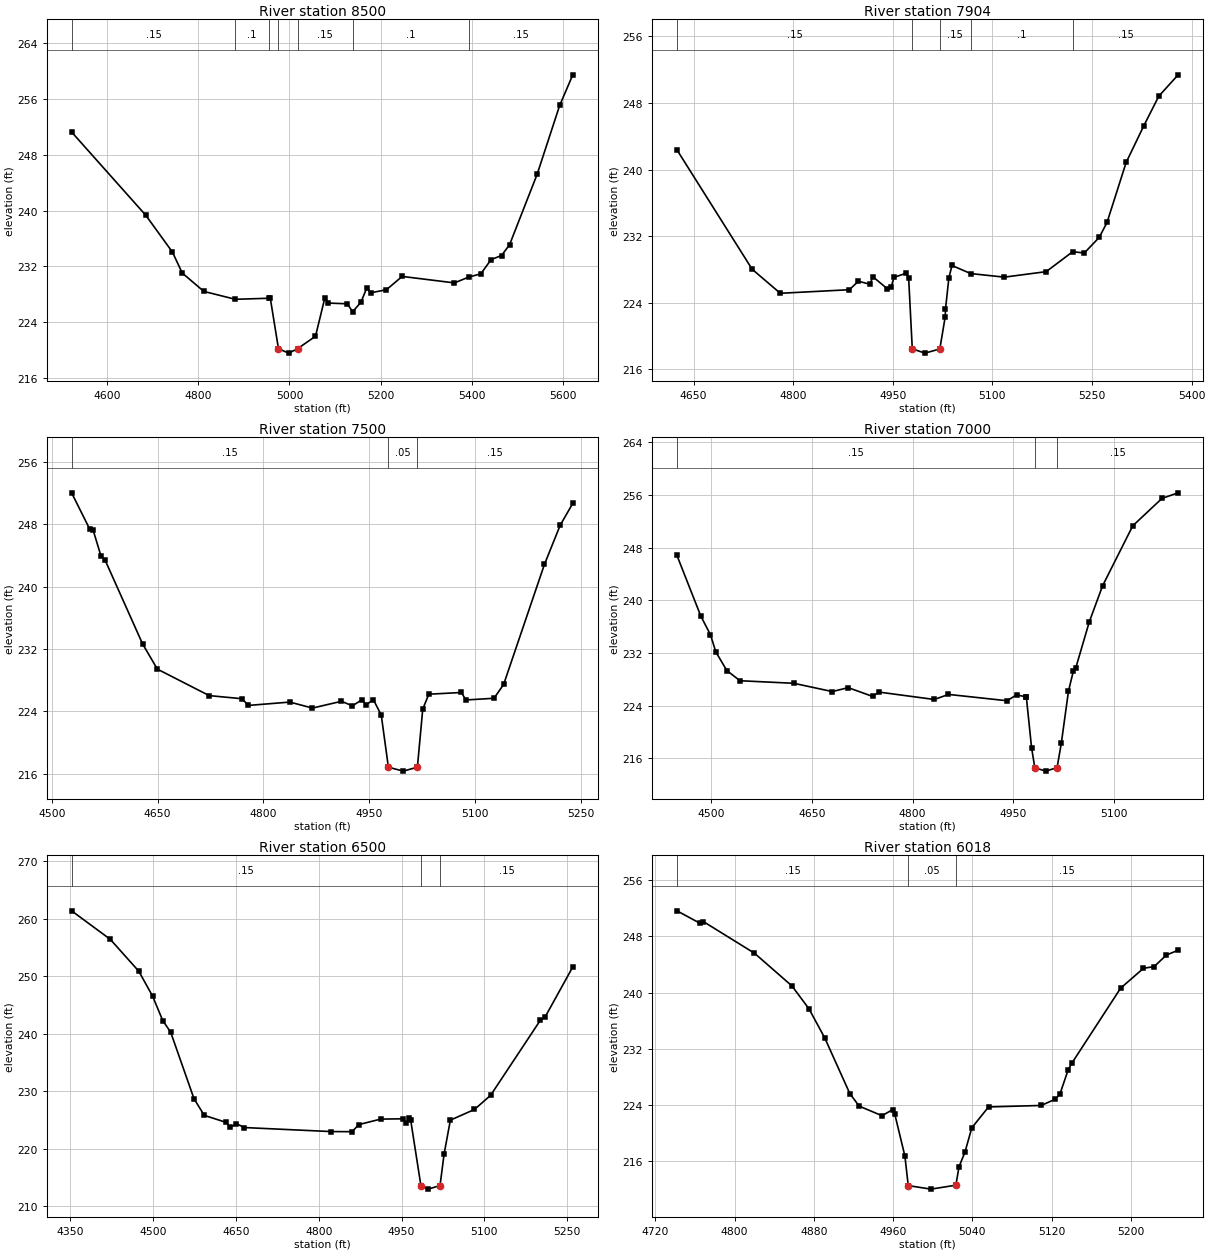
Type RM Length L Ch R = 1,8500,596,596,596
BEGIN DESCRIPTION:
WATEREE CREEK 17.0
END DESCRIPTION:
XS GIS Cut Line= 3
      1919525.00       860025.00      1919250.46       859633.21
      1919309.66       859014.04
#Sta/Elev= 30
  4521.6  251.27  4684.6  239.32  4743.0  234.05  4764.5  231.05  4812.0  228.41
  4881.1  227.28  4955.1  227.43  4957.7  227.50  4975.8  220.19  4998.3  219.56
  5017.6  220.19  5057.1  221.98  5077.8  227.53  5085.1  226.74  5127.2  226.63
  5138.6  225.48  5156.8  226.86  5169.9  228.94  5178.3  228.21  5212.8  228.65
  5247.4  230.56  5362.2  229.63  5393.2  230.46  5420.1  230.93  5442.6  232.97
  5465.6  233.56  5483.1  235.09  5543.8  245.22  5593.2  255.08  5622.0  259.47
#Mann=7,-1,0
  4521.6    0.15       0  4881.1     0.1       0  4955.1    0.15       0
  4975.8    0.05       0  5017.6    0.15       0  5138.6     0.1       0
  5393.2    0.15       0
Bank Sta=4975.8,5017.6
Exp/Cntr=0.3,0.1

Type RM Length L Ch R = 1,7904,404,404,404
BEGIN DESCRIPTION:
WATEREE CREEK 16.0
END DESCRIPTION:
XS GIS Cut Line= 3
      1919762.73       859852.79      1919736.31       859478.82
      1919794.41       859103.59
#Sta/Elev= 30
  4625.1  242.37  4738.3  228.03  4780.7  225.14  4884.7  225.57  4898.3  226.59
  4916.1  226.22  4919.8  227.15  4941.5  225.70  4947.6  225.89  4951.9  227.06
  4969.5  227.53  4973.9  227.03  4979.4  218.47  4998.3  217.95  5020.9  218.45
  5029.0  222.33  5029.4  223.22  5034.5  227.00  5039.2  228.48  5067.3  227.51
  5118.0  227.08  5181.0  227.74  5221.0  230.14  5238.4  229.98  5260.9  231.86
  5272.6  233.65  5301.4  240.86  5327.7  245.22  5350.6  248.83  5379.7  251.39
#Mann=5,-1,0
  4625.1    0.15       0  4979.4    0.05       0  5020.9    0.15       0
  5067.3     0.1       0  5221.0    0.15       0
Bank Sta=4979.4,5020.9
Exp/Cntr=0.3,0.1

Type RM Length L Ch R = 1,7500,500,500,500
BEGIN DESCRIPTION:
WATEREE CREEK 15.0
END DESCRIPTION:
XS GIS Cut Line= 3
      1919924.98       859925.03      1920139.41       859504.78
      1920087.96       859272.00
#Sta/Elev= 30
  4528.2  252.03  4553.8  247.39  4558.7  247.25  4569.8  243.93  4575.5  243.43
  4628.7  232.66  4649.7  229.41  4723.2  226.01  4769.7  225.61  4778.7  224.75
  4837.5  225.18  4869.4  224.41  4910.6  225.28  4926.1  224.70  4939.5  225.47
  4945.7  224.86  4955.9  225.48  4967.0  223.51  4977.1  216.82  4998.3  216.32
  5018.2  216.83  5025.8  224.28  5034.4  226.19  5080.6  226.41  5086.9  225.45
  5126.8  225.67  5140.4  227.44  5198.2  242.84  5220.6  247.88  5238.4  250.68
#Mann=3,-1,0
  4528.2    0.15       0  4977.1    0.05       0  5018.2    0.15       0
Bank Sta=4977.1,5018.2
Exp/Cntr=0.3,0.1

Type RM Length L Ch R = 1,7000,500,500,500
BEGIN DESCRIPTION:
WATEREE CREEK 14.0
END DESCRIPTION:
XS GIS Cut Line= 3
      1920400.18       860014.09      1920629.23       859512.73
      1920621.91       859317.26
#Sta/Elev= 30
  4448.8  246.81  4484.4  237.58  4498.7  234.76  4506.7  232.15  4523.1  229.32
  4542.7  227.77  4622.9  227.38  4680.3  226.12  4703.9  226.72  4740.2  225.39
  4750.1  226.04  4832.3  224.92  4853.4  225.69  4940.4  224.73  4955.1  225.62
  4968.6  225.32  4969.4  225.29  4977.2  217.58  4982.0  214.55  4998.3  214.03
  5015.2  214.56  5021.5  218.27  5032.2  226.20  5039.4  229.22  5043.0  229.70
  5063.1  236.69  5083.0  242.20  5128.0  251.32  5171.6  255.49  5195.6  256.33
#Mann=3,-1,0
  4448.8    0.15       0  4982.0    0.05       0  5015.2    0.15       0
Bank Sta=4982,5015.2
Exp/Cntr=0.3,0.1

Type RM Length L Ch R = 1,6500,482,482,482
BEGIN DESCRIPTION:
WATEREE CREEK 13.0
END DESCRIPTION:
XS GIS Cut Line= 3
      1921175.00       860225.02      1921123.13       859579.40
      1921160.38       859321.78
#Sta/Elev= 30
  4352.3  261.42  4422.4  256.46  4474.0  250.92  4499.0  246.59  4517.4  242.34
  4531.8  240.31  4574.0  228.76  4592.6  225.85  4632.5  224.62  4639.8  223.74
  4650.9  224.41  4665.1  223.73  4822.3  223.03  4860.3  223.01  4872.9  224.25
  4912.3  225.20  4952.0  225.25  4958.1  224.50  4964.3  225.33  4966.7  224.98
  4985.3  213.52  4998.3  213.02  5019.8  213.64  5027.1  219.09  5038.5  225.02
  5082.1  226.87  5111.4  229.33  5201.4  242.37  5210.2  242.96  5260.3  251.66
#Mann=3,-1,0
  4352.3    0.15       0  4985.3    0.05       0  5019.8    0.15       0
Bank Sta=4985.3,5019.8
Exp/Cntr=0.3,0.1

Type RM Length L Ch R = 1,6018,162,162,162
BEGIN DESCRIPTION:
WATEREE CREEK 12.0
END DESCRIPTION:
XS GIS Cut Line= 3
      1921459.04       860172.49      1921418.31       859914.54
      1921436.41       859670.15
#Sta/Elev= 30
  4741.7  251.62  4764.6  249.88  4768.5  250.08  4820.0  245.59  4857.9  240.93
  4875.1  237.67  4891.0  233.53  4916.3  225.63  4925.7  223.85  4948.8  222.48
  4959.4  223.34  4961.7  222.70  4971.9  216.75  4975.3  212.54  4998.3  212.04
  5023.4  212.60  5026.6  215.23  5032.5  217.27  5039.5  220.76  5056.4  223.73
  5109.6  223.94  5123.9  224.84  5128.4  225.53  5136.9  229.03  5140.8  230.01
  5189.8  240.62  5212.9  243.45  5223.7  243.69  5235.9  245.32  5247.9  246.02
#Mann=3,-1,0
  4741.7    0.15       0  4975.3    0.05       0  5023.4    0.15       0
Bank Sta=4975.3,5023.4
Exp/Cntr=0.5,0.3

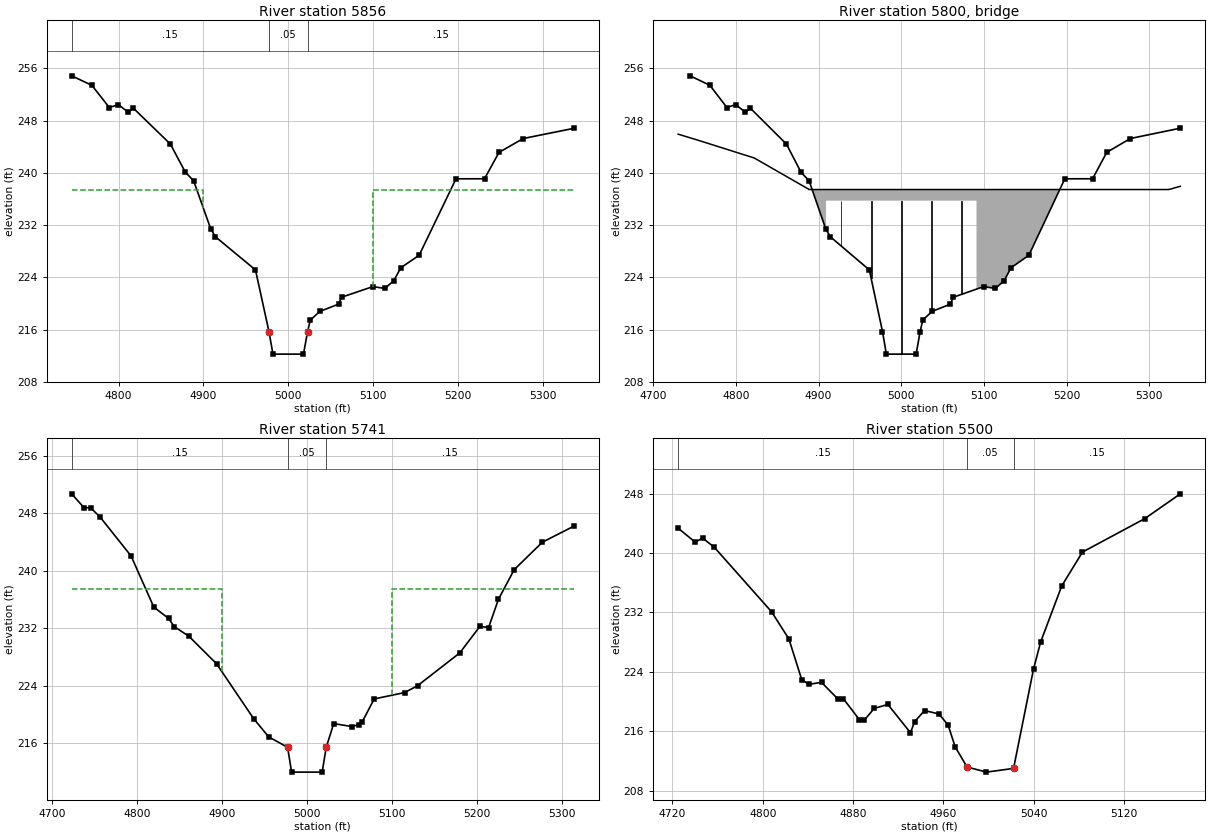
Type RM Length L Ch R = 1,5856,115,115,115
BEGIN DESCRIPTION:
WC_Wash Lever Rd - US
END DESCRIPTION:
XS GIS Cut Line= 4
      1921652.61       860150.98      1921598.57       859981.40
      1921535.20       859770.79      1921481.14       859584.39
#Sta/Elev= 30
  4744.7  254.86  4768.5  253.41  4789.1  250.01  4799.7  250.45  4811.4  249.29
  4817.4  249.91  4861.1  244.41  4878.7  240.11  4888.5  238.79  4908.6  231.44
  4914.1  230.23  4961.4  225.14  4977.3  215.70  4982.0  212.25  5018.0  212.25
  5022.8  215.70  5026.0  217.45  5037.1  218.78  5059.3  219.90  5062.9  220.96
  5099.8  222.59  5113.9  222.31  5124.4  223.49  5132.8  225.48  5154.3  227.38
  5197.8  239.09  5231.4  239.10  5248.5  243.14  5277.0  245.26  5336.7  246.82
#Mann=3,-1,0
  4744.7    0.15       0  4977.3    0.05       0  5022.8    0.15       0
#XS Ineff=2,0
    0.00 4900.00  237.45 5100.00    0.00  237.45
Permanent Ineff=
       F       F
Bank Sta=4977.3,5022.8
Exp/Cntr=0.5,0.3

Type RM Length L Ch R =3,5800,,,
BEGIN DESCRIPTION:
WC_Wash Lever Rd - TOR
Structure ID: lds 23
Approximate Survey Structure
END DESCRIPTION:
Bridge Culvert--1,0,-1,-1,0
Deck Dist Width WeirC Skew NumUp NumDn MinLoCord MaxHiCord MaxSubmerge Is_Ogee
38,36,3,,15,15,,,0.95,0,1,1,,
  4730.1  4755.5  4822.2  4888.7  4909.0  4909.0  5091.0  5091.0  5323.3  5324.0
  5326.5  5329.8  5333.1  5334.2  5337.5
  245.93  244.95  242.28  237.45  237.45  237.45  237.45  237.45  237.45  237.48
  237.54  237.68  237.79  237.83  237.95
  192.25  192.25  192.25  192.25  192.25  235.75  235.75  192.25  192.25  192.25
  192.25  192.25  192.25  192.25  192.25
  4730.1  4755.5  4822.2  4888.7  4909.0  4909.0  5091.0  5091.0  5323.3  5324.0
  5326.5  5329.8  5333.1  5334.2  5337.5
  245.93  244.95  242.28  237.45  237.45  237.45  237.45  237.45  237.45  237.48
  237.54  237.68  237.79  237.83  237.95
  192.25  192.25  192.25  192.25  192.25  235.75  235.75  192.25  192.25  192.25
  192.25  192.25  192.25  192.25  192.25
Pier Skew, UpSta & Num, DnSta & Num=,4927.2,2,4927.2,2,0,0,0,0,0
       1       1
  228.53  235.75
       1       1
  221.51  235.75
Pier Skew, UpSta & Num, DnSta & Num=,4963.6,2,4963.6,2,0,0,0,0,0
       1       1
  224.25  235.75
       1       1
  214.94  235.75
Pier Skew, UpSta & Num, DnSta & Num=,5000,2,5000,2,0,0,0,0,0
       1       1
  212.25  235.75
       1       1
  212.00  235.75
Pier Skew, UpSta & Num, DnSta & Num=,5036.4,2,5036.4,2,0,0,0,0,0
       1       1
  218.72  235.75
       1       1
  218.74  235.75
Pier Skew, UpSta & Num, DnSta & Num=,5072.8,2,5072.8,2,0,0,0,0,0
       1       1
  221.28  235.75
       1       1
  220.71  235.75
Abutment Skew #Up #Dn=,2,2
  4909.0  4950.0
  235.75  226.23
  4909.0  4950.0
  235.75  217.67
Abutment Skew #Up #Dn=,2,2
  5050.0  5091.0
  219.69  235.75
  5050.0  5091.0
  218.64  235.75
BR Coef=1,1,0,1.25,0,,,0.8,0,2,0,
WSPro=,,,, 1 ,,,, 0 ,,,, 0 ,,,,-1 ,-1 ,-1 , 0 , 0 , 0 , 0 , 0
BC Design=,,0,,0,,,,,,

Type RM Length L Ch R = 1,5741,241,241,241
BEGIN DESCRIPTION:
WC_Wash Lever Rd - DS
END DESCRIPTION:
XS GIS Cut Line= 5
      1921744.38       860106.43      1921717.85       859990.72
      1921654.48       859798.75      1921604.16       859634.74
      1921561.31       859545.31
#Sta/Elev= 30
  4722.9  250.71  4737.6  248.76  4745.2  248.78  4756.4  247.48  4792.9  242.07
  4819.7  234.95  4837.0  233.39  4843.7  232.25  4861.1  230.89  4893.6  227.07
  4937.3  219.44  4954.9  216.92  4977.3  215.45  4982.0  212.00  5018.0  212.00
  5022.8  215.45  5031.6  218.75  5053.6  218.33  5060.9  218.62  5065.4  219.04
  5079.3  222.18  5115.3  223.07  5130.5  224.03  5180.1  228.58  5203.9  232.28
  5214.1  232.11  5225.7  236.05  5244.3  240.17  5277.4  243.98  5314.5  246.21
#Mann=3,-1,0
  4722.9    0.15       0  4977.3    0.05       0  5022.8    0.15       0
#XS Ineff=2,0
    0.00 4900.00  237.45 5100.00    0.00  237.45
Permanent Ineff=
       F       F
Bank Sta=4977.3,5022.8
Exp/Cntr=0.5,0.3

Type RM Length L Ch R = 1,5500,500,500,500
BEGIN DESCRIPTION:
WATEREE CREEK 11.0
END DESCRIPTION:
XS GIS Cut Line= 3
      1921893.44       860027.65      1921891.81       859752.65
      1921892.58       859582.55
#Sta/Elev= 30
  4725.0  243.34  4740.1  241.46  4746.7  242.00  4757.0  240.78  4807.9  232.07
  4823.2  228.42  4834.6  222.93  4840.9  222.32  4852.1  222.58  4866.9  220.30
  4871.4  220.39  4885.7  217.56  4890.1  217.51  4898.8  219.08  4910.9  219.61
  4930.9  215.81  4934.6  217.28  4943.4  218.79  4956.2  218.33  4964.3  216.83
  4970.6  213.88  4981.1  211.19  4998.3  210.50  5022.3  211.00  5040.0  224.37
  5046.3  228.01  5065.0  235.56  5083.4  240.12  5138.6  244.62  5170.1  247.96
#Mann=3,-1,0
  4725.0    0.15       0  4981.1    0.05       0  5022.3    0.15       0
Bank Sta=4981.1,5022.3
Exp/Cntr=0.3,0.1