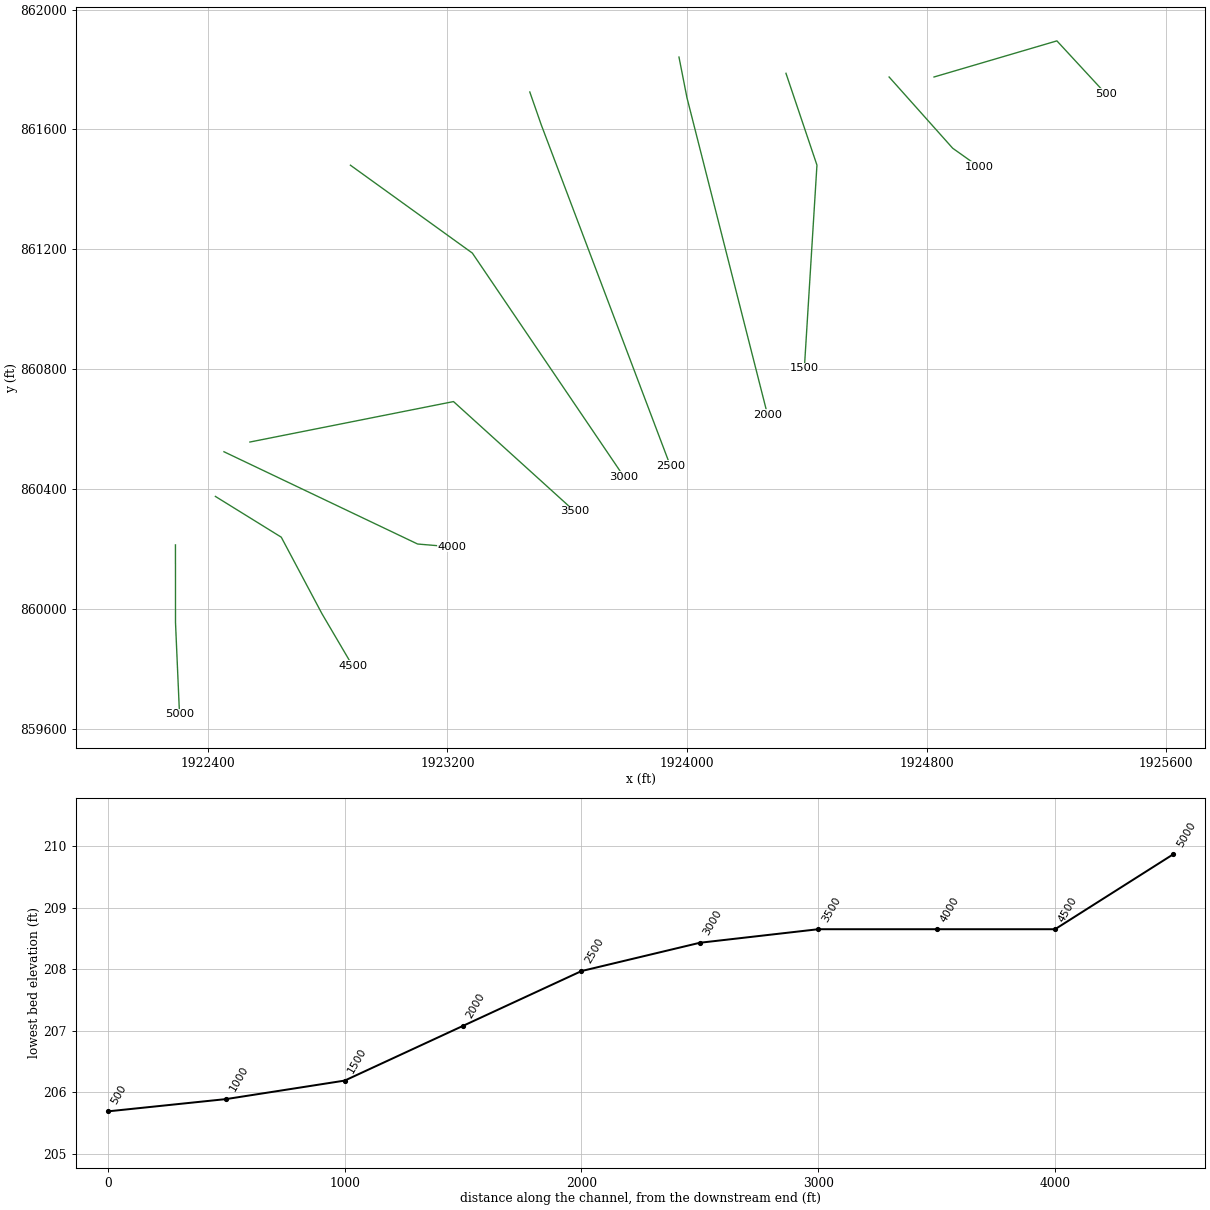
HEC-RAS study WATEREE CREEK.prj: WATEREE CREEK Limited Detail Study

--- WATEREE CREEK.g01 (geometry) --- (continued)

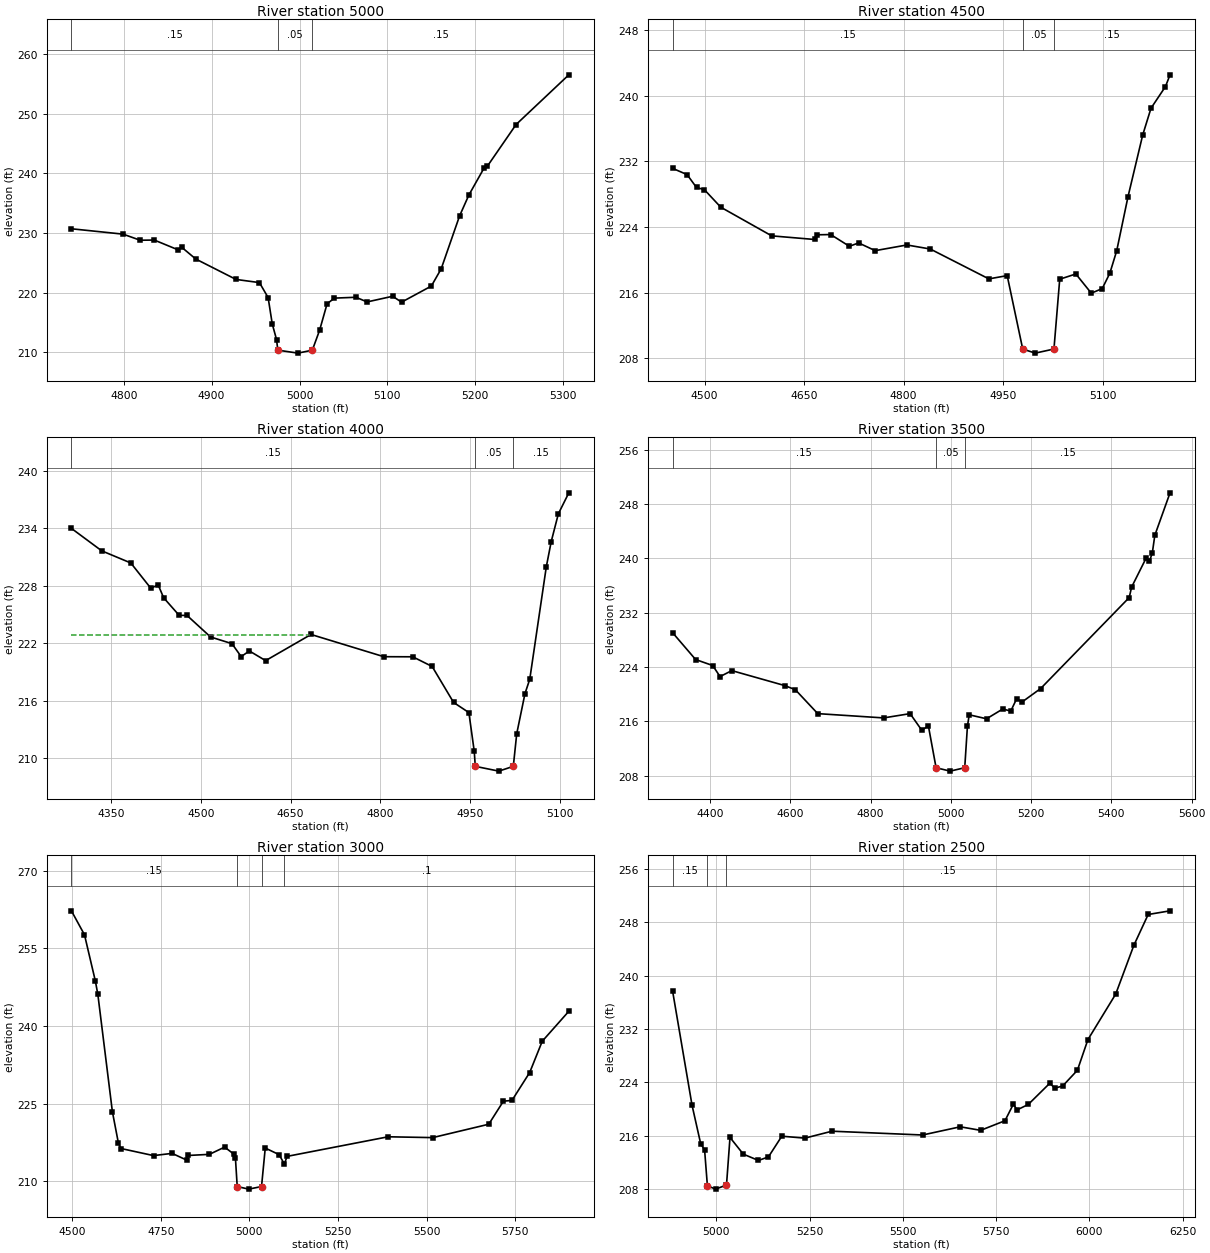
Type RM Length L Ch R = 1,5000,500,500,500
BEGIN DESCRIPTION:
WATEREE CREEK 10.0
END DESCRIPTION:
XS GIS Cut Line= 3
      1922291.64       860213.20      1922291.80       859953.70
      1922305.21       859647.60
#Sta/Elev= 30
  4740.5  230.71  4799.3  229.81  4818.7  228.79  4834.8  228.82  4861.7  227.19
  4865.9  227.62  4882.0  225.64  4927.8  222.22  4954.4  221.69  4964.3  219.18
  4969.0  214.76  4973.9  212.13  4975.3  210.37  4998.3  209.87  5014.6  210.37
  5022.9  213.72  5031.4  218.15  5039.8  219.09  5064.2  219.23  5076.9  218.45
  5106.0  219.40  5116.1  218.41  5150.0  221.11  5161.2  224.00  5182.1  232.86
  5192.7  236.37  5209.7  240.82  5213.6  241.17  5246.4  248.18  5306.4  256.51
#Mann=3,-1,0
  4740.5    0.15       0  4975.3    0.05       0  5014.6    0.15       0
Bank Sta=4975.3,5014.6
Exp/Cntr=0.3,0.1

Type RM Length L Ch R = 1,4500,500,500,500
BEGIN DESCRIPTION:
WATEREE CREEK 9.0
END DESCRIPTION:
XS GIS Cut Line= 4
      1922425.00       860375.00      1922645.00       860238.92
      1922781.02       859983.24      1922883.20       859809.45
#Sta/Elev= 30
  4451.7  231.15  4473.5  230.39  4487.7  228.82  4499.5  228.56  4524.3  226.42
  4601.1  222.93  4665.6  222.49  4669.8  223.06  4690.0  223.09  4718.2  221.66
  4732.1  222.07  4757.1  221.13  4804.9  221.82  4840.1  221.33  4928.5  217.69
  4956.1  218.09  4979.5  209.15  4998.3  208.65  5026.6  209.15  5035.3  217.65
  5059.6  218.29  5082.9  215.95  5099.4  216.51  5110.9  218.39  5121.2  221.11
  5138.3  227.72  5160.4  235.21  5172.9  238.47  5194.7  241.11  5201.6  242.54
#Mann=3,-1,0
  4451.7    0.15       0  4979.5    0.05       0  5026.6    0.15       0
Bank Sta=4979.5,5026.6
Exp/Cntr=0.3,0.1

Type RM Length L Ch R = 1,4000,500,500,500
BEGIN DESCRIPTION:
WATEREE CREEK 8.0
END DESCRIPTION:
XS GIS Cut Line= 3
      1922453.69       860524.07      1923100.40       860216.08
      1923215.30       860206.44
#Sta/Elev= 30
  4283.7  233.98  4334.3  231.64  4383.0  230.37  4416.5  227.73  4428.7  228.09
  4437.9  226.74  4463.9  224.90  4476.9  224.90  4516.3  222.65  4552.1  221.95
  4567.5  220.60  4581.2  221.19  4608.4  220.18  4684.3  222.91  4806.1  220.59
  4854.4  220.58  4886.8  219.57  4922.6  215.82  4948.2  214.76  4957.2  210.71
  4958.9  209.15  4998.3  208.65  5022.5  209.15  5028.2  212.55  5042.0  216.74
  5050.0  218.24  5077.7  229.99  5085.9  232.61  5097.8  235.50  5115.3  237.69
#Mann=3,-1,0
  4283.7    0.15       0  4958.9    0.05       0  5022.5    0.15       0
#XS Ineff=2,0
    0.00 4683.20  222.90               0
Permanent Ineff=
       F       F
Bank Sta=4958.9,5022.5
Exp/Cntr=0.3,0.1

Type RM Length L Ch R = 1,3500,500,500,500
BEGIN DESCRIPTION:
WATEREE CREEK 7.0
END DESCRIPTION:
XS GIS Cut Line= 3
      1922540.30       860556.53      1923220.22       860691.56
      1923625.01       860324.99
#Sta/Elev= 30
  4306.8  229.04  4364.1  225.09  4406.6  224.21  4425.0  222.58  4454.2  223.46
  4586.4  221.25  4612.6  220.64  4668.4  217.12  4832.5  216.49  4898.5  217.12
  4927.7  214.66  4944.0  215.33  4963.2  209.15  4998.3  208.65  5034.6  209.15
  5041.3  215.26  5045.8  216.95  5088.9  216.36  5129.3  217.80  5149.3  217.50
  5164.2  219.34  5177.1  218.82  5223.8  220.82  5444.4  234.22  5450.3  235.75
  5487.1  240.10  5494.8  239.56  5502.0  240.81  5508.2  243.39  5546.1  249.65
#Mann=3,-1,0
  4306.8    0.15       0  4963.2    0.05       0  5034.6    0.15       0
Bank Sta=4963.2,5034.6
Exp/Cntr=0.3,0.1

Type RM Length L Ch R = 1,3000,500,500,500
BEGIN DESCRIPTION:
WATEREE CREEK 6.0
END DESCRIPTION:
XS GIS Cut Line= 3
      1922875.96       861480.55      1923283.20       861187.19
      1923789.15       860441.06
#Sta/Elev= 30
  4498.1  262.29  4535.0  257.65  4565.7  248.69  4572.7  246.10  4613.7  223.42
  4630.7  217.33  4638.0  216.29  4729.8  214.92  4782.2  215.35  4823.0  214.06
  4826.6  214.94  4887.3  215.16  4930.4  216.56  4957.5  215.15  4960.9  214.40
  4965.9  208.93  4998.3  208.43  5034.5  208.93  5045.0  216.38  5084.0  215.11
  5098.9  213.29  5106.6  214.77  5391.7  218.56  5517.4  218.40  5675.6  220.99
  5716.9  225.45  5741.1  225.60  5791.1  231.00  5826.5  237.05  5901.5  242.85
#Mann=4,-1,0
  4498.1    0.15       0  4965.9    0.05       0  5034.5    0.15       0
  5098.9     0.1       0
Bank Sta=4965.9,5034.5
Exp/Cntr=0.3,0.1

Type RM Length L Ch R = 1,2500,500,500,500
BEGIN DESCRIPTION:
WATEREE CREEK 5.0
END DESCRIPTION:
XS GIS Cut Line= 3
      1923475.01       861724.96      1923513.59       861614.51
      1923944.35       860477.14
#Sta/Elev= 30
  4883.0  237.66  4935.1  220.54  4958.3  214.76  4968.7  213.87  4976.2  208.47
  4998.3  207.97  5027.4  208.59  5036.8  215.72  5072.4  213.22  5113.1  212.27
  5139.9  212.81  5175.6  215.91  5237.5  215.62  5310.1  216.66  5553.0  216.09
  5653.9  217.32  5708.6  216.79  5773.8  218.23  5796.4  220.73  5806.0  219.85
  5836.2  220.67  5894.4  223.88  5906.6  223.11  5928.4  223.44  5967.9  225.80
  5996.1  230.40  6070.6  237.23  6119.2  244.54  6157.6  249.17  6216.2  249.72
#Mann=3,-1,0
  4883.0    0.15       0  4976.2    0.05       0  5027.4    0.15       0
Bank Sta=4976.2,5027.4
Exp/Cntr=0.3,0.1

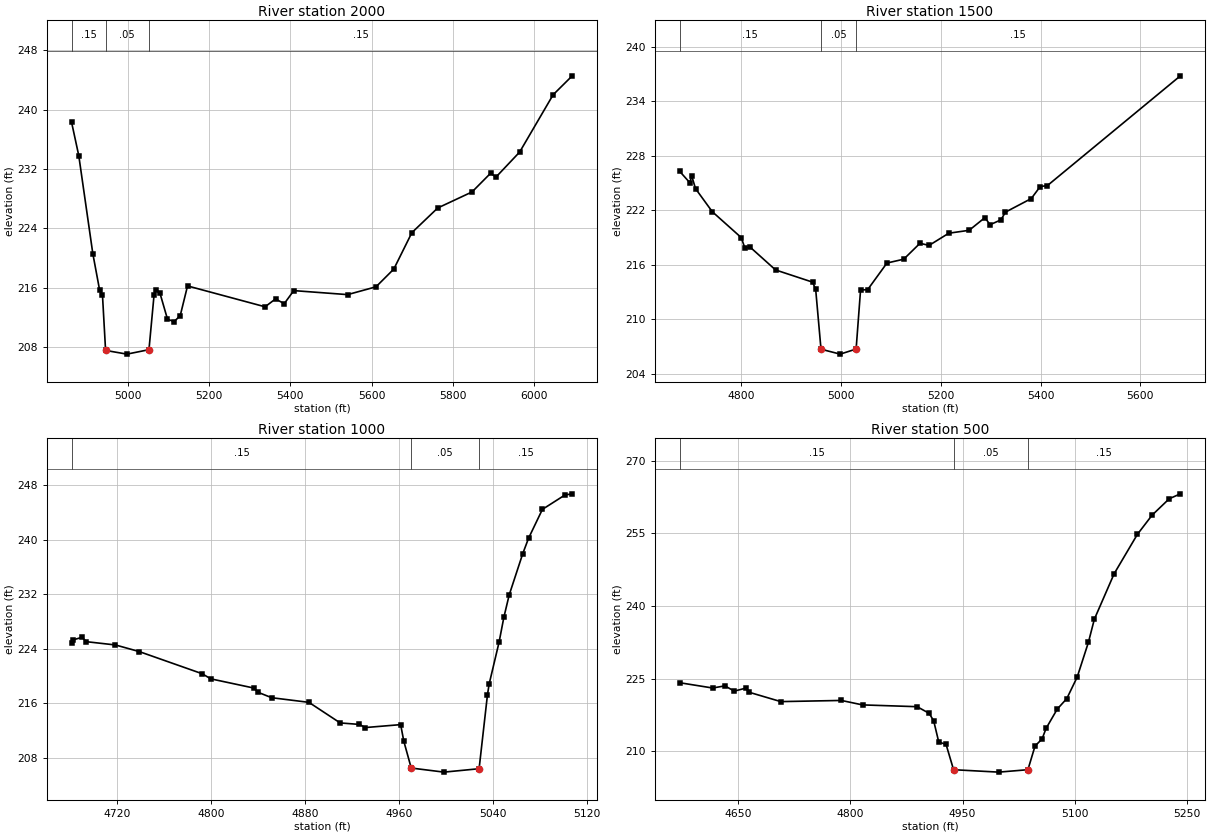
Type RM Length L Ch R = 1,2000,500,500,500
BEGIN DESCRIPTION:
WATEREE CREEK 4.0
END DESCRIPTION:
XS GIS Cut Line= 3
      1923973.23       861841.45      1923999.81       861706.24
      1924269.20       860646.75
#Sta/Elev= 30
  4862.2  238.29  4879.9  233.80  4914.4  220.62  4930.9  215.77  4938.2  215.01
  4945.8  207.58  4998.3  207.08  5052.5  207.68  5065.0  215.04  5070.7  215.76
  5079.6  215.27  5098.0  211.79  5114.1  211.45  5129.3  212.25  5147.3  216.26
  5338.0  213.45  5363.6  214.51  5385.1  213.87  5408.5  215.63  5540.9  215.09
  5610.7  216.14  5654.5  218.53  5698.9  223.43  5762.4  226.75  5846.8  228.91
  5892.5  231.43  5905.7  230.91  5963.9  234.28  6046.2  241.99  6093.2  244.54
#Mann=3,-1,0
  4862.2    0.15       0  4945.8    0.05       0  5052.5    0.15       0
Bank Sta=4945.8,5052.5
Exp/Cntr=0.3,0.1

Type RM Length L Ch R = 1,1500,500,500,500
BEGIN DESCRIPTION:
WATEREE CREEK 3.0
END DESCRIPTION:
XS GIS Cut Line= 3
      1924330.55       861787.30      1924434.01       861480.89
      1924391.91       860802.00
#Sta/Elev= 30
  4676.6  226.29  4696.6  225.06  4700.8  225.76  4708.3  224.39  4741.8  221.86
  4799.9  219.01  4807.5  217.81  4816.7  218.01  4868.7  215.45  4942.8  214.11
  4949.1  213.33  4959.8  206.73  4998.3  206.19  5030.2  206.75  5039.1  213.24
  5053.3  213.28  5092.0  216.21  5125.6  216.63  5158.2  218.38  5176.5  218.15
  5216.0  219.49  5256.8  219.81  5288.5  221.21  5298.6  220.42  5320.5  220.96
  5329.6  221.81  5381.3  223.30  5399.2  224.62  5413.7  224.73  5680.2  236.80
#Mann=3,-1,0
  4676.6    0.15       0  4959.8    0.05       0  5030.2    0.15       0
Bank Sta=4959.8,5030.2
Exp/Cntr=0.3,0.1

Type RM Length L Ch R = 1,1000,500,500,500
BEGIN DESCRIPTION:
WATEREE CREEK 2.0
END DESCRIPTION:
XS GIS Cut Line= 3
      1924675.02       861774.98      1924887.36       861537.19
      1924975.03       861474.98
#Sta/Elev= 30
  4681.2  224.82  4682.6  225.30  4690.0  225.67  4693.9  225.03  4718.6  224.55
  4738.8  223.58  4792.4  220.33  4799.7  219.58  4836.6  218.22  4839.9  217.61
  4851.6  216.81  4883.3  216.13  4909.9  213.11  4926.3  212.89  4931.3  212.43
  4961.4  212.86  4964.1  210.42  4970.4  206.49  4998.3  205.89  5028.2  206.39
  5035.3  217.22  5036.7  218.78  5045.2  224.96  5049.3  228.63  5053.8  231.88
  5065.3  237.92  5070.3  240.21  5082.1  244.45  5101.3  246.56  5107.5  246.73
#Mann=3,-1,0
  4681.2    0.15       0  4970.4    0.05       0  5028.2    0.15       0
Bank Sta=4970.4,5028.2
Exp/Cntr=0.3,0.1

Type RM Length L Ch R = 1,500,0,0,0
BEGIN DESCRIPTION:
WATEREE CREEK 1.0
END DESCRIPTION:
XS GIS Cut Line= 3
      1924825.01       861775.00      1925235.36       861895.56
      1925398.93       861718.71
#Sta/Elev= 30
  4572.3  224.16  4616.3  223.07  4632.6  223.51  4645.2  222.43  4660.7  223.05
  4665.0  222.19  4707.3  220.26  4788.2  220.50  4816.4  219.58  4889.3  219.21
  4905.3  217.85  4911.4  216.32  4918.2  211.92  4928.0  211.41  4938.0  206.19
  4998.3  205.69  5037.3  206.19  5046.8  211.08  5056.2  212.55  5061.6  214.74
  5076.5  218.72  5089.2  220.88  5103.1  225.33  5118.1  232.52  5126.0  237.28
  5152.4  246.67  5183.5  254.82  5203.1  258.78  5226.0  262.17  5240.9  263.19
#Mann=3,-1,0
  4572.3    0.15       0  4938.0    0.05       0  5037.3    0.15       0
Bank Sta=4938,5037.3
Exp/Cntr=0.3,0.1

Chan Stop Cuts=-1

--- WATEREE CREEK.g02 (geometry) ---

Geom Title=Effective
Program Version=4.10

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
River Reach=WATEREE CREEK   ,Reach-1

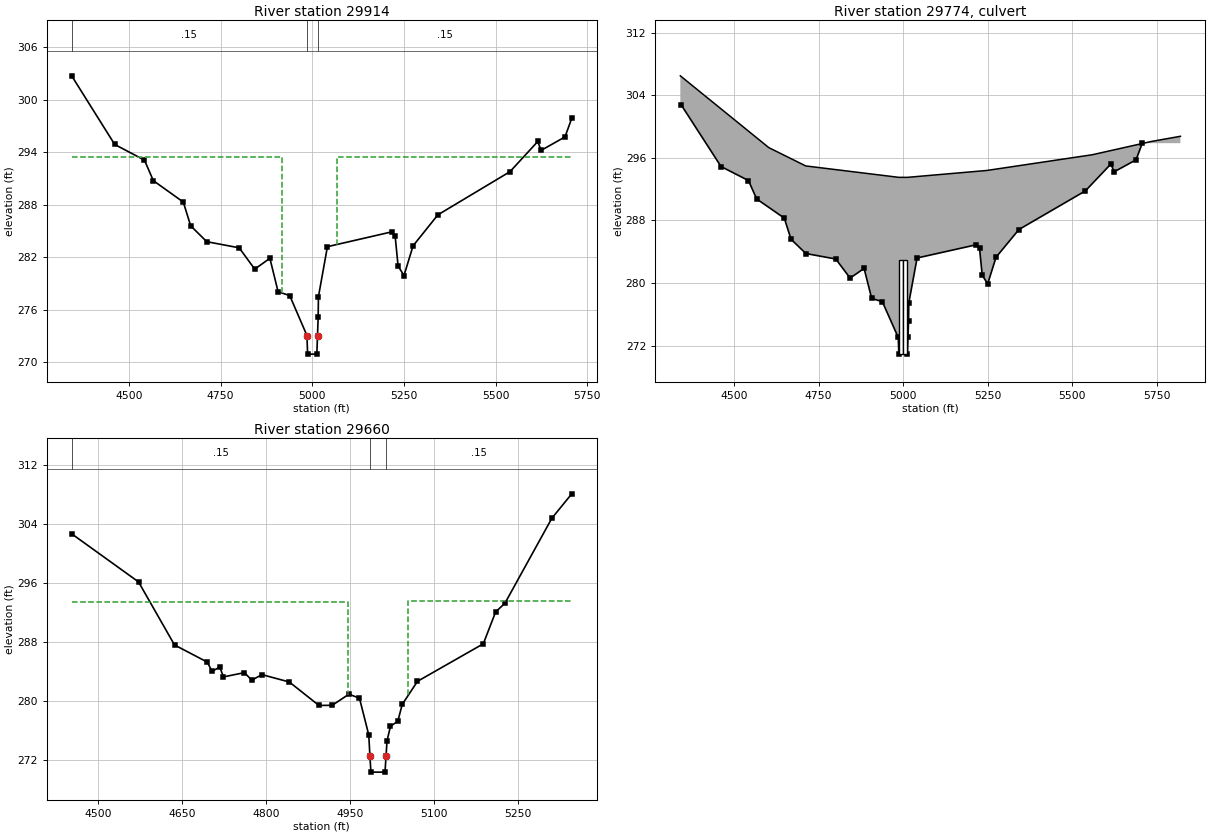
Type RM Length L Ch R = 1 ,29914   ,254,254,254
BEGIN DESCRIPTION:
WC_I-26 - US
END DESCRIPTION:
XS GIS Cut Line= 5
      1908925.36        850225.2      1909142.71       850133.21
      1909515.74        849940.9      1909710.07       849870.21
      1910127.52       849593.91
#Sta/Elev= 30
  4344.3  302.74  4461.6  294.89  4542.7   293.1  4566.9  290.75  4648.6   288.3
  4668.6  285.59  4712.5  283.77  4800.9  283.07  4843.3  280.63  4884.6  281.87
    4907  278.04  4938.6  277.61  4985.6  273.04  4987.4  270.91  5012.6  270.91
  5014.4  273.04  5016.2  275.16  5016.9  277.47  5041.4   283.2  5216.4  284.89
    5226  284.43    5234     281  5250.1  279.89  5274.9   283.3  5342.5  286.84
  5539.1  291.78  5614.8  295.23  5623.8  294.21  5688.9  295.75  5707.4  297.88
#Mann= 3 ,-1 , 0
  4344.3     .15       0  4985.6     .05       0  5014.4     .15       0
#XS Ineff= 2 , 0
       0    4917  293.41  5066.4       0  293.44
Permanent Ineff=
       F       F
Bank Sta=4985.6,5014.4
XS Rating Curve= 0 ,0
Exp/Cntr=0.5,0.3

Type RM Length L Ch R = 2 ,29774   ,,,
BEGIN DESCRIPTION:
WC_I-26 - TOR
Structure ID: lds 17
Approximate Survey Structure
END DESCRIPTION:
Bridge Culvert--1,0,-1,-1, 0
Deck Dist Width WeirC Skew NumUp NumDn MinLoCord MaxHiCord MaxSubmerge Is_Ogee
80,120,3,0, 9, 9, , , 0.95, 0, 1,1,,
  4341.2  4602.9    4712  4987.5  5012.5  5247.6  5559.4  5734.5  5820.1
  306.49  297.31  294.97  293.51  293.51  294.39   296.4   298.1  298.76
  250.91  250.91  250.91  250.91  250.91  250.91  250.91  250.91  250.91
  4341.2  4602.9    4712  4987.5  5012.5  5247.6  5559.4  5734.5  5820.1
  306.49  297.31  294.97  293.51  293.51  294.39   296.4   298.1  298.76
  250.31  250.31  250.31  250.31  250.31  250.31  250.31  250.31  250.31
BR Coef= 1 , 1 , 0 ,1.25, 0 ,,,0.8,0,2,0,
WSPro=,,,, 1 ,,,, 0 ,,,, 0 ,,,,-1 ,-1 ,-1 , 0 , 0 , 0 , 0 , 0
Culvert=2,12,12,120,0.012,0.4,1,8,1,270.91,4993.5,270.31,4993.5,Culvert #1  , 0 ,80
Culvert Bottom n=0.012
Culvert=2,12,12,120,0.012,0.4,1,8,1,270.91,5006.5,270.31,5006.5,Culvert #2  , 0 ,80
Culvert Bottom n=0.012
BC Design=,, 0 ,, 0 ,,,,,,
BC HTab HWMax=302.74
BC Use User HTab Curves=0
BC User HTab FreeFlow(D)= 0

Type RM Length L Ch R = 1 ,29660   ,302,302,302
BEGIN DESCRIPTION:
WC_I-26 - DS
END DESCRIPTION:
XS GIS Cut Line= 5
      1909019.78       850338.11      1909201.35       850317.25
       1909534.8       850168.22      1909733.33       850067.92
      1909857.36       850060.17
#Sta/Elev= 30
    4452  302.62  4571.6   296.1    4636  287.55  4694.8  285.22    4703  283.97
    4717  284.55  4723.6  283.22  4761.2   283.8  4774.2  282.77  4792.3  283.53
  4841.4  282.53  4894.4  279.35  4918.1  279.37    4948  280.87  4966.9  280.34
  4983.6  275.33  4985.6  272.44  4987.4  270.31  5012.6  270.31  5014.4  272.44
  5016.2  274.56  5022.4  276.53  5035.5  277.21  5043.4  279.49  5070.7  282.62
  5188.5  287.71  5210.5  292.03  5227.1   293.2  5311.2  304.74  5346.7  308.04
#Mann= 3 ,-1 , 0
    4452     .15       0  4985.6     .05       0  5014.4     .15       0
#XS Ineff= 2 , 0
       0    4947  293.37    5054       0  293.57
Permanent Ineff=
       F       F
Bank Sta=4985.6,5014.4
XS Rating Curve= 0 ,0
Exp/Cntr=0.5,0.3

--- WATEREE CREEK.g03 (geometry) ---

Geom Title=Corrected Effective
Program Version=4.10

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
River Reach=WATEREE CREEK   ,Reach-1