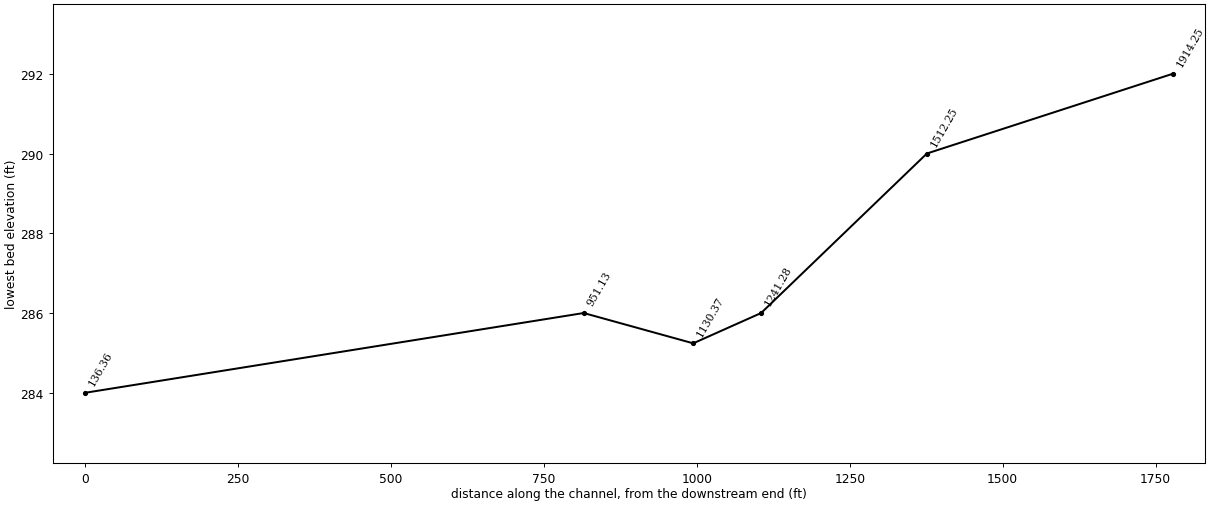
--- 1071.prj (project) ---

Proj Title=1071
Current Plan=p01
Default Exp/Contr=0.3,0.1
English Units
Geom File=g01
Flow File=f02
Plan File=p01
Y Axis Title=Elevation
X Axis Title(PF)=Main Channel Distance
X Axis Title(XS)=Station
BEGIN DESCRIPTION:
END DESCRIPTION:
DSS Export Rating Curves= 0
DSS Export Rating Curve Sorted= 0
DSS Export Volume Flow Curves= 0
DXF OffsetX= 0
DXF OffsetY= 0
DXF ScaleX= 1
DXF ScaleY= 10

--- 1071.p01 (plan) ---

Plan Title=Existing
Program Version=4.10
Short Identifier=Existing
Geom File=g01
Flow File=f02
Subcritical Flow
K Sum by GR= 0
Std Step Tol= 0.01
Critical Tol= 0.01
Num of Std Step Trials= 20
Max Error Tol= 0.3
Flow Tol Ratio= 0.001
Split Flow NTrial= 30
Split Flow Tol= 0.02
Split Flow Ratio= 0.02
Log Output Level= 0
Friction Slope Method= 1
Unsteady Friction Slope Method= 2
Unsteady Bridges Friction Slope Method= 1
Parabolic Critical Depth
Global Vel Dist= 0 , 0 , 0
Global Log Level= 0
CheckData=True
Encroach Param=-1 ,0,0, 0
Computation Interval=1HOUR
Output Interval=1HOUR
Run HTab= 0
Run UNet= 0
Run PostProcess= 0
Run WQNet= 0
UNET Theta= 1
UNET Theta Warmup= 1
UNET ZTol= 0.02
UNET ZSATol= 0.05
UNET MxIter= 20
UNET MaxInSteps= 0
UNET DtIC= 0
UNET DtMin= 0
UNET MaxCRTS= 20
UNET WFStab= 2
UNET SFStab= 1
UNET WFX= 1
UNET SFX= 1
UNET DSS MLevel= 4
UNET DZMax Abort= 100
UNET Convert EG Bridges= 0
UNET Use Existing IB Tables=-1
UNET Froude Reduction=False
UNET Froude Limit= 1
UNET Froude Power= 10
UNET Time Slicing=0,0, 5
UNET Junction Losses=0
Instantaneous Interval=1HOUR
Write IC File= 0
Write IC File at Sim End=0
Echo Input=False
Echo Parameters=False
Echo Output=False
Write Detailed= 0
WQ AD Non Conservative
WQ ULTIMATE=-1
WQ Max Comp Step=1HOUR
WQ Output Interval=15MIN
WQ Output Selected Increments= 0
WQ Output face flow=0
WQ Output face velocity=0
WQ Output face area=0
WQ Output face dispersion=0
WQ Output cell volume=0
WQ Output cell surface area=0
WQ Output cell continuity=0
WQ Output cumulative cell continuity=0
WQ Output face conc=0
WQ Output face dconc_dx=0
WQ Output face courant=0
WQ Output face peclet=0
WQ Output face adv mass=0
WQ Output face disp mass=0
WQ Output cell mass=0
WQ Output cell source sink temp=0
WQ Output cell source sink nsm=0
WQ Output MaxMinRange=-1
WQ Daily Max Min Mean=-1
WQ Daily Range=0
WQ Daily Time=0
WQ Create Restart=0
WQ Fixed Restart=0
WQ System Summary=0
WQ Use Fixed Temperature=0
Sorting and Armoring Iterations= 10
XS Update Threshold= 0.02
Hydraulics Update Threshold= 0.02
Energy Slope Method= 1
Volume Change Method= 0
XS Weighting Method= 0
Number of US Weighted Cross Sections= 1
Number of DS Weighted Cross Sections= 1
Upstream XS Weight=0.25
Main XS Weight=0.5
Downstream XS Weight=0.25
Number of DS XS's Weighted with US Boundary= 1
Upstream Boundary Weight= 1
Weight of XSs Associated with US Boundary= 0
Number of US XS's Weighted with DS Boundary= 1
Downstream Boundary Weight= 0.5
Weight of XSs Associated with DS Boundary= 0.5
Sediment Output Level= 4
Mass or Volume Output= 0
Output Increment Type= 1
Profile and TS Output Increment= 10
XS Output Flag= 0
XS Output Increment= 10
Disregard all LS=0
Disregard all Conn=0
Disregard all Breaches=0
Disregard all Pumps=0

--- 1071.f02 (steady flow) ---

Flow Title=existing flow
Program Version=4.10
Number of Profiles= 2
Profile Names=50 YR,100 YR
River Rch & RM=Dbl 8,10x10           ,1914.25
    1060    1240
River Rch & RM=Dbl 8,10x10           ,1130.37
    1120    1310
Boundary for River Rch & Prof#=Dbl 8,10x10           , 1
Up Type= 0
Dn Type= 3
Dn Slope=0.007
Boundary for River Rch & Prof#=Dbl 8,10x10           , 2
Up Type= 0
Dn Type= 3
Dn Slope=0.007
DSS Import GetInterval= 0
DSS Import GetPeak= 0
DSS Import FillOption= 0

--- 1071.g01 (geometry) ---

Geom Title=Existing
Program Version=4.10

River Reach=Dbl 8           ,10x10
Reach XY= 2
-0.26264591439680.007782101167321.262645914396890.99221789883269

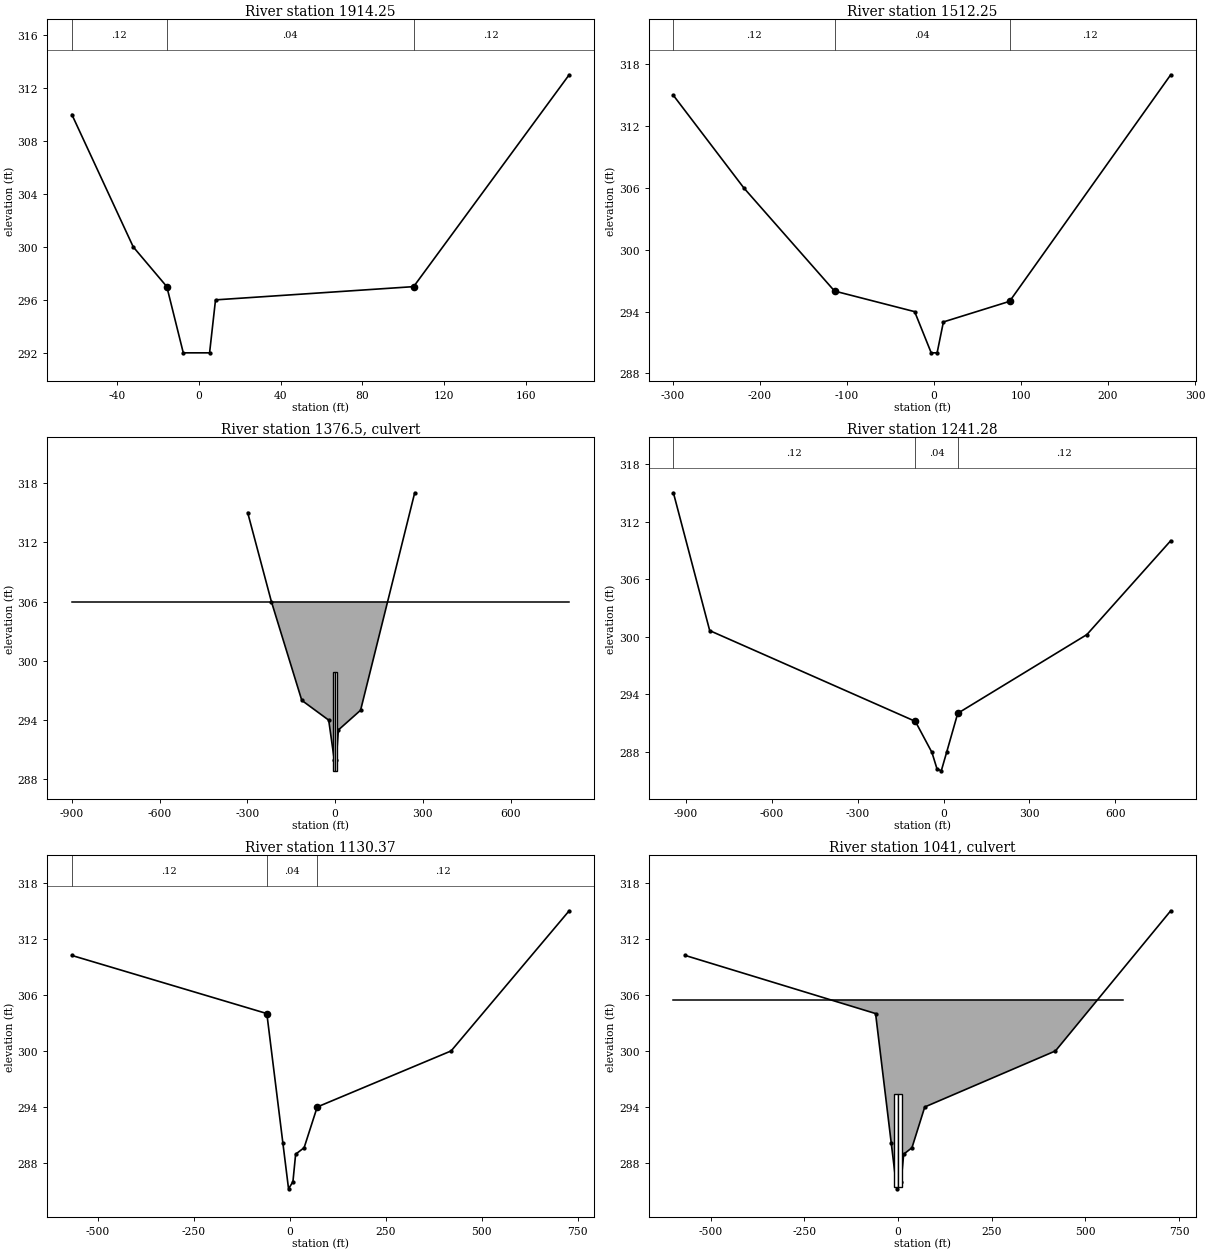
Type RM Length L Ch R = 1 ,1914.25 ,402,402,402
#Sta/Elev= 8
     -62     310     -32     300   -15.6     297   -7.55     292     5.3     292
     8.2     296     105     297     181     313
#Mann= 3 , 0 , 0
     -62     .12       0   -15.6     .04       0     105     .12       0
Bank Sta=-15.6,105
XS Rating Curve= 0 ,0
Exp/Cntr=0.3,0.1

Type RM Length L Ch R = 1 ,1512.25 ,271,271,271
#Sta/Elev= 9
    -299     315    -218     306    -114     296     -22     294   -2.99     290
     3.8     290      11     293      87     295     272     317
#Mann= 3 , 0 , 0
    -299     .12       0    -114     .04       0      87     .12       0
Bank Sta=-114,87
XS Rating Curve= 0 ,0
Exp/Cntr=0.5,0.3

Type RM Length L Ch R = 2 ,1376.5  ,,,
Bridge Culvert--1,0,-1,-1, 0
Deck Dist Width WeirC Skew NumUp NumDn MinLoCord MaxHiCord MaxSubmerge Is_Ogee
65,55,2.6,0, 2, 2, , , 0.98, 0, 1.5,1.5,,
    -900     800
     306     306
                
    -900     800
     306     306
                
BR Coef=-1 , 0 , 0 ,, 0 ,,,0.8,-1,,0,
WSPro=,,,, 1 ,,,, 0 ,,,, 0 ,,,,-1 ,-1 ,-1 , 0 , 0 , 0 , 0 , 0
Multiple Barrel Culv=2,10,8,110,0.012,0.2,1,8,1,288.87,288.61, 2,Culvert #1  , 0 ,42
    -4.6     -12       4       0
Culvert Bottom n=0.012
BC Design=,, 0 ,, 0 ,,,,,,
BC Use User HTab Curves=0
BC User HTab FreeFlow(D)= 0

Type RM Length L Ch R = 1 ,1241.28 ,111,111,111
#Sta/Elev= 10
    -944     315  -817.1 300.625   -98.5  291.16  -40.47  287.92  -22.83  286.21
    -7.8     286   11.34  287.98    49.7     292     501  300.21     794     310
#Mann= 3 , 0 , 0
    -944     .12       0   -98.5     .04       0    49.7     .12       0
Bank Sta=-98.5,49.7
XS Rating Curve= 0 ,0
Exp/Cntr=0.5,0.3

Type RM Length L Ch R = 1 ,1130.37 ,179,179,179
#Sta/Elev= 10
  -568.4  310.22  -60.11     304  -18.23 290.121    -3.5  285.24     7.9     286
   14.98  288.95  37.068  289.64    71.2     294  420.27     300     728     315
#Mann= 3 , 0 , 0
  -568.4     .12       0  -60.11     .04       0    71.2     .12       0
Bank Sta=-60.11,71.2
XS Rating Curve= 0 ,0
Exp/Cntr=0.3,0.1

Type RM Length L Ch R = 2 ,1041    ,,,
Bridge Culvert--1,0,-1,-1, 0
Deck Dist Width WeirC Skew NumUp NumDn MinLoCord MaxHiCord MaxSubmerge Is_Ogee
68,40,2.6,0, 2, 2, , , 0.98, 0, 1.5,1.5,,
    -600     600
   305.5   305.5
                
    -600     600
   305.5   305.5
                
BR Coef=-1 , 0 , 0 ,, 0 ,,,0.8,-1,,0,
WSPro=,,,, 1 ,,,, 0 ,,,, 0 ,,,,-1 ,-1 ,-1 , 0 , 0 , 0 , 0 , 0
Multiple Barrel Culv=2,10,10,88,0.012,0.2,1,8,1,285.4,285.32, 2,Culvert #1  , 0 ,38
      -6      -6       6       6
Culvert Bottom n=0.012
BC Design=,, 0 ,, 0 ,,,,,,
BC Use User HTab Curves=0
BC User HTab FreeFlow(D)= 0

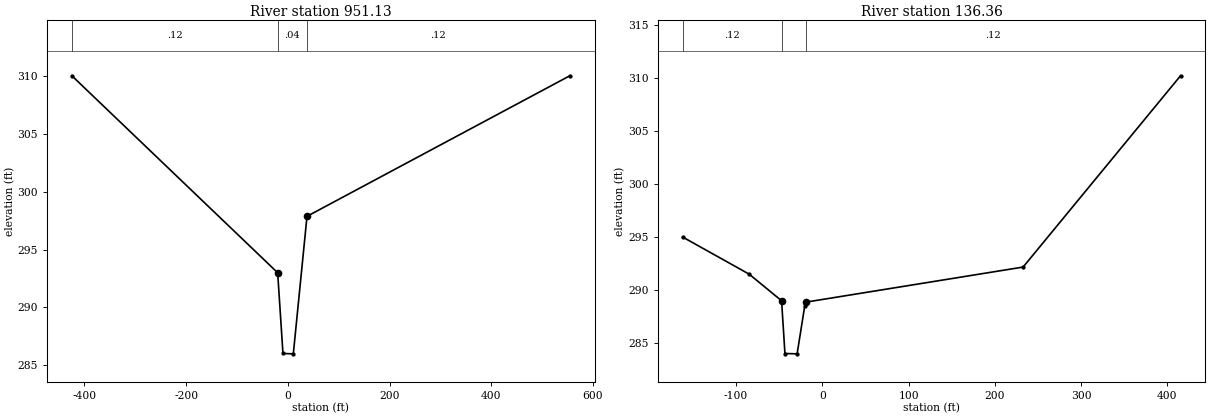
Type RM Length L Ch R = 1 ,951.13  ,815,815,815
#Sta/Elev= 6
 -424.68     310  -19.95     293   -9.53  286.03   10.83     286   37.75  297.87
  554.58     310
#Mann= 3 , 0 , 0
 -424.68     .12       0  -19.95     .04       0   37.75     .12       0
Bank Sta=-19.95,37.75
XS Rating Curve= 0 ,0
Exp/Cntr=0.5,0.3

Type RM Length L Ch R = 1 ,136.36  ,0,0,0
#Sta/Elev= 9
    -162     295  -84.76   291.5  -47.24     289  -43.32  284.03   -29.2     284
  -20.45  288.47  -18.91  288.87  232.83  292.17  415.36  310.18
#Mann= 3 , 0 , 0
    -162     .12       0  -47.24     .04       0  -18.91     .12       0
Bank Sta=-47.24,-18.91
XS Rating Curve= 0 ,0
Exp/Cntr=0.3,0.1

Chan Stop Cuts=-1
Use User Specified Reach Order=0
Composite Channel Slope=5