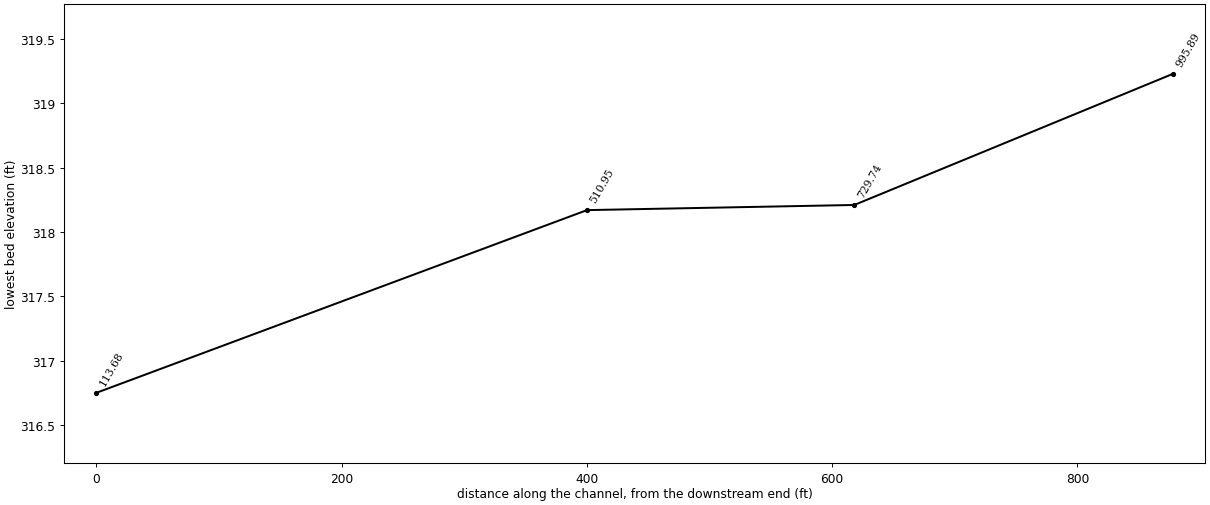
--- Culvert1168+50.prj (project) ---

Proj Title=Culvert 1168+50
Current Plan=p01
Default Exp/Contr=0.3,0.1
English Units
Geom File=..\1521\Culvert1168+50.g01
Geom File=g02
Flow File=f01
Plan File=p01
Y Axis Title=Elevation
X Axis Title(PF)=Main Channel Distance
X Axis Title(XS)=Station
BEGIN DESCRIPTION:
END DESCRIPTION:
DSS Export Rating Curves= 0
DSS Export Rating Curve Sorted= 0
DSS Export Volume Flow Curves= 0
DXF OffsetX= 0
DXF OffsetY= 0
DXF ScaleX= 1
DXF ScaleY= 10

--- Culvert1168+50.p01 (plan) ---

Plan Title=Existing
Program Version=4.10
Short Identifier=Existing
Geom File=g02
Flow File=f01
Subcritical Flow
K Sum by GR= 0
Std Step Tol= 0.01
Critical Tol= 0.01
Num of Std Step Trials= 20
Max Error Tol= 0.3
Flow Tol Ratio= 0.001
Split Flow NTrial= 30
Split Flow Tol= 0.02
Split Flow Ratio= 0.02
Log Output Level= 0
Friction Slope Method= 1
Unsteady Friction Slope Method= 2
Unsteady Bridges Friction Slope Method= 1
Parabolic Critical Depth
Global Vel Dist= 0 , 0 , 0
Global Log Level= 0
CheckData=True
Encroach Param=-1 ,0,0, 0
Computation Interval=1HOUR
Output Interval=1HOUR
Run HTab= 0
Run UNet= 0
Run PostProcess= 0
Run WQNet= 0
UNET Theta= 1
UNET Theta Warmup= 1
UNET ZTol= 0.02
UNET ZSATol= 0.05
UNET MxIter= 20
UNET MaxInSteps= 0
UNET DtIC= 0
UNET DtMin= 0
UNET MaxCRTS= 20
UNET WFStab= 2
UNET SFStab= 1
UNET WFX= 1
UNET SFX= 1
UNET DSS MLevel= 4
UNET DZMax Abort= 100
UNET Convert EG Bridges= 0
UNET Use Existing IB Tables=-1
UNET Froude Reduction=False
UNET Froude Limit= 1
UNET Froude Power= 10
UNET Time Slicing=0,0, 5
UNET Junction Losses=0
Instantaneous Interval=1HOUR
Write IC File= 0
Write IC File at Sim End=0
Echo Input=False
Echo Parameters=False
Echo Output=False
Write Detailed= 0
WQ AD Non Conservative
WQ ULTIMATE=-1
WQ Max Comp Step=1HOUR
WQ Output Interval=15MIN
WQ Output Selected Increments= 0
WQ Output face flow=0
WQ Output face velocity=0
WQ Output face area=0
WQ Output face dispersion=0
WQ Output cell volume=0
WQ Output cell surface area=0
WQ Output cell continuity=0
WQ Output cumulative cell continuity=0
WQ Output face conc=0
WQ Output face dconc_dx=0
WQ Output face courant=0
WQ Output face peclet=0
WQ Output face adv mass=0
WQ Output face disp mass=0
WQ Output cell mass=0
WQ Output cell source sink temp=0
WQ Output cell source sink nsm=0
WQ Output MaxMinRange=-1
WQ Daily Max Min Mean=-1
WQ Daily Range=0
WQ Daily Time=0
WQ Create Restart=0
WQ Fixed Restart=0
WQ System Summary=0
WQ Use Fixed Temperature=0
Sorting and Armoring Iterations= 10
XS Update Threshold= 0.02
Hydraulics Update Threshold= 0.02
Energy Slope Method= 1
Volume Change Method= 0
XS Weighting Method= 0
Number of US Weighted Cross Sections= 1
Number of DS Weighted Cross Sections= 1
Upstream XS Weight=0.25
Main XS Weight=0.5
Downstream XS Weight=0.25
Number of DS XS's Weighted with US Boundary= 1
Upstream Boundary Weight= 1
Weight of XSs Associated with US Boundary= 0
Number of US XS's Weighted with DS Boundary= 1
Downstream Boundary Weight= 0.5
Weight of XSs Associated with DS Boundary= 0.5
Sediment Output Level= 4
Mass or Volume Output= 0
Output Increment Type= 1
Profile and TS Output Increment= 10
XS Output Flag= 0
XS Output Increment= 10
Disregard all LS=0
Disregard all Conn=0
Disregard all Breaches=0
Disregard all Pumps=0

--- Culvert1168+50.f01 (steady flow) ---

Flow Title=Flow data
Program Version=4.10
Number of Profiles= 2
Profile Names=50 YR,100 YR
River Rch & RM=1168+26,Main            ,995.89
    1530    1780
Boundary for River Rch & Prof#=1168+26,Main            , 1
Up Type= 0
Dn Type= 3
Dn Slope=0.007
Boundary for River Rch & Prof#=1168+26,Main            , 2
Up Type= 0
Dn Type= 3
Dn Slope=0.007
DSS Import GetInterval= 0
DSS Import GetPeak= 0
DSS Import FillOption= 0

--- Culvert1168+50.g02 (geometry) ---

Geom Title=Existing
Program Version=4.10

River Reach=1168+26         ,Main
Reach XY= 2
-0.23929961089490.072632944228281.183527885862520.96757457846952

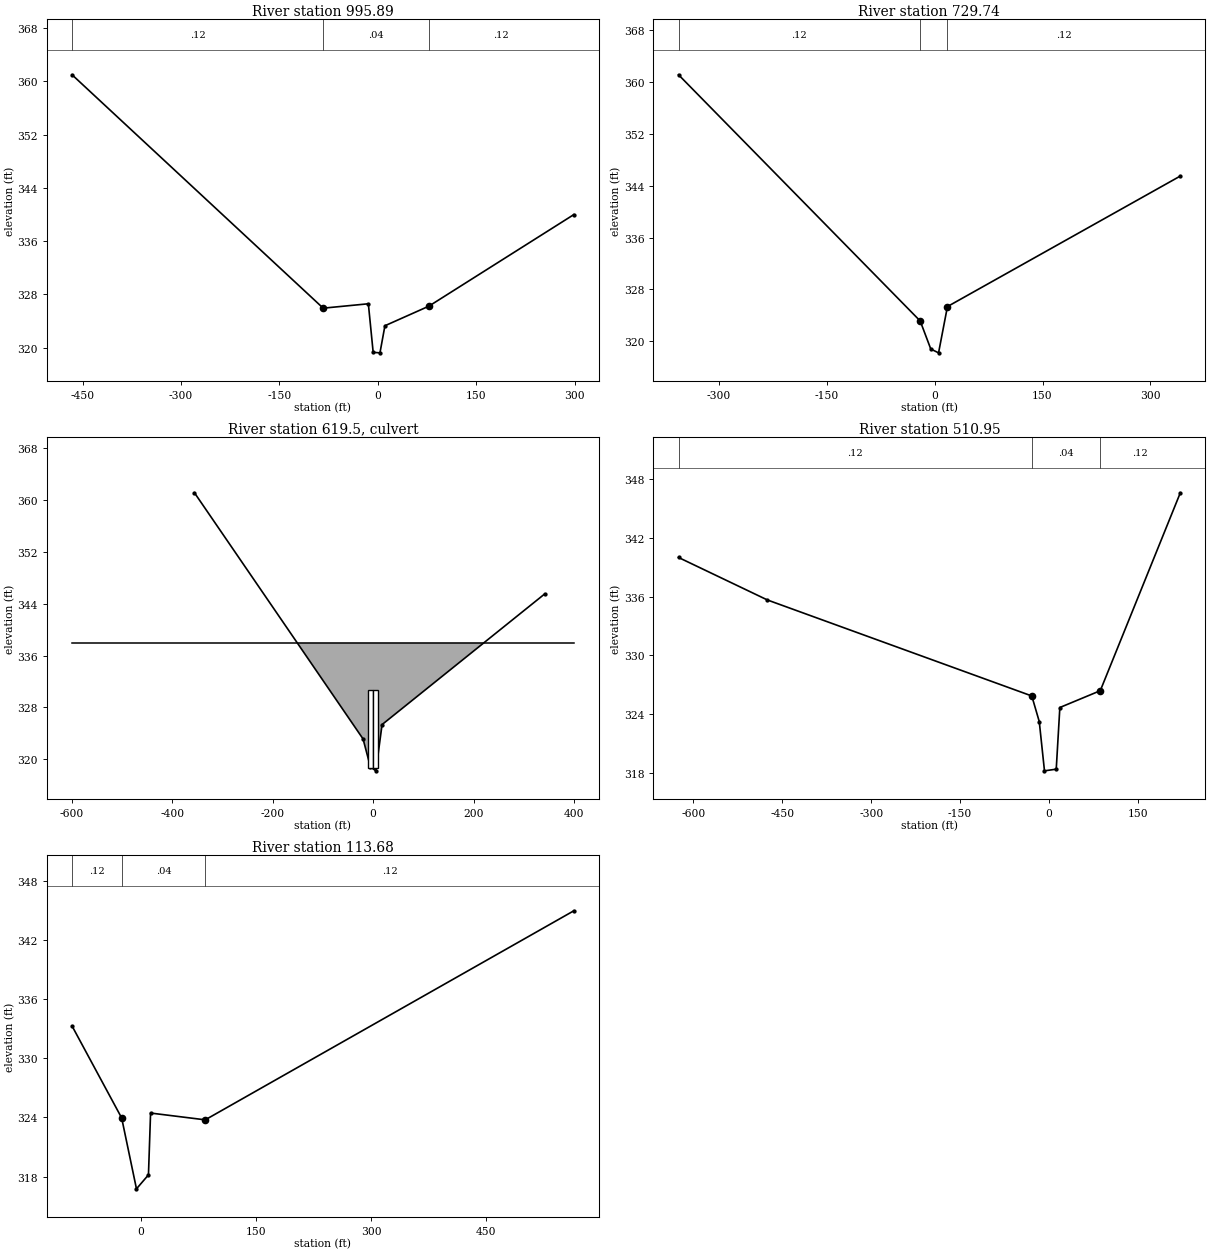
Type RM Length L Ch R = 1 ,995.89  ,260,260,260
#Sta/Elev= 8
    -466     361  -83.14  325.94   -14.3   326.6   -6.96   319.3     3.4  319.23
   10.96   323.3   77.96  326.24     299     340
#Mann= 3 , 0 , 0
    -466     .12       0  -83.14     .04       0   77.96     .12       0
Bank Sta=-83.14,77.96
XS Rating Curve= 0 ,0
Exp/Cntr=0.3,0.1

Type RM Length L Ch R = 1 ,729.74  ,218,218,218
#Sta/Elev= 6
  -356.1  361.13  -20.08  323.13   -5.36   318.8    5.47  318.21    17.8  325.35
  341.63   345.5
#Mann= 3 , 0 , 0
  -356.1     .12       0  -20.08     .04       0    17.8     .12       0
Bank Sta=-20.08,17.8
XS Rating Curve= 0 ,0
Exp/Cntr=0.5,0.3

Type RM Length L Ch R = 2 ,619.5   ,,,
Bridge Culvert--1,0,-1,-1, 0
Deck Dist Width WeirC Skew NumUp NumDn MinLoCord MaxHiCord MaxSubmerge Is_Ogee
75,80,2.6,0, 2, 2, , , 0.98, 0, 1.5,1.5,,
    -600     400
     338     338
                
    -600     400
     338     338
                
BR Coef=-1 , 0 , 0 ,, 0 ,,,0.8,-1,,0,
WSPro=,,,, 1 ,,,, 0 ,,,, 0 ,,,,-1 ,-1 ,-1 , 0 , 0 , 0 , 0 , 0
Multiple Barrel Culv=2,12,10,140,0.012,0.2,1,8,1,318.62,318.06, 2,Culvert #1  , 0 ,35
      -5      -5       5       5
Culvert Bottom n=0.012
BC Design=,, 0 ,, 0 ,,,,,,
BC Use User HTab Curves=0
BC User HTab FreeFlow(D)= 0

Type RM Length L Ch R = 1 ,510.95  ,400,400,400
#Sta/Elev= 9
    -625     340 -474.98  335.65  -29.01  325.83  -16.42  323.21   -7.62  318.17
   12.22  318.34   18.31  324.65   86.53  326.37  221.57  346.62
#Mann= 3 , 0 , 0
    -625     .12       0  -29.01     .04       0   86.53     .12       0
Bank Sta=-29.01,86.53
XS Rating Curve= 0 ,0
Exp/Cntr=0.5,0.3

Type RM Length L Ch R = 1 ,113.68  ,0,0,0
#Sta/Elev= 7
  -89.23  333.29  -24.66  323.95   -5.39  316.75   10.21  318.17   12.97  324.45
   84.12  323.76     564     345
#Mann= 3 , 0 , 0
  -89.23     .12       0  -24.66     .04       0   84.12     .12       0
Bank Sta=-24.66,84.12
XS Rating Curve= 0 ,0
Exp/Cntr=0.3,0.1

Chan Stop Cuts=-1
Use User Specified Reach Order=0
Composite Channel Slope=5