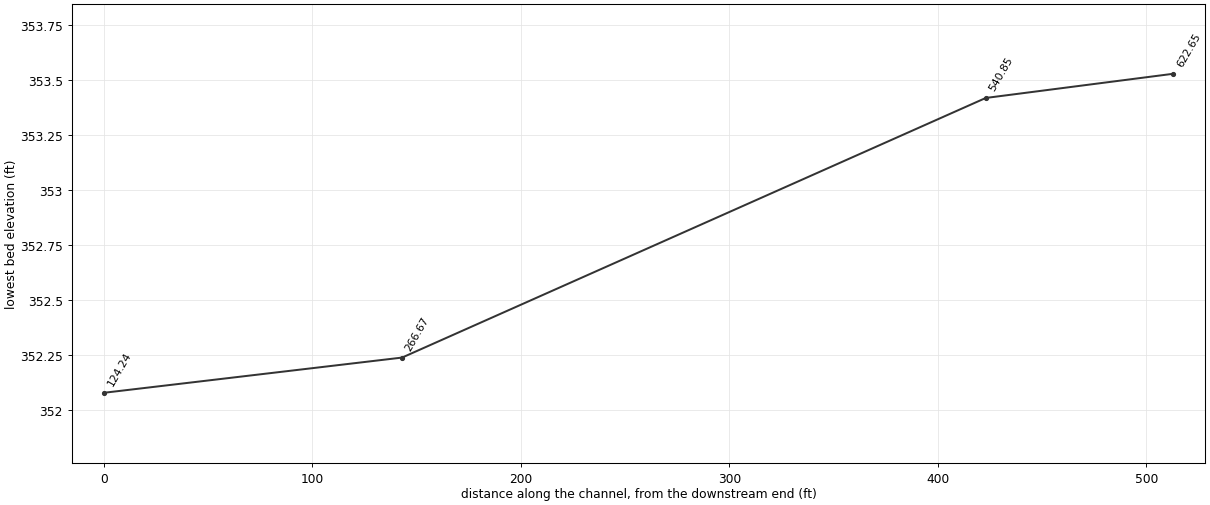
--- forculvert1521.prj (project) ---

Proj Title=forculvert1521
Current Plan=p01
Default Exp/Contr=0.3,0.1
English Units
Geom File=g01
Flow File=f01
Plan File=p01
Y Axis Title=Elevation
X Axis Title(PF)=Main Channel Distance
X Axis Title(XS)=Station
BEGIN DESCRIPTION:
END DESCRIPTION:
DSS Export Rating Curves= 0
DSS Export Rating Curve Sorted= 0
DSS Export Volume Flow Curves= 0
DXF OffsetX= 0
DXF OffsetY= 0
DXF ScaleX= 1
DXF ScaleY= 10

--- forculvert1521.p01 (plan) ---

Plan Title=Existing
Program Version=4.10
Short Identifier=Existing
Geom File=g01
Flow File=f01
Subcritical Flow
K Sum by GR= 0
Std Step Tol= 0.01
Critical Tol= 0.01
Num of Std Step Trials= 20
Max Error Tol= 0.3
Flow Tol Ratio= 0.001
Split Flow NTrial= 30
Split Flow Tol= 0.02
Split Flow Ratio= 0.02
Log Output Level= 0
Friction Slope Method= 1
Unsteady Friction Slope Method= 2
Unsteady Bridges Friction Slope Method= 1
Parabolic Critical Depth
Global Vel Dist= 0 , 0 , 0
Global Log Level= 0
CheckData=True
Encroach Param=-1 ,0,0, 0
Computation Interval=1HOUR
Output Interval=1HOUR
Run HTab= 0
Run UNet= 0
Run PostProcess= 0
Run WQNet= 0
UNET Theta= 1
UNET Theta Warmup= 1
UNET ZTol= 0.02
UNET ZSATol= 0.05
UNET MxIter= 20
UNET MaxInSteps= 0
UNET DtIC= 0
UNET DtMin= 0
UNET MaxCRTS= 20
UNET WFStab= 2
UNET SFStab= 1
UNET WFX= 1
UNET SFX= 1
UNET DSS MLevel= 4
UNET DZMax Abort= 100
UNET Convert EG Bridges= 0
UNET Use Existing IB Tables=-1
UNET Froude Reduction=False
UNET Froude Limit= 1
UNET Froude Power= 10
UNET Time Slicing=0,0, 5
UNET Junction Losses=0
Instantaneous Interval=1HOUR
Write IC File= 0
Write IC File at Sim End=0
Echo Input=False
Echo Parameters=False
Echo Output=False
Write Detailed= 0
WQ AD Non Conservative
WQ ULTIMATE=-1
WQ Max Comp Step=1HOUR
WQ Output Interval=15MIN
WQ Output Selected Increments= 0
WQ Output face flow=0
WQ Output face velocity=0
WQ Output face area=0
WQ Output face dispersion=0
WQ Output cell volume=0
WQ Output cell surface area=0
WQ Output cell continuity=0
WQ Output cumulative cell continuity=0
WQ Output face conc=0
WQ Output face dconc_dx=0
WQ Output face courant=0
WQ Output face peclet=0
WQ Output face adv mass=0
WQ Output face disp mass=0
WQ Output cell mass=0
WQ Output cell source sink temp=0
WQ Output cell source sink nsm=0
WQ Output MaxMinRange=-1
WQ Daily Max Min Mean=-1
WQ Daily Range=0
WQ Daily Time=0
WQ Create Restart=0
WQ Fixed Restart=0
WQ System Summary=0
WQ Use Fixed Temperature=0
Sorting and Armoring Iterations= 10
XS Update Threshold= 0.02
Hydraulics Update Threshold= 0.02
Energy Slope Method= 1
Volume Change Method= 0
XS Weighting Method= 0
Number of US Weighted Cross Sections= 1
Number of DS Weighted Cross Sections= 1
Upstream XS Weight=0.25
Main XS Weight=0.5
Downstream XS Weight=0.25
Number of DS XS's Weighted with US Boundary= 1
Upstream Boundary Weight= 1
Weight of XSs Associated with US Boundary= 0
Number of US XS's Weighted with DS Boundary= 1
Downstream Boundary Weight= 0.5
Weight of XSs Associated with DS Boundary= 0.5
Sediment Output Level= 4
Mass or Volume Output= 0
Output Increment Type= 1
Profile and TS Output Increment= 10
XS Output Flag= 0
XS Output Increment= 10
Disregard all LS=0
Disregard all Conn=0
Disregard all Breaches=0
Disregard all Pumps=0

--- forculvert1521.f01 (steady flow) ---

Flow Title=Steady Flow
Program Version=4.10
Number of Profiles= 2
Profile Names=50 YR,100 YR
River Rch & RM=Dbl 12x12,Main            ,622.65
    1830    2130
Boundary for River Rch & Prof#=Dbl 12x12,Main            , 1
Up Type= 0
Dn Type= 3
Dn Slope=0.007
Boundary for River Rch & Prof#=Dbl 12x12,Main            , 2
Up Type= 0
Dn Type= 3
Dn Slope=0.007
DSS Import GetInterval= 0
DSS Import GetPeak= 0
DSS Import FillOption= 0

--- forculvert1521.g01 (geometry) ---

Geom Title=Existing
Program Version=4.10

River Reach=Dbl 12x12       ,Main
Reach XY= 2
0.091439688715950.30090791180285 0.66861219195850.70817120622568

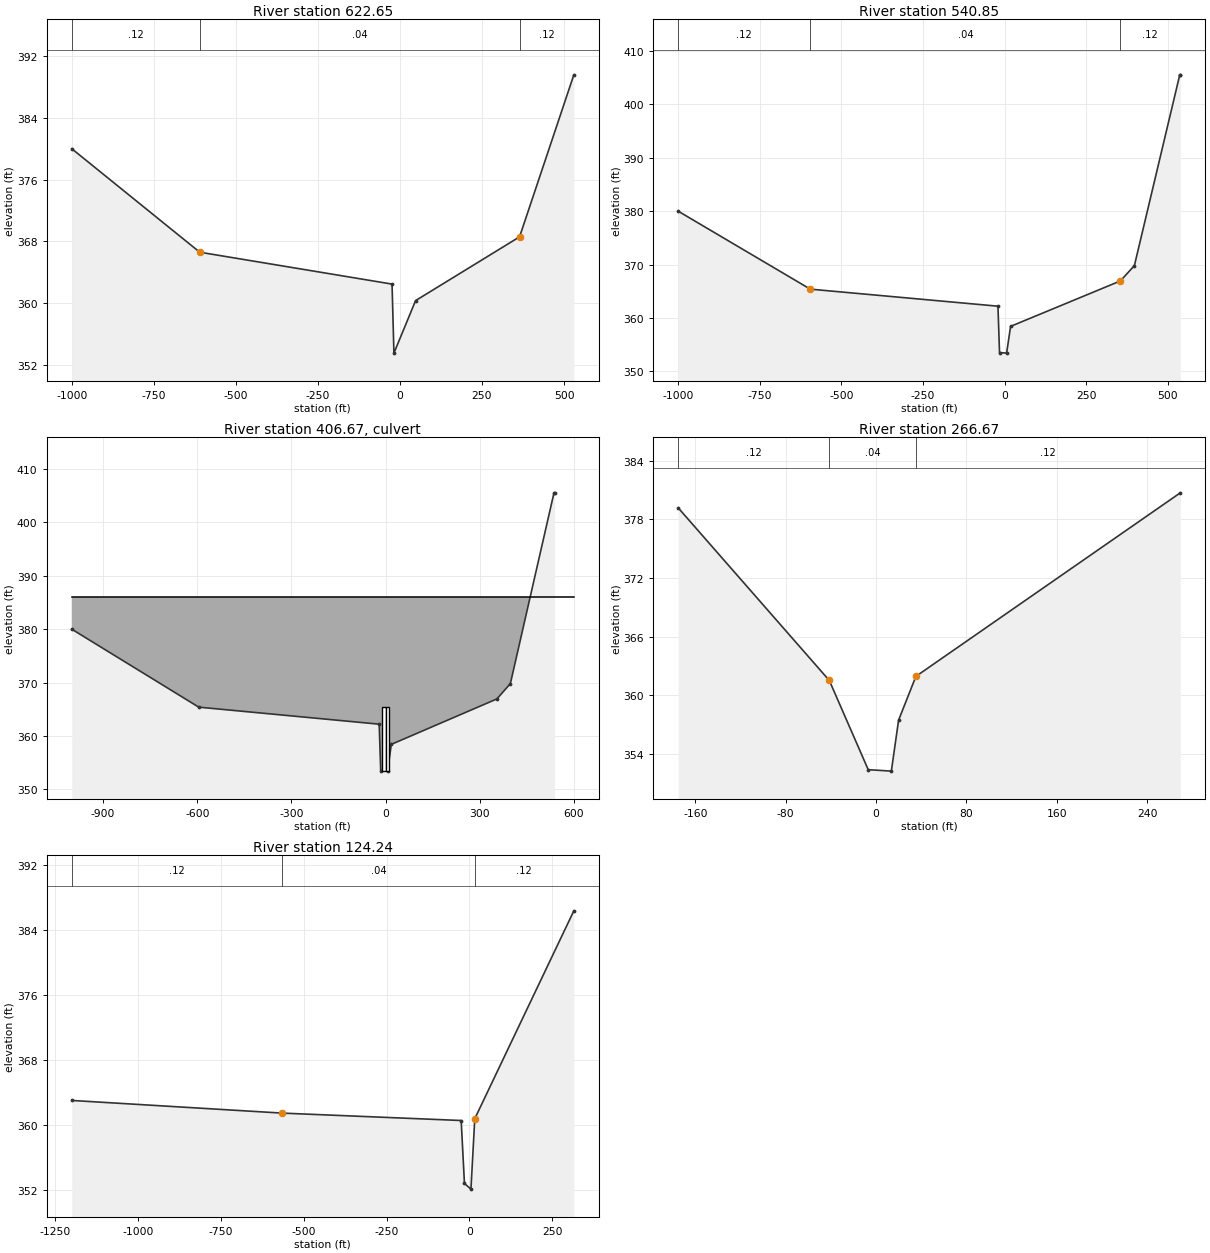
Type RM Length L Ch R = 1 ,622.65  ,85,90,95
#Sta/Elev= 7
   -1000     380-610.045   366.6  -24.06  362.47  -18.32  353.53   47.67  360.33
  364.55  368.59  529.92  389.57
#Mann= 3 , 0 , 0
   -1000     .12       0-610.045     .04       0  364.55     .12       0
Bank Sta=-610.045,364.55
XS Rating Curve= 0 ,0
Exp/Cntr=0.3,0.1

Type RM Length L Ch R = 1 ,540.85  ,280,280,280
#Sta/Elev= 10
   -1000     380 -595.35   365.4  -20.34  362.21  -15.52  353.53     6.2  353.42
   18.38  358.43  354.81  366.94  397.72  369.81  536.75  405.54  538.43  405.54
#Mann= 3 , 0 , 0
   -1000     .12       0 -595.35     .04       0  354.81     .12       0
Bank Sta=-595.35,354.81
XS Rating Curve= 0 ,0
Exp/Cntr=0.5,0.3

Type RM Length L Ch R = 2 ,406.67  ,,,
Bridge Culvert--1,0,-1,-1, 0
Deck Dist Width WeirC Skew NumUp NumDn MinLoCord MaxHiCord MaxSubmerge Is_Ogee
98,75,2.6,0, 2, 2, , , 0.98, 0, 2,2,,
   -1000     600
     386     386
                
    -600     600
     386     386
                
BR Coef=-1 , 0 , 0 ,, 0 ,,,0.8,-1,,0,
WSPro=,,,, 1 ,,,, 0 ,,,, 0 ,,,,-1 ,-1 ,-1 , 0 , 0 , 0 , 0 , 0
Multiple Barrel Culv=2,12,12,195,0.012,0.2,1,8,1,353.5,352.2, 2,Culvert #1  , 0 ,42.5
      -6      -6       6       6
Culvert Bottom n=0.012
BC Design=,, 0 ,, 0 ,,,,,,
BC Use User HTab Curves=0
BC User HTab FreeFlow(D)= 0

Type RM Length L Ch R = 1 ,266.67  ,150,143,135
#Sta/Elev= 7
 -175.05  379.16  -41.31  361.51   -6.88  352.39    13.6  352.24  20.014  357.45
   35.34  361.93   269.4   380.7
#Mann= 3 , 0 , 0
 -175.05     .12       0  -41.31     .04       0   35.34     .12       0
Bank Sta=-41.31,35.34
XS Rating Curve= 0 ,0
Exp/Cntr=0.5,0.3

Type RM Length L Ch R = 1 ,124.24  ,0,0,0
#Sta/Elev= 7
   -1200     363 -564.62  361.44  -24.96  360.53   -15.1  352.78     4.5  352.08
   16.05  360.75     315  386.35
#Mann= 3 , 0 , 0
   -1200     .12       0 -564.62     .04       0   16.05     .12       0
Bank Sta=-564.62,16.05
XS Rating Curve= 0 ,0
Exp/Cntr=0.3,0.1

Chan Stop Cuts=-1
Use User Specified Reach Order=0
Composite Channel Slope=5